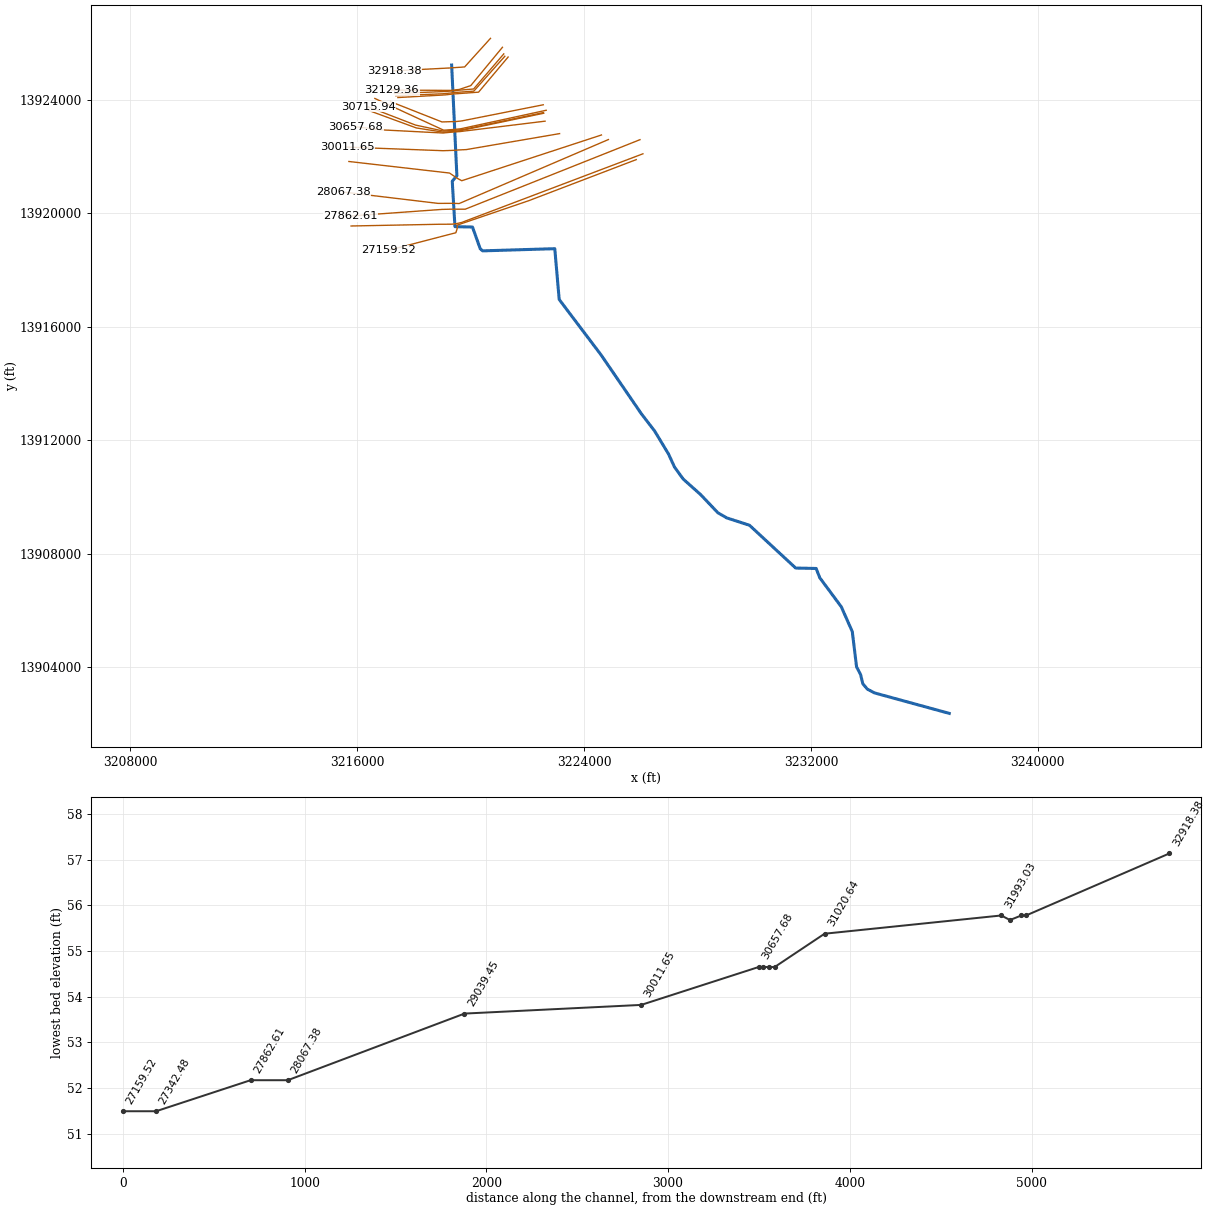
--- Q128-00-00.prj (project) ---

Proj Title=Q128-00-00
Current Plan=p06
Default Exp/Contr=.3,.1
English Units
Geom File=g05
Flow File=f01
Flow File=f05
Plan File=p04
Plan File=p06
Y Axis Title=Elevation
X Axis Title(PF)=Main Channel Distance
X Axis Title(XS)=Station
BEGIN DESCRIPTION:
Adlong Ditch, HCFCD Unit Q128-00-00
Flood Hazard and Floodway Model
10, 2, 1, & 0.2% Events
Filename: Q128.prj
Prepared by: Costello, Inc. Date: February, 2004
Reviewed by: _________ Date:____________
Status: Final
END DESCRIPTION:
DSS Export Rating Curves= 0
DSS Export Rating Curve Sorted= 0
DSS Export Volume Flow Curves= 0
DXF OffsetX= 0
DXF OffsetY= 0
DXF ScaleX= 1
DXF ScaleY= 10

--- Q128-00-00.p06 (plan) ---

Plan Title=Floodway
Version=Version 3.0.1  Mar 2001
Short Identifier=Floodway0607
Geom File=g05
Flow File=f05
Subcritical Flow
K Sum by GR= 0
Std Step Tol= 0.006
Critical Tol= 0.001
Num of Std Step Trials= 23
Max Error Tol= 1
Flow Tol Ratio= 0.01
Split Flow NTrial= 60
Split Flow Tol= 0.001
Split Flow Ratio= 0.0001
Log Output Level= 0
Friction Slope Method= 2
Unsteady Friction Slope Method= 2
Secant Critical Depth
Global Vel Dist= 0 , 0 , 0
Global Log Level= 0
Log Level Location=Q128            ,Q128            ,9511.879, 7 , 1
CheckData=True
Encroach Param=-1 ,0,0, 2
Encroach River=Q128-00-00
Encroach Reach=Q128-00-00_0001
Encroach Node=32918.38
       1 1803.08    1847
Encroach Node=32129.36
       1    2406    2441
Encroach Node=32103.52
       1    2360 2402.22
Encroach Node=32070
       1    2208    2458
Encroach Node=32040.66
       1    2379 2422.23
Encroach Node=31993.03
       1    2520 2556.25
Encroach Node=31020.64
       1    3188    3222
Encroach Node=30746.02
       1    3295    3332
Encroach Node=30715.94
       1    3184    3221
Encroach Node=30700
       1 3183.75  3236.5
Encroach Node=30679.44
       1 3191.25    3244
Encroach Node=30657.68
       1    3202    3239
Encroach Node=30011.65
       1    3706    3747
Encroach Node=29039.45
       1    5416    5465
Encroach Node=28067.38
       1    5910    5949
Encroach Node=27862.61
       1    7023    7062
Encroach Node=27342.48
       1    6678    7278
Encroach Node=27159.52
       1    6210    6848
Encroach Node=26310.80
       1    5809    6486
Encroach Node=26284.87
       1    5803    6573
Encroach Node=26250
       1    5829    6580
Encroach Node=26215.72
       1    5855    6625
Encroach Node=26159.63
       1    5857    6784
Encroach Node=25350.23
       1    6125    7574
Encroach Node=24542.46
       1    5480    6510
Encroach Node=24497.51
       1    4250    5280
Encroach Node=24450
       1    4350    4750
Encroach Node=24423.35
       1    4000    5030
Encroach Node=24352.01
       1    3913    4860
Encroach Node=23556.57
       1    3112    4102
Encroach Node=22602.06
       1    4036    5006
Encroach Node=21514.76
       1    5429    6389
Encroach Node=21474.39
       1    5540    6529
Encroach Node=21400
       1    5380    6700
Encroach Node=21369.81
       1    5630    6600
Encroach Node=21328.17
       1    5656    6606
Encroach Node=21037.37
       1    5663    6613
Encroach Node=20683.59
       1    5680    6655
Encroach Node=20564.84
       1    5716    6666
Encroach Node=20510.66
       1    5657    6600
Encroach Node=20400
       1    5615    6600
Encroach Node=20349.55
       1    5618    6560
Encroach Node=20284.89
       1    5600    6550
Encroach Node=20135.50
       1    5450    6400
Encroach Node=20098.65
       1    5437    6387
Encroach Node=20080
       1    5322    6472
Encroach Node=20064.37
       1    5407    6357
Encroach Node=20015.84
       1    5387    6337
Encroach Node=19556.38
       1    5277    6227
Encroach Node=19225.07
       1    5177    6125
Encroach Node=19192.09
       1    5268    6218
Encroach Node=19160
       1  5163.5  6313.5
Encroach Node=19141.10
       1    5275    6175
Encroach Node=19062.63
       1    5432    6325
Encroach Node=19033.02
       1    5583    6483
Encroach Node=19020
       1  5541.5  6641.5
Encroach Node=19004.74
       1    5635    6535
Encroach Node=18973.43
       1    5754    6654
Encroach Node=18338.17
       1    5934    6834
Encroach Node=17560.39
       1    6182    7082
Encroach Node=17531.26
       1    6150    7050
Encroach Node=17500
       1  6052.5  7102.5
Encroach Node=17494.45
       1    6100    7000
Encroach Node=17464.99
       1    6014    6914
Encroach Node=17371.83
       1    6070    6970
Encroach Node=16432.65
       1    6376    7276
Encroach Node=16301.42
       1    6462    7362
Encroach Node=15393.05
       1    6472    7373
Encroach Node=14800.56
       1    6573    7473
Encroach Node=14766.30
       1    6950    7850
Encroach Node=14700
       1    3900    7400
Encroach Node=14651.86
       1    3550    4450
Encroach Node=14600
       1    3900    4700
Encroach Node=14534.02
       1    4217    5117
Encroach Node=14474.57
       1    4754    5604
Encroach Node=14383.70
       1    4698    5548
Encroach Node=14300
       1    4675    5525
Encroach Node=14229.25
       1    4652    5502
Encroach Node=14079.22
       1    4617    5467
Encroach Node=13518.22
       1    3654    4504
Encroach Node=13500
       1    3658    4508
Encroach Node=13486.67
       1    3550    4426
Encroach Node=13460
       1  3548.5  4424.5
Encroach Node=13435.00
       1    3666    4516
Encroach Node=12771.34
       1    3764    4614
Encroach Node=12699.64
       1    3799    4649
Encroach Node=12600
       1  3833.5  4683.5
Encroach Node=12566.80
       1    3868    4718
Encroach Node=12503.04
       1    3994    4842
Encroach Node=11694.88
       1    4128    4975
Encroach Node=10723.57
       1    4217    5067
Encroach Node=10669.62
       1    4215    5058
Encroach Node=10640
       1  4211.5  5054.5
Encroach Node=10617.79
       1    4148    5053
Encroach Node=10571.19
       1    4182    5077
Encroach Node=9726.464
       1    4710    5610
Encroach Node=9590.477
       1    4875    5775
Encroach Node=9550
       1    4600    5350
Encroach Node=9511.879
       1    4662    5612
Encroach Node=9469.325
       1    4600    5550
Encroach Node=8768.922
       1    4525    5478
Encroach Node=7774.364
       1    1805    2745
Encroach Node=7664.989
       1    1948    2893
Encroach Node=6810.434
       1    2500    3400
Encroach Node=6593.142
       1    2800    3695
Encroach Node=6457.308
       1    2670    3560
Encroach Node=5820.481
       1    2954    3854
Encroach Node=5211.852
       1     752    1592
Encroach Node=5147.383
       1     724    1524
Encroach Node=5135
       1     724    1455
Encroach Node=5129.793
       1     705    1455
Encroach Node=5107.502
       1     750    1450
Encroach Node=4805.194
       1     734    1434
Encroach Node=3842.296
       1    1301    1915
Encroach Node=2778.698
       1    2210    3010
Encroach Node=1941.131
       1    2351    2682
Encroach Node=1714.976
       1    2458    2789
Encroach Node=795.239
       1    2325    2775
Encroach Node=107.522
       1 2476.16    2586
Computation Interval=1HOUR
Output Interval=1HOUR
Run HTab= 0
Run UNet= 0
Run PostProcess= 0
UNET Theta= 1
UNET ZTol= 0.02
UNET ZSATol= 0.1
UNET MxIter= 20
UNET MaxInSteps= 20
UNET DtIC= 0
UNET DtMin= 0
UNET MaxCRTS= 20
UNET WFStab= 2
UNET SFStab= 1
UNET WFX= 1
UNET SFX= 1
UNET Convert EG Bridges=-1
UNET Use Existing IB Tables=-1
Instantaneous Interval=1HOUR
Write IC File= 0
Write Velocity= 0
Write Detailed= 0

--- Q128-00-00.p03 (plan) ---

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Plan Title=Q128-CL sta shift to new-FH
Short Identifier=CLsta->new
Geom File=g04
Flow File=f01
K Sum by GR=-1
DSS File=dss

--- Q128-00-00.p04 (plan) ---

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Plan Title=FEMA Effective June 2007
Short Identifier=FEMAeff0607
Geom File=g05
Flow File=f01

--- Q128-00-00.f05 (steady flow) ---

Flow Title=Floodway
Version=Version 3.0.1  Mar 2001
Number of Profiles= 2
Profile Names=1PCT_100yr,1PCTFloodway_100yrFW
River Rch & RM=Q128-00-00,Q128-00-00_0001 ,32918.38
      59      59
River Rch & RM=Q128-00-00,Q128-00-00_0001 ,32129.36
      60      60
River Rch & RM=Q128-00-00,Q128-00-00_0001 ,32103.52
      63      63
River Rch & RM=Q128-00-00,Q128-00-00_0001 ,31993.03
      99      99
River Rch & RM=Q128-00-00,Q128-00-00_0001 ,31020.64
     112     112
River Rch & RM=Q128-00-00,Q128-00-00_0001 ,30746.02
     114     114
River Rch & RM=Q128-00-00,Q128-00-00_0001 ,30715.94
     117     117
River Rch & RM=Q128-00-00,Q128-00-00_0001 ,30657.68
     158     158
River Rch & RM=Q128-00-00,Q128-00-00_0001 ,30011.65
     248     248
River Rch & RM=Q128-00-00,Q128-00-00_0001 ,29039.45
     390     390
River Rch & RM=Q128-00-00,Q128-00-00_0001 ,28067.38
     429     429
River Rch & RM=Q128-00-00,Q128-00-00_0001 ,27862.61
     546     546
River Rch & RM=Q128-00-00,Q128-00-00_0001 ,27342.48
     594     594
River Rch & RM=Q128-00-00,Q128-00-00_0001 ,27159.52
     881     881
River Rch & RM=Q128-00-00,Q128-00-00_0001 ,26310.80
     895     895
River Rch & RM=Q128-00-00,Q128-00-00_0001 ,26159.63
     971     971
River Rch & RM=Q128-00-00,Q128-00-00_0001 ,25350.23
    1053    1053
River Rch & RM=Q128-00-00,Q128-00-00_0001 ,24542.46
    1073    1073
River Rch & RM=Q128-00-00,Q128-00-00_0001 ,24352.01
    1163    1163
River Rch & RM=Q128-00-00,Q128-00-00_0001 ,23556.57
    1280    1280
River Rch & RM=Q128-00-00,Q128-00-00_0001 ,22602.06
    1429    1429
River Rch & RM=Q128-00-00,Q128-00-00_0001 ,21514.76
    1499    1499
River Rch & RM=Q128-00-00,Q128-00-00_0001 ,21037.37
    1554    1554
River Rch & RM=Q128-00-00,Q128-00-00_0001 ,20683.59
    2582    2582
River Rch & RM=Q128-00-00,Q128-00-00_0001 ,14766.30
    2663    2663
River Rch & RM=Q128-00-00,Q128-00-00_0001 ,14383.70
    2702    2702
River Rch & RM=Q128-00-00,Q128-00-00_0001 ,14079.22
    2776    2776
River Rch & RM=Q128-00-00,Q128-00-00_0001 ,10723.57
    2862    2862
River Rch & RM=Q128-00-00,Q128-00-00_0001 ,8768.922
    2908    2908
River Rch & RM=Q128-00-00,Q128-00-00_0001 ,7774.364
    3089    3089
River Rch & RM=Q128-00-00,Q128-00-00_0001 ,7664.989
    3188    3188
River Rch & RM=Q128-00-00,Q128-00-00_0001 ,6457.308
    3242    3242
River Rch & RM=Q128-00-00,Q128-00-00_0001 ,5820.481
    3362    3362
River Rch & RM=Q128-00-00,Q128-00-00_0001 ,3842.296
    3481    3481
River Rch & RM=Q128-00-00,Q128-00-00_0001 ,1941.131
    3981    3981
River Rch & RM=Q128-00-00,Q128-00-00_0001 ,1714.976
    4007    4007
Boundary for River Rch & Prof#=Q128-00-00,Q128-00-00_0001 , 1
Up Type= 0
Dn Type= 3
Dn Slope=.0011
Boundary for River Rch & Prof#=Q128-00-00,Q128-00-00_0001 , 2
Up Type= 0
Dn Type= 3
Dn Slope=.0011
DSS Import GetInterval= 0
DSS Import GetPeak= 0
DSS Import FillOption= 0

--- Q128-00-00.f01 (steady flow) ---

Flow Title=FEMA Effective June 2007
Version=Version 3.0.1  Mar 2001
Number of Profiles= 4
Profile Names=10PCT_10yr,2PCT_50yr,1PCT_100yr,0.2PCT_500yr
River Rch & RM=Q128-00-00,Q128-00-00_0001 ,32918.38
      33      50      59      86
River Rch & RM=Q128-00-00,Q128-00-00_0001 ,32129.36
      33      51      60      87
River Rch & RM=Q128-00-00,Q128-00-00_0001 ,32103.52
      35      53      63      91
River Rch & RM=Q128-00-00,Q128-00-00_0001 ,31993.03
      55      84      99     143
River Rch & RM=Q128-00-00,Q128-00-00_0001 ,31020.64
      63      95     112     163
River Rch & RM=Q128-00-00,Q128-00-00_0001 ,30746.02
      63      97     114     165
River Rch & RM=Q128-00-00,Q128-00-00_0001 ,30715.94
      65      99     117     170
River Rch & RM=Q128-00-00,Q128-00-00_0001 ,30657.68
      88     134     158     229
River Rch & RM=Q128-00-00,Q128-00-00_0001 ,30011.65
     138     211     248     360
River Rch & RM=Q128-00-00,Q128-00-00_0001 ,29039.45
     217     331     390     565
River Rch & RM=Q128-00-00,Q128-00-00_0001 ,28067.38
     239     364     429     621
River Rch & RM=Q128-00-00,Q128-00-00_0001 ,27862.61
     304     463     546     790
River Rch & RM=Q128-00-00,Q128-00-00_0001 ,27342.48
     331     504     594     860
River Rch & RM=Q128-00-00,Q128-00-00_0001 ,27159.52
     491     748     881    1276
River Rch & RM=Q128-00-00,Q128-00-00_0001 ,26310.80
     498     759     895    1296
River Rch & RM=Q128-00-00,Q128-00-00_0001 ,26159.63
     541     824     971    1406
River Rch & RM=Q128-00-00,Q128-00-00_0001 ,25350.23
     586     894    1053    1525
River Rch & RM=Q128-00-00,Q128-00-00_0001 ,24542.46
     598     911    1073    1555
River Rch & RM=Q128-00-00,Q128-00-00_0001 ,24352.01
     648     987    1163    1684
River Rch & RM=Q128-00-00,Q128-00-00_0001 ,23556.57
     713    1087    1280    1854
River Rch & RM=Q128-00-00,Q128-00-00_0001 ,22602.06
     796    1212    1429    2069
River Rch & RM=Q128-00-00,Q128-00-00_0001 ,21514.76
     835    1272    1499    2171
River Rch & RM=Q128-00-00,Q128-00-00_0001 ,21037.37
     865    1318    1554    2250
River Rch & RM=Q128-00-00,Q128-00-00_0001 ,20683.59
    1439    2192    2582    3736
River Rch & RM=Q128-00-00,Q128-00-00_0001 ,14766.30
    1440    2192    2663    3777
River Rch & RM=Q128-00-00,Q128-00-00_0001 ,14383.70
    1472    2192    2702    3848
River Rch & RM=Q128-00-00,Q128-00-00_0001 ,14079.22
    1533    2238    2776    3985
River Rch & RM=Q128-00-00,Q128-00-00_0001 ,10723.57
    1606    2316    2862    4147
River Rch & RM=Q128-00-00,Q128-00-00_0001 ,8768.922
    1644    2357    2908    4232
River Rch & RM=Q128-00-00,Q128-00-00_0001 ,7774.364
    1802    2523    3089    4578
River Rch & RM=Q128-00-00,Q128-00-00_0001 ,7664.989
    1870    2626    3188    4728
River Rch & RM=Q128-00-00,Q128-00-00_0001 ,6457.308
    1907    2682    3242    4809
River Rch & RM=Q128-00-00,Q128-00-00_0001 ,5820.481
    1989    2807    3362    4990
River Rch & RM=Q128-00-00,Q128-00-00_0001 ,3842.296
    2072    2933    3481    5170
River Rch & RM=Q128-00-00,Q128-00-00_0001 ,1941.131
    2426    3476    3981    5929
River Rch & RM=Q128-00-00,Q128-00-00_0001 ,1714.976
    2444    3504    4007    5968
Boundary for River Rch & Prof#=Q128-00-00,Q128-00-00_0001  , 1
Up Type= 0
Dn Type= 3
Dn Slope=.0011
Boundary for River Rch & Prof#=Q128-00-00,Q128-00-00_0001 , 2
Up Type= 0
Dn Type= 3
Dn Slope=.0011
Boundary for River Rch & Prof#=Q128-00-00,Q128-00-00_0001 , 3
Up Type= 0
Dn Type= 3
Dn Slope=.0011
Boundary for River Rch & Prof#=Q128-00-00,Q128-00-00_0001 , 4
Up Type= 0
Dn Type= 3
Dn Slope=.0011
DSS Import GetInterval= 0
DSS Import GetPeak= 0
DSS Import FillOption= 0

--- Q128-00-00.g05 (geometry) ---

Geom Title=Q128-00-00 June 2007
Version=Version 3.0.1  Mar 2001

River Reach=Q128-00-00            ,Q128-00-00_0001
Reach XY= 30
     3219333.005    13925231.394       3219517.5       13921322.
      3219354.25       13921136.       3219449.5       13919533.
       3220067.5       13919520.      3220340.75       13918753.
      3220423.25       13918680.      3222968.75       13918757.
       3223124.5       13916966.      3224606.75       13915003.
        3226018.       13912941.        3226491.       13912326.
        3226980.       13911515.        3227192.       13911054.
        3227496.       13910636.      3228111.25       13910086.
      3228719.75       13909446.      3229031.25       13909266.
      3229833.25       13909006.      3231462.75       13907497.
     3232183.715    13907482.833     3232310.367    13907157.108
     3233070.783    13906130.025       3233457.5       13905256.
     3233608.283    13904015.441      3233749.95    13903742.525
     3233829.117    13903417.525     3233989.533    13903227.941
       3234243.7    13903094.608       3236876.5       13902374.

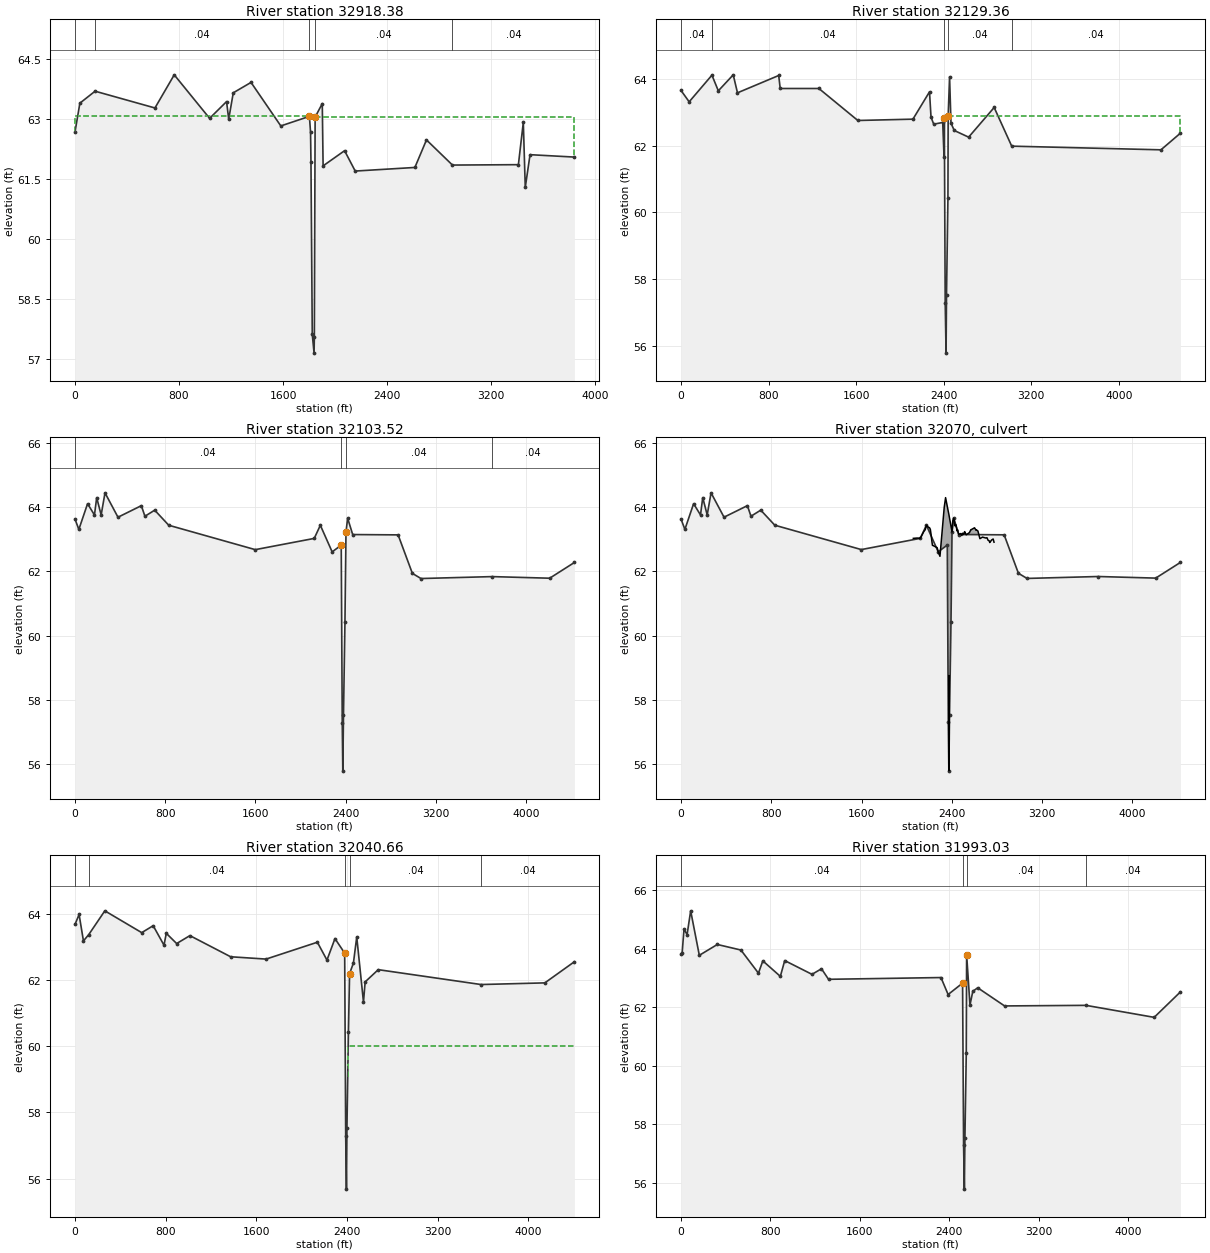
Type RM Length L Ch R = 1 ,32918.38,789.02,789.02,789.02
BEGIN DESCRIPTION:
Section AC - Peters Road
END DESCRIPTION:
XS GIS Cut Line= 5
     3220702.724    13926172.656     3219790.465    13925163.885
     3219392.436    13925137.126     3219286.485    13925128.976
     3217313.029    13925027.173
#Sta/Elev= 30
       0   62.68   37.38    63.4  154.47    63.7  614.91   63.28  763.25   64.11
 1035.35   63.02  1165.8   63.44 1182.26      63 1217.36   63.66 1353.98   63.92
  1583.1   62.83 1803.08   63.07 1811.79   62.67    1815   61.92    1825   57.61
    1839   57.14    1841   57.55    1847   63.05    1902   63.39 1908.33   61.83
 2073.55   62.21 2155.35    61.7 2614.27   61.79 2703.53   62.48  2903.3   61.85
 3410.53   61.86 3448.39   62.92 3463.41   61.29 3500.18   62.11 3841.36   62.05
#Mann= 5 ,-1 , 0
       0     .04       0  154.47     .04       0 1803.08    .045       0
    1847     .04       0  2903.3     .04       0
#XS Ineff= 2 , 0
       0 1803.08   63.07    1847       0   63.05
Permanent Ineff=
       F       F
Bank Sta=1803.08,1847
XS Rating Curve= 0
Exp/Cntr=.3,.1

Type RM Length L Ch R = 1 ,32129.36,25.84,25.84,25.84
XS GIS Cut Line= 6
     3221123.513    13925857.064     3220007.434    13924506.576
       3219605.8    13924372.005     3219401.308    13924348.151
     3219302.257    13924336.722      3217219.52    13924349.234
#Sta/Elev= 30
       0   63.66   74.11   63.32  282.17   64.12  340.55   63.65  476.76   64.13
  515.68   63.59  892.38   64.11  906.15   63.72 1259.68   63.72 1615.63   62.76
 2119.21    62.8 2270.57   63.62 2284.42   62.86    2309   62.65 2391.38    62.7
  2403.5   61.66    2406   62.82    2414   57.29    2422   55.78    2426   57.53
    2439   60.42    2441   62.88 2453.96   64.07 2466.88   62.68 2496.93   62.46
 2628.08   62.26 2861.49   63.15 3021.94   61.99 4385.88   61.88 4563.92   62.38
#Mann= 5 ,-1 , 0
       0     .04       0  282.17     .04       0    2406    .045       0
    2441     .04       0 3021.94     .04       0
#XS Ineff= 2 , 0
       0    2406   62.82    2441       0   62.88
Permanent Ineff=
       F       F
Bank Sta=2406,2441
XS Rating Curve= 0
Exp/Cntr=.5,.3

Type RM Length L Ch R = 1 ,32103.52,62.86,62.86,62.86
XS GIS Cut Line= 6
     3221170.268    13925623.292     3220107.386    13924386.522
     3219578.565    13924342.884     3219404.822    13924321.936
     3219111.631    13924298.524     3217316.541    13924226.639
#Sta/Elev= 30
       0   63.63   33.98   63.31 111.241   64.11  172.43   63.76 192.211    64.3
 231.759   63.76  265.85   64.45 380.921   63.69  588.04   64.05  619.81   63.72
  706.44   63.91  830.97   63.44 1597.99   62.68 2120.74   63.03 2174.76   63.44
 2279.57   62.61    2360   62.82    2369   57.29    2374   55.782379.999   57.53
    2393   60.42 2402.22   63.23 2416.84   63.66 2461.58   63.15 2864.17   63.14
 2990.72   61.94 3067.01   61.783697.511   61.84 4207.92   61.79 4427.02   62.28
#Mann= 4 ,-1 , 0
       0     .04       0    2360    .045       0 2402.22     .04       0
3697.511     .04       0
#XS Ineff= 2 , 0
       0    2360    61.5 2402.22       0    61.5
Permanent Ineff=
       F       F
Bank Sta=2360,2402.22
XS Rating Curve= 0
Exp/Cntr=.5,.3

Type RM Length L Ch R = 2 ,32070   ,,,
BEGIN DESCRIPTION:
1-36" RCP, L=51', 930' DS Peters Rd.
END DESCRIPTION:
Bridge Culvert--1,0,-1,-1, 0
Deck Dist Width WeirC Skew NumUp NumDn MinLoCord MaxHiCord MaxSubmerge Is_Ogee
7,51,2.6,0, 62, 39, , , .95, 0, 0,0,,
 2059.14 2093.35 2117.94  2118.7 2119.62 2120.74 2151.36 2155.69 2164.54 2174.76
 2188.25 2203.06 2209.87 2215.21 2224.98  2228.7 2231.69  2270.3 2279.57 2295.11
 2332.96    2345    2375 2402.22 2408.49 2416.84 2423.11 2428.33 2436.14 2447.58
 2451.19 2461.58 2471.62 2481.27 2489.58 2496.31 2504.12 2511.35 2514.58 2527.77
 2556.47 2569.11 2571.52 2601.45 2601.58  2601.6 2615.59 2617.86  2620.5 2631.66
 2649.23 2673.17 2680.51 2691.71 2702.04 2711.79 2721.73 2732.18 2736.74 2753.31
 2766.77 2774.34
   63.03   63.04   63.03   63.03   63.03   63.03   63.24   63.26    63.3   63.44
   63.39   63.36   63.31   63.18    62.9   62.81   62.81   62.74   62.61   62.47
      64    64.3   63.76   63.23   63.57   63.66   63.57   63.42   63.46   63.26
    63.3   63.15   63.17   63.18   63.12   63.19   63.15   63.22   63.24   63.14
   63.21    63.3    63.3   63.36   63.36   63.36   63.28    63.3   63.29   63.26
   63.02   63.07   63.06   63.05   63.04   63.05   62.97   62.95    62.9   62.98
   63.01   62.91
                                                                                
                                                                                
                                                                                
                                                                                
                                                                                
                                                                                
                
 1964.25 2050.74  2123.5 2137.95 2153.48 2153.57 2153.65 2154.73 2172.17 2185.36
 2191.95 2205.14 2222.73 2242.51 2270.39 2280.48 2285.02  2287.4 2293.31 2334.51
 2345.92    2364    2394    2438 2447.57  2456.1 2471.53 2485.44  2504.3 2518.21
 2544.88 2559.55 2616.04 2675.15 2717.66 2755.95 2788.99 2810.67  2824.9
   62.85   62.91   62.99   63.15   63.11   63.11    63.1   63.09   62.89   62.82
   62.76   62.67   62.61    62.7   62.86   63.09   63.19   63.21   63.26    63.1
      64    64.3   63.76   62.95   62.27   62.52   62.84   63.31   62.76   62.36
   61.34   61.95   62.23   62.32   62.28   62.29    62.3   62.27   62.27
                                                                                
                                                                                
                                                                                
                                                                        
BR Coef=-1 , 0 , 0 ,, 0 ,,,.8,-1,,0,
WSPro=,,,, 1 ,,,, 0 ,,,, 0 ,,,,-1 ,-1 ,-1 , 0 , 0 , 0 , 0 , 0
Culvert=1,3,,51,.013,.2,1,1,3,55.77,2374,55.67,2394,Culvert #1  , 0 ,7
Culvert Bottom n=.013
BC Design=,, 0 ,, 0 ,,,,,,

Type RM Length L Ch R = 1 ,32040.66,47.63,47.63,47.63
XS GIS Cut Line= 6
     3221209.163    13925541.701      3220113.33    13924310.414
     3219408.874    13924261.165     3219329.872    13924249.011
     3219024.449    13924218.288     3217361.651    13924149.308
#Sta/Elev= 30
       0   63.69   35.99   63.99  74.439   63.19   121.1   63.38  263.04    64.1
  588.58   63.44  689.63   63.65  785.12   63.06   805.2   63.42   896.7   63.11
1013.571   63.351373.031   62.711685.502   62.64 2137.95   63.15 2222.73   62.61
2293.311   63.26    2379   62.82    2388   57.29 2394.56   55.68    2399   57.53
    2412   60.42 2422.23    62.22456.102   62.522485.439   63.312544.881   61.34
2559.549   61.952675.151   62.323582.281   61.87 4144.74   61.92 4405.61   62.56
#Mann= 5 ,-1 , 0
       0     .04       0   121.1     .04       0    2379    .045       0
 2422.23     .04       03582.281     .04       0
#XS Ineff= 2 , 0
       0    2382      60    2406       0      60
Permanent Ineff=
       F       F
Bank Sta=2379,2422.23
XS Rating Curve= 0
Exp/Cntr=.5,.3

Type RM Length L Ch R = 1 ,31993.03,972.4,972.4,972.4
BEGIN DESCRIPTION:
Section AB -
END DESCRIPTION:
XS GIS Cut Line= 6
      3221323.75    13925513.426      3220282.05    13924275.292
     3219423.054    13924212.548     3219329.872    13924204.446
     3219103.691    13924177.918     3217436.721    13924084.809
#Sta/Elev= 30
       0   63.81    9.82   63.85   26.23   64.66   54.13   64.48   86.07   65.29
  163.45   63.77  324.61   64.14  535.91   63.95  692.73   63.16  731.93   63.58
  888.76   63.05  927.96   63.59 1171.95   63.12 1257.11   63.31 1320.02   62.95
 2326.57   63.01 2390.59   62.43    2520   62.82    2529   57.29    2536   55.78
    2541   57.53    2553   60.42 2556.25   63.79 2586.17   62.07 2611.61   62.54
 2655.51   62.66  2895.9   62.04 3624.08   62.06 4234.99   61.65 4470.18   62.52
#Mann= 4 ,-1 , 0
       0     .04       0    2520    .045       0 2556.25     .04       0
 3624.08     .04       0
Bank Sta=2520,2556.25
XS Rating Curve= 0
Exp/Cntr=.3,.1

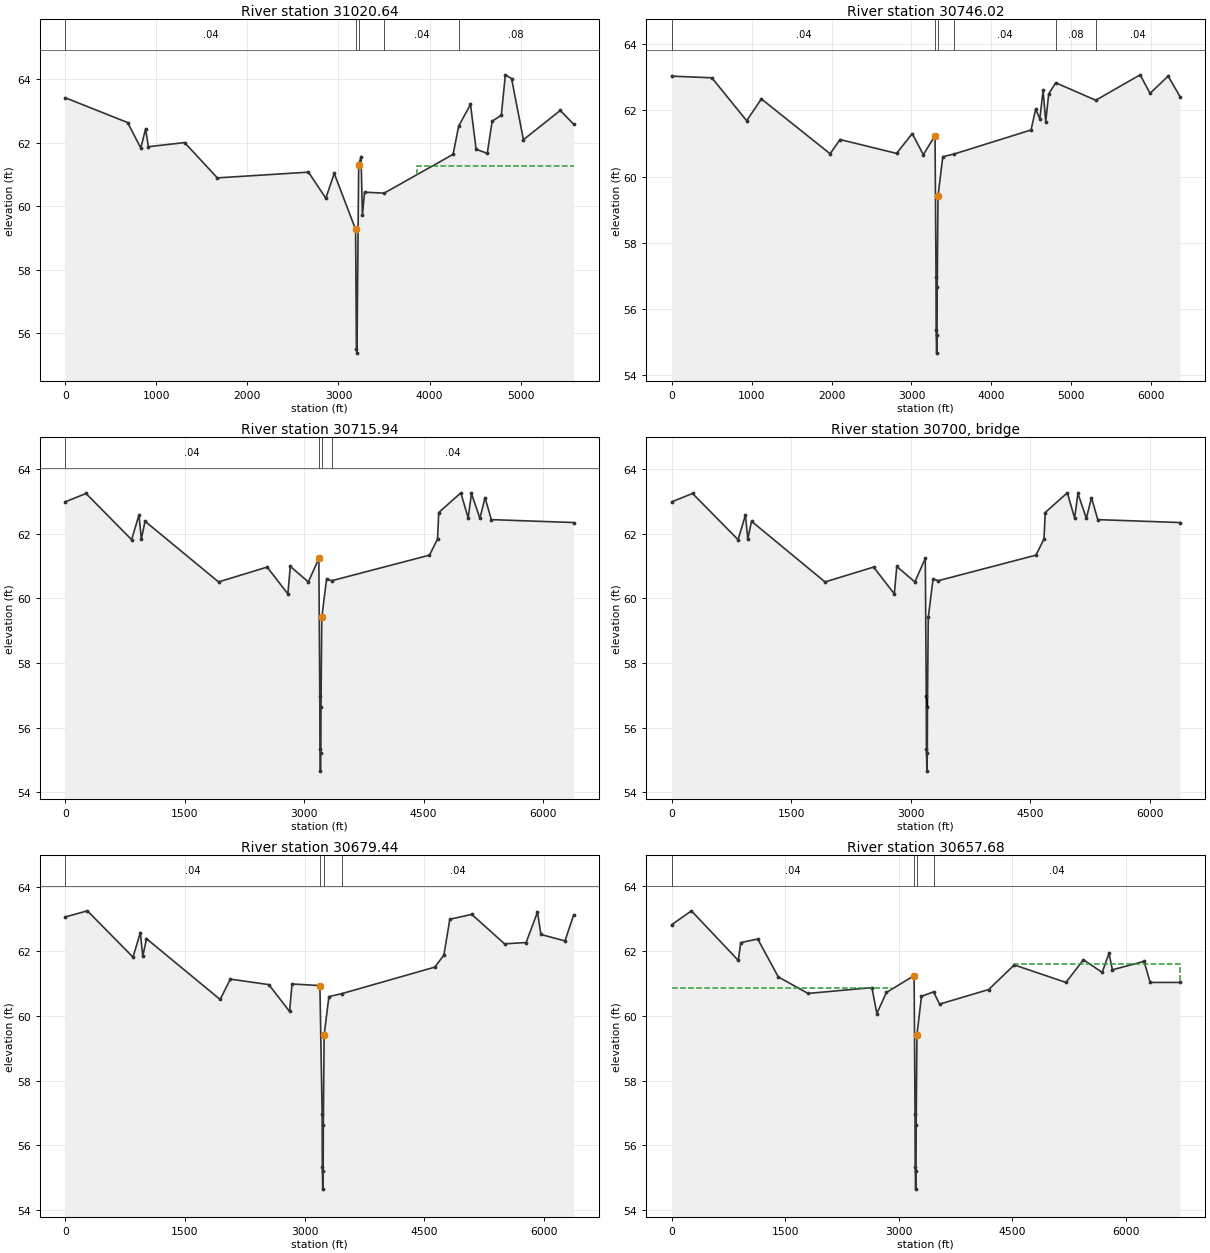
Type RM Length L Ch R = 1 ,31020.64,274.62,274.62,274.62
BEGIN DESCRIPTION:
Section AA -
END DESCRIPTION:
XS GIS Cut Line= 6
     3222563.373    13923830.337     3219690.812    13923261.411
     3219481.799    13923238.187     3219329.872    13923236.162
     3218991.666    13923225.351     3217176.296    13923941.948
#Sta/Elev= 30
       0   63.41  684.74   62.63  829.85   61.83  882.75   62.43  913.34   61.87
 1310.91      62 1670.12   60.89 2670.67   61.07 2861.35   60.25 2953.37   61.03
    3188   59.27    3197   55.51    3203   55.38    3222    61.3 3247.99   61.56
 3262.99   59.71 3286.12   60.44 3501.25   60.41  4258.2   61.63 4319.95   62.52
 4449.42    63.2    4511   61.79 4633.56   61.66 4687.22   62.67 4787.66   62.86
 4832.36   64.13  4900.6   64.01 5030.46   62.09 5435.14   63.01 5580.67   62.58
#Mann= 5 ,-1 , 0
       0     .04       0    3188    .045       0    3222     .08       0
 3501.25     .04       0 4319.95     .08       0
#XS Ineff= 2 , 0
       0 2953.37   61.03 3857.35       0   61.25
Permanent Ineff=
       F       F
Bank Sta=3188,3222
XS Rating Curve= 0
Exp/Cntr=.3,.1

Type RM Length L Ch R = 1 ,30746.02,30.08,30.08,30.08
XS GIS Cut Line= 6
     3222667.543    13923636.878     3219647.278    13922982.886
     3219526.364    13922970.795     3219386.591    13922958.641
      3219051.03    13922934.549     3216625.683    13924053.558
#Sta/Elev= 30
       0   63.04  502.51   62.99   938.2   61.69 1122.37   62.35 1981.84   60.69
 2106.81   61.12  2813.3    60.7 3010.13    61.3  3148.5   60.66    3295   61.24
    3307   56.97    3309   55.34    3315   54.65    3320    55.2    3322   56.64
    3332   59.41    3392    60.6 3532.36   60.68 4495.94   61.41 4553.73   62.04
 4606.07   61.75 4646.74   62.61 4679.78   61.66 4716.56    62.5 4804.37   62.84
 5305.63   62.31 5860.83   63.08 5984.82   62.52 6211.25   63.04 6359.55   62.42
#Mann= 6 ,-1 , 0
       0     .04       0    3295    .045       0    3332     .08       0
 3532.36     .04       0 4804.37     .08       0 5305.63     .04       0
#XS Ineff= 2 , 0
       0 3010.13    61.3               0
Permanent Ineff=
       F       F
Bank Sta=3295,3332
XS Rating Curve= 0
Exp/Cntr=.5,.3

Type RM Length L Ch R = 1 ,30715.94,36.5,36.5,36.5
XS GIS Cut Line= 6
     3222565.839    13923554.783     3219722.857    13922956.615
     3219386.591    13922928.255      3219050.63    13922902.144
     3218059.911    13923114.948     3216391.301    13923758.255
#Sta/Elev= 30
       0   62.99  261.71   63.25  833.36   61.82   925.9   62.58  955.96   61.84
 1002.12   62.39 1925.14   60.51 2535.09   60.97 2795.05   60.14 2825.92   60.99
 3052.56   60.51    3184   61.24    3196   56.97    3198   55.34    3204   54.65
    3209    55.2    3211   56.64    3221   59.41    3281    60.6 3349.26   60.55
 4572.98   61.34 4674.17   61.84 4689.09   62.66 4966.73   63.27  5058.4   62.49
  5100.1   63.25 5205.82   62.48  5270.3   63.12 5349.37   62.44 6381.31   62.35
#Mann= 4 ,-1 , 0
       0     .04       0    3184    .045       0    3221     .08       0
 3349.26     .04       0
#XS Ineff= 2 , 0
       0    3184   61.24    3221       0   59.41
Permanent Ineff=
       F       F
Bank Sta=3184,3221
XS Rating Curve= 0
Exp/Cntr=.5,.3

Type RM Length L Ch R = 3 ,30700   ,,,
BEGIN DESCRIPTION:
1' diameter natural gas pipe line
END DESCRIPTION:
Bridge Culvert--1,0,-1,-1, 0
Deck Dist Width WeirC Skew NumUp NumDn MinLoCord MaxHiCord MaxSubmerge Is_Ogee
17,1,2.6,0, 2, 2, , , .95, 0, 0,0,,
    3196    3212
   56.97   56.64
   55.97   55.64
    3219    3234
   56.97   56.64
   55.97   55.64
BR Coef=-1 , 0 , 0 ,, 0 ,,,.8,-1,,0,
WSPro=,,,, 1 ,,,, 0 ,,,, 0 ,,,,-1 ,-1 ,-1 , 0 , 0 , 0 , 0 , 0
BR U #Sta/Elev= 30
       0   62.99  261.71   63.25  833.36   61.82   925.9   62.58  955.96   61.84
 1002.12   62.39 1925.14   60.51 2535.09   60.97 2795.05   60.14 2825.92   60.99
 3052.56   60.51    3184   61.24    3196   56.97    3198   55.34    3204   54.65
    3209    55.2    3211   56.64    3221   59.41    3281    60.6 3349.26   60.55
 4572.98   61.34 4674.17   61.84 4689.09   62.66 4966.73   63.27  5058.4   62.49
  5100.1   63.25 5205.82   62.48  5270.3   63.12 5349.37   62.44 6381.31   62.35
BR U #Mann= 4
       0     .04    3184    .044    3221     .08 3349.26     .04
BR D #Sta/Elev= 30
       0   63.06  277.71   63.25  849.36   61.82   941.9   62.58  971.96   61.84
 1018.12   62.39 1941.14   60.51 2069.36   61.14 2551.09   60.97 2811.05   60.14
 2841.92   60.99 3191.25   60.94    3219   56.97    3221   55.34    3227   54.65
    3232    55.2    3234   56.64    3244   59.41    3304    60.6 3464.08   60.69
 4629.83   61.51  4744.2   61.88 4818.85   62.99 5093.84   63.14  5504.3   62.23
 5774.59   62.27 5917.33   63.21 5959.83   62.52 6261.51   62.32 6368.82   63.11
BR D #Mann= 4
       0     .04 3191.25    .044    3244     .08 3464.08     .04
BC Design=,, 0 ,, 0 ,,,,,,

Type RM Length L Ch R = 1 ,30679.44,21.76,21.76,21.76
XS GIS Cut Line= 6
     3222579.932    13923531.951     3219652.808     13922918.63
     3219390.643    13922887.741     3219040.051      13922863.2
     3218084.863    13923014.457     3216399.592    13923632.886
#Sta/Elev= 30
       0   63.06  277.71   63.25  849.36   61.82   941.9   62.58  971.96   61.84
 1018.12   62.39 1941.14   60.51 2069.36   61.14 2551.09   60.97 2811.05   60.14
 2841.92   60.99 3191.25   60.94    3219   56.97    3221   55.34    3227   54.65
    3232    55.2    3234   56.64    3244   59.41    3304    60.6 3464.08   60.69
 4629.83   61.51  4744.2   61.88 4818.85   62.99 5093.84   63.14  5504.3   62.23
 5774.59   62.27 5917.33   63.21 5959.83   62.52 6261.51   62.32 6368.82   63.11
#Mann= 4 ,-1 , 0
       0     .04       0 3191.25    .045       0    3244     .08       0
 3464.08     .04       0
#XS Ineff= 2 , 0
       0 2841.92   60.99               0
Permanent Ineff=
       F       F
Bank Sta=3191.25,3244
XS Rating Curve= 0
Exp/Cntr=.5,.3

Type RM Length L Ch R = 1 ,30657.68,646.03,646.03,646.03
XS GIS Cut Line= 6
     3222626.517    13923252.438     3219621.497    13922884.852
     3219421.028    13922873.561      3219031.51    13922834.794
     3216879.789     13922944.97     3215947.324    13923056.391
#Sta/Elev= 30
       0   62.81  260.56   63.24  879.53   61.71  912.87   62.26 1136.43   62.37
 1408.45    61.2 1801.35   60.69 2644.27   60.87 2709.93   60.07 2835.85   60.72
    3202   61.24    3214   56.97    3216   55.34    3222   54.65    3227    55.2
    3229   56.64    3239   59.41    3299    60.6 3458.85   60.74 3538.21   60.36
 4185.95   60.81 4524.38   61.57  5206.8   61.03 5437.79   61.73 5685.38   61.34
  5775.5   61.93 5820.28   61.42 6238.73   61.68 6319.34   61.03 6713.29   61.03
#Mann= 4 ,-1 , 0
       0     .04       0    3202    .045       0    3239     .08       0
 3458.85     .04       0
#XS Ineff= 2 , 0
       0  2900.1   60.85    4519       0    61.6
Permanent Ineff=
       F       F
Bank Sta=3202,3239
XS Rating Curve= 0
Exp/Cntr=.3,.1

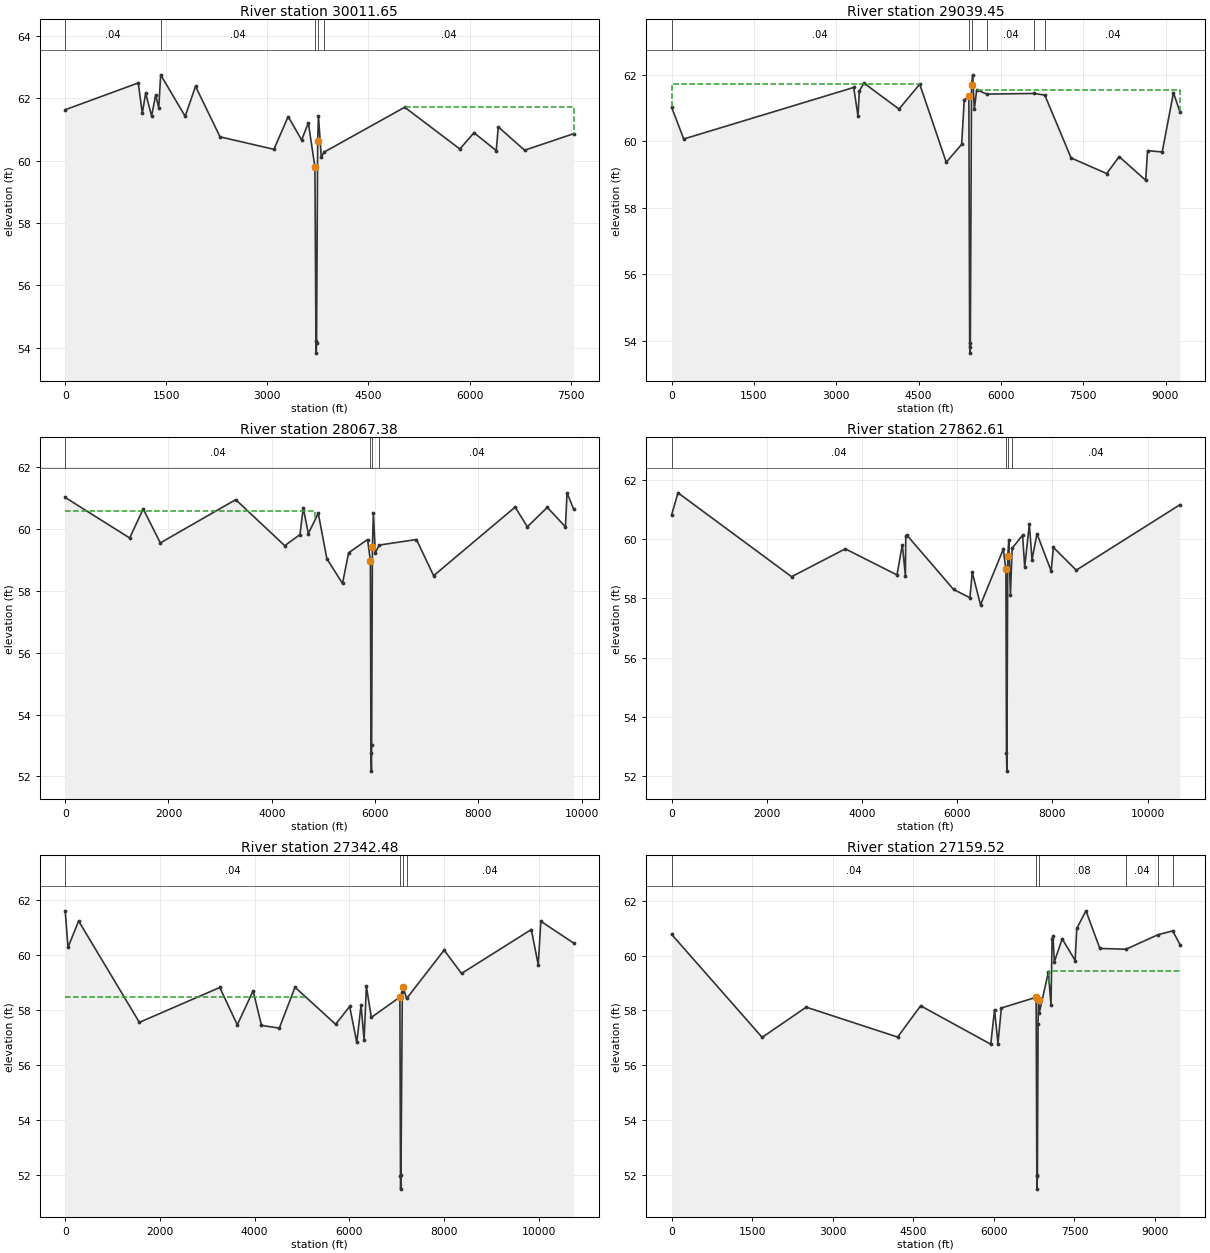
Type RM Length L Ch R = 1 ,30011.65,1100,972.2,900
BEGIN DESCRIPTION:
Section Z -
END DESCRIPTION:
XS GIS Cut Line= 6
     3223138.958    13922813.758     3219848.877    13922250.459
     3219538.519    13922235.466     3219402.797    13922223.312
     3219033.323    13922211.047      3215646.46    13922338.198
#Sta/Elev= 30
       0   61.63 1084.03   62.49 1144.15   61.52 1194.25   62.16 1281.87   61.43
 1342.74    62.1 1388.39   61.69 1416.83   62.75 1780.12   61.42 1934.25   62.38
 2298.15   60.76 3097.21   60.36 3308.87   61.41 3508.46   60.66 3608.48   61.21
    3706   59.79    3721    54.2    3725   53.82    3730   54.16    3747   60.64
    3758   61.44 3800.27   60.11 3842.59   60.27 5038.26   61.71 5856.71   60.37
 6066.81   60.89 6397.05   60.32 6427.07   61.08 6817.34   60.33 7543.87   60.86
#Mann= 5 ,-1 , 0
       0     .04       0 1416.83     .04       0    3706    .045       0
    3747     .08       0 3842.59     .04       0
#XS Ineff= 2 , 0
       0 3308.87   61.41 5038.26       0   61.71
Permanent Ineff=
       F       F
Bank Sta=3706,3747
XS Rating Curve= 0
Exp/Cntr=.3,.1

Type RM Length L Ch R = 1 ,29039.45,900,972.07,1100
BEGIN DESCRIPTION:
Section Y -
END DESCRIPTION:
XS GIS Cut Line= 6
     3224614.164    13922765.232     3219689.324    13921152.844
     3219522.313    13921242.874     3219435.208    13921303.645
     3219259.226    13921423.581     3215709.544    13921831.096
#Sta/Elev= 30
       0   61.02  219.93   60.07 3317.67   61.62 3395.59   60.76 3420.81   61.52
 3504.86   61.75 4143.28   60.97 4520.48   61.72 5004.29   59.37 5284.77   59.91
 5331.77   61.24    5416   61.36    5431   53.82    5439   53.63    5443   53.94
    5465   61.69    5486      62 5515.22   60.96 5559.11   61.55 5743.76   61.42
 6603.08   61.44 6800.17   61.39 7279.13    59.5 7928.37   59.03 8154.84   59.54
    8638   58.83 8673.04   59.72 8939.97   59.68 9144.53   61.46 9263.98   60.88
#Mann= 6 ,-1 , 0
       0     .04       0    5416    .045       0    5465     .08       0
 5743.76     .04       0 6603.08     .08       0 6800.17     .04       0
#XS Ineff= 2 , 0
       0 4520.48   61.72 5559.11       0   61.55
Permanent Ineff=
       F       F
Bank Sta=5416,5465
XS Rating Curve= 0
Exp/Cntr=.3,.1

Type RM Length L Ch R = 1 ,28067.38,204.77,204.77,204.77
XS GIS Cut Line= 6
      3224859.83    13922604.487     3219598.544    13920348.294
     3219477.748    13920353.592     3219331.897    13920355.618
     3218854.639    13920353.913     3215503.307    13920754.413
#Sta/Elev= 30
       0   61.02 1248.02   59.71 1510.38   60.65 1841.64   59.55 3302.04   60.95
 4251.82   59.46 4546.14   59.82 4610.15   60.69 4708.08   59.85 4900.55   60.51
 5067.14   59.04 5369.98   58.24 5487.95   59.23    5855   59.66    5910   58.98
    5921   52.77    5930   52.17    5934   53.01    5949   59.43    5968   60.52
 6004.84   59.23 6080.18   59.48 6802.26   59.66 7134.39   58.49 8713.22   60.71
 8949.33   60.07 9335.22    60.7 9687.64   60.07 9717.85   61.17 9843.86   60.65
#Mann= 4 ,-1 , 0
       0     .04       0    5910    .045       0    5949     .08       0
 6080.18     .04       0
#XS Ineff= 2 , 0
       0 4838.65   60.57               0
Permanent Ineff=
       F       F
Bank Sta=5910,5949
XS Rating Curve= 0
Exp/Cntr=.3,.1

Type RM Length L Ch R = 1 ,27862.61,520.13,520.13,520.13
XS GIS Cut Line= 6
      3225973.73    13922600.168        3219810.    13920148.175
     3219483.825    13920148.996     3219370.386    13920151.022
     3218991.315    13920141.395     3215771.037    13919909.399
#Sta/Elev= 30
       0   60.82  132.65   61.56 2519.66   58.73 3648.32   59.67 4734.17   58.79
  4846.5   59.81 4911.07   58.77 4918.71   60.12 4943.36   60.13 5923.48    58.3
 6267.11   58.02 6315.54   58.88 6489.38   57.78    6968   59.66    7023   58.98
    7035   52.77    7043   52.17    7062   59.43  7083.5   59.97  7118.1   58.12
 7153.59   59.69 7373.18   60.13 7418.19   59.05 7515.31   60.51 7571.42    59.3
 7676.09   60.18 7974.55   58.92 8019.67   59.72 8500.91   58.9510680.99   61.16
#Mann= 4 ,-1 , 0
       0     .04       0    7023    .045       0    7062     .08       0
 7153.59     .04       0
#XS Ineff= 2 , 0
       0 4943.36   60.13 7515.31       0   60.51
Permanent Ineff=
       F       F
Bank Sta=7023,7062
XS Rating Curve= 0
Exp/Cntr=.3,.1

Type RM Length L Ch R = 1 ,27342.48,30,182.96,450
BEGIN DESCRIPTION:
Section X -
END DESCRIPTION:
XS GIS Cut Line= 6
     3226076.311    13922101.921      3219687.56    13919681.601
     3219498.005     13919638.52     3219346.077    13919620.289
     3218884.784    13919617.459     3215786.043    13919556.758
#Sta/Elev= 30
       0   61.62   59.09   60.29  283.66   61.25 1566.88   57.56 3265.69   58.83
 3636.09   57.47 3970.01   58.71 4147.09   57.45 4523.71   57.35 4855.15   58.84
 5713.69   57.49 6010.06   58.14 6160.25   56.83 6250.66   58.19 6314.82   56.93
 6362.94   58.87 6467.87   57.74    7071   58.48    7084   51.98    7087   51.49
    7094   52.01 7122.49   58.68 7132.68   58.86 7214.91   58.43 8005.41   60.19
 8373.76   59.34 9848.29   60.94 9994.31   59.6510048.39   61.2410739.89   60.45
#Mann= 4 ,-1 , 0
       0     .04       0    7071    .045       0 7132.68     .08       0
 7214.91     .04       0
#XS Ineff= 2 , 0
       0 5093.02    58.5               0
Permanent Ineff=
       F       F
Bank Sta=7071,7132.68
XS Rating Curve= 0
Exp/Cntr=.3,.1

Type RM Length L Ch R = 1 ,27159.52,564,848.72,818
XS GIS Cut Line= 6
     3225841.356    13921896.566     3222058.149    13920451.266
     3219524.663    13919586.035     3219526.364    13919458.233
     3219481.185    13919318.958     3217096.121    13918697.847
#Sta/Elev= 30
       0   60.77 1685.03   57.02 2505.18   58.12 4207.31   57.03 4636.42   58.17
 5942.04   56.77 6012.33   58.03 6076.01   56.79 6139.14   58.09    6787   58.48
    6800   51.98    6803   51.49    6810   52.01    6823   57.51 6830.99   58.38
 6843.75    57.9 7015.15    59.4 7063.67    58.2 7083.49   60.59 7101.23   60.72
 7125.67   59.77 7272.11   60.61 7513.18   59.82 7544.18   60.99 7714.68   61.63
 7973.42   60.26  8458.7   60.23 9056.58   60.76 9330.47    60.9 9465.89    60.4
#Mann= 6 ,-1 , 0
       0     .04       0    6787    .045       0 6843.75     .08       0
  8458.7     .04       0 9056.58     .08       0 9330.47     .04       0
#XS Ineff= 2 , 0
       0 4636.42   58.17 7032.67       0   59.42
Permanent Ineff=
       F       F
Bank Sta=6787,6830.99
XS Rating Curve= 0
Exp/Cntr=.3,.1