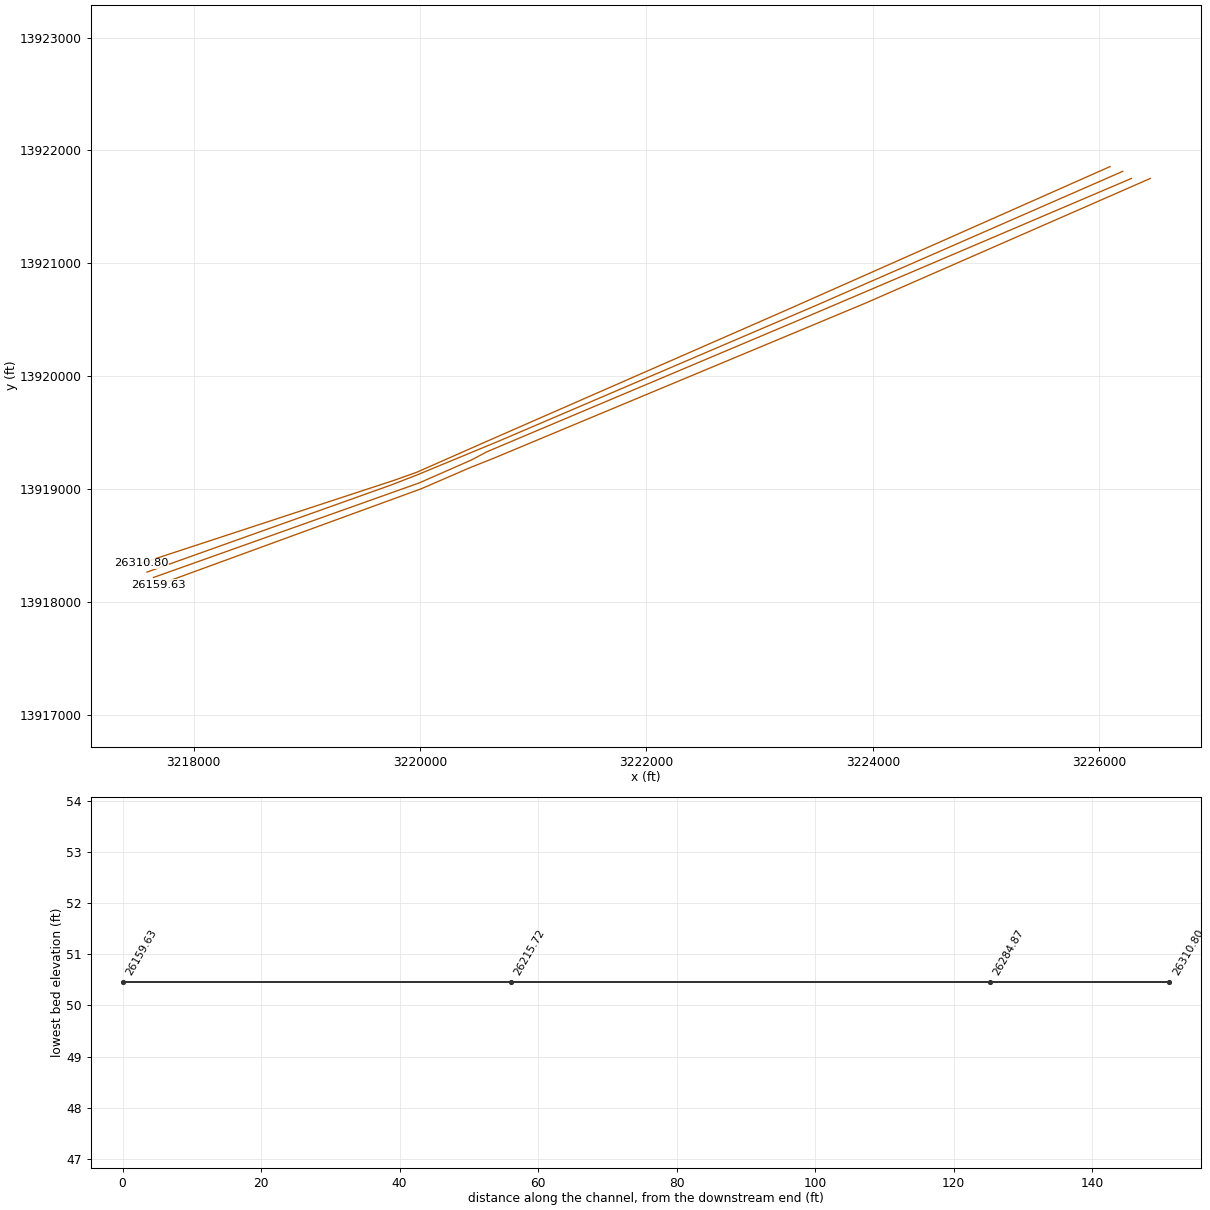
HEC-RAS study Q128-00-00.prj: Q128-00-00

--- Q128-00-00.g05 (geometry) --- (continued)

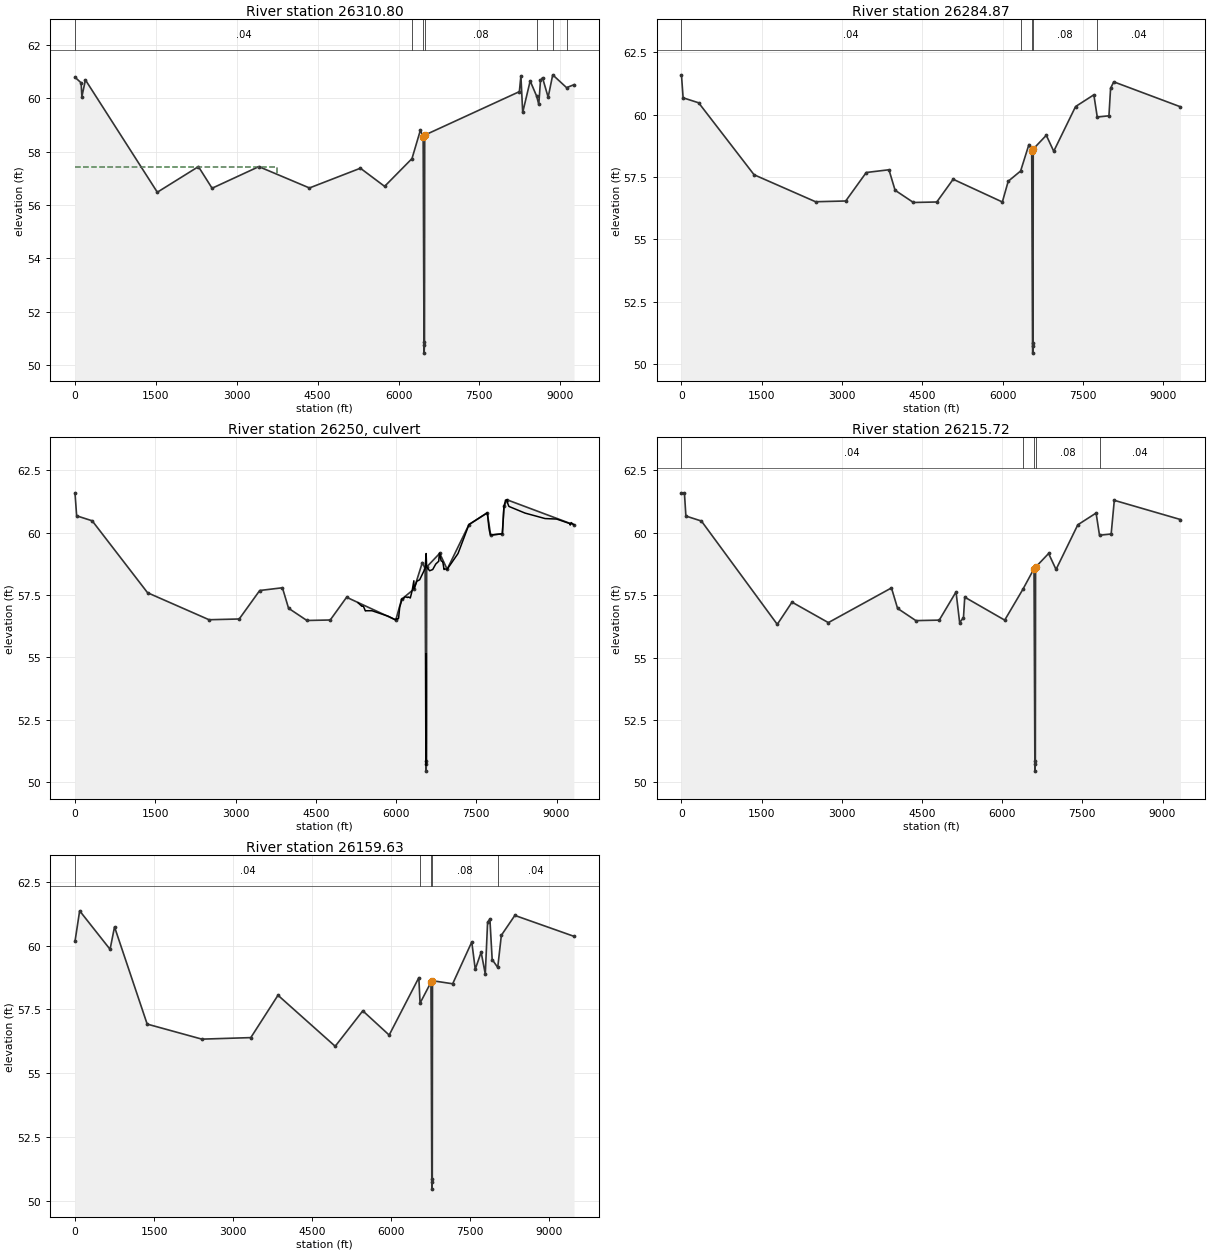
Type RM Length L Ch R = 1 ,26310.80,25.93,25.93,25.93
BEGIN DESCRIPTION:
Section W -
END DESCRIPTION:
XS GIS Cut Line= 6
     3226093.958    13921856.958     3223240.484    13920587.469
     3220585.249    13919420.325     3219971.005    13919148.301
      3219771.46    13919077.213      3217541.68    13918342.918
#Sta/Elev= 30
       0   60.79  113.75   60.58  127.73   60.06   193.4   60.69 1526.96   56.48
 2289.52   57.44 2542.53   56.63 3409.82   57.44 4348.04   56.64 5293.16   57.38
 5742.54    56.7    6250   57.74    6405    58.8    6457   58.56    6473   50.74
    6476   50.45    6482   50.85    6486   58.62 8241.42   60.25  8270.1   60.84
  8303.4   59.47 8442.06   60.65 8562.19   60.08 8601.74   59.77 8633.33   60.67
 8671.03   60.77 8775.46   60.04 8860.08   60.88 9116.88    60.4 9254.76   60.51
#Mann= 7 ,-1 , 0
       0     .04       0    6250     .06       0    6457    .045       0
    6486     .08       0 8562.19     .04       0 8860.08     .08       0
 9116.88     .04       0
#XS Ineff= 2 , 0
       0 3752.48   57.42               0
Permanent Ineff=
       F       F
Bank Sta=6457,6486
XS Rating Curve= 0
Exp/Cntr=.5,.3

Type RM Length L Ch R = 1 ,26284.87,69.15,69.15,69.15
XS GIS Cut Line= 6
     3226206.013    13921814.938      3223506.15    13920630.351
     3220708.505    13919429.691     3219977.082    13919126.018
     3219754.235    13919038.989     3217589.097     13918263.89
#Sta/Elev= 30
       0   61.59   30.89   60.67  321.54   60.47 1356.81   57.59 2505.47   56.51
  3069.3   56.54 3452.61   57.68 3877.01   57.79 3991.48   56.97 4334.06   56.48
 4770.87    56.5 5076.51   57.41 5995.71    56.5 6105.36   57.33    6337   57.74
    6492    58.8    6544   58.56    6560   50.74    6563   50.45    6569   50.85
    6573   58.62 6816.78   59.17 6955.81   58.53 7363.64   60.32 7705.38   60.79
 7769.11    59.9 7987.25   59.95 8018.05   61.05 8076.99   61.31 9323.62   60.31
#Mann= 5 ,-1 , 0
       0     .04       0    6337     .06       0    6544    .045       0
    6573     .08       0 7769.11     .04       0
#XS Ineff= 2 , 0
       0    6523   55.95    6593       0   55.95
Permanent Ineff=
       F       F
Bank Sta=6544,6573
XS Rating Curve= 0
Exp/Cntr=.5,.3

Type RM Length L Ch R = 2 ,26250   ,,,
BEGIN DESCRIPTION:
2-54"RCP, L=26'
END DESCRIPTION:
Bridge Culvert--1,0,-1,-1, 0
Deck Dist Width WeirC Skew NumUp NumDn MinLoCord MaxHiCord MaxSubmerge Is_Ogee
22,26,2.6,0, 86, 86, , , .95, 0, 0,0,,
    5290 5361.19 5362.41 5363.32 5390.26  5427.7 5431.44 5551.36 5855.63 5995.71
 5998.98 6001.69 6008.38 6031.34 6036.25 6047.52 6047.77 6066.63 6068.94 6096.07
 6105.36 6140.92 6151.44  6172.8 6217.81 6222.62 6237.25 6266.63 6288.24 6306.44
 6308.37 6333.74    6337    6389    6442    6544    6563    6573    6573    6629
    6686    6743    6798 6810.88 6816.78  6831.9 6843.09 6873.13 6875.29 6876.68
 6897.85  6907.5 6933.45 6955.81 7158.86 7363.64 7705.38 7712.31 7734.24 7740.88
 7742.99 7762.44 7769.11 7987.25 7992.16 8002.54 8010.72 8018.05 8022.45 8024.02
 8034.18 8039.96 8045.91 8069.38 8071.82 8076.99 8087.75 8107.06 8116.31 8410.28
 8785.71 9001.86 9247.49 9256.01 9272.55 9326.62
   57.19   57.05   57.05   57.06   57.05   56.86   56.87   56.87   56.65    56.5
   56.54   56.54   56.55   56.55   56.54   56.57   56.57   56.96   57.01   57.21
   57.33   57.35   57.39   57.43    57.4   57.41   57.42   57.38   57.56   57.73
   57.76   58.07   57.74   58.05   58.11   58.56   59.16   58.62   58.62   58.47
   58.52   58.74   58.85   59.17   59.17   58.99   58.87   58.83   58.83    58.8
   58.52   58.54   58.54   58.53   59.16   60.32   60.79   60.69   60.23   60.14
    60.1   59.91    59.9   59.95    60.1   60.47   60.79   61.05   61.09    61.1
   61.19   61.23    61.3    61.3   61.27   61.31   61.17   61.06   61.04   60.78
   60.56   60.54   60.36    60.3    60.4   60.31
                                                                                
                                                                                
                                                                                
                                                                                
                                                                                
                                                                                
                                                                                
                                                                                
                                                
    5342 5413.19 5414.41 5415.32 5442.26  5479.7 5483.44 5603.36 5907.63 6047.71
 6050.98 6053.69 6060.38 6083.34 6088.25 6099.52 6099.77 6118.63 6120.94 6148.07
 6157.36 6192.92 6203.44  6224.8 6269.81 6274.62 6289.25 6318.63 6340.24 6358.44
 6360.37 6385.74    6389    6441    6494    6596    6615    6625    6625    6681
    6738    6795    6850 6862.88 6868.78  6883.9 6895.09 6925.13 6927.29 6928.68
 6949.85  6959.5 6985.45 7007.81 7210.86 7415.64 7757.38 7764.31 7786.24 7792.88
 7794.99 7814.44 7821.11 8039.25 8044.16 8054.54 8062.72 8070.05 8074.45 8076.02
 8086.18 8091.96 8097.91 8121.38 8123.82 8128.99 8139.75 8159.06 8168.31 8462.28
 8837.71 9053.86 9299.49 9308.01 9324.55 9378.62
   57.19   57.05   57.05   57.06   57.05   56.86   56.87   56.87   56.65    56.5
   56.54   56.54   56.55   56.55   56.54   56.57   56.57   56.96   57.01   57.21
   57.33   57.35   57.39   57.43    57.4   57.41   57.42   57.38   57.56   57.73
   57.76   58.07   57.74   58.05   58.11   58.56   59.16   58.62   58.62   58.47
   58.52   58.74   58.85   59.17   59.17   58.99   58.87   58.83   58.83    58.8
   58.52   58.54   58.54   58.53   59.16   60.32   60.79   60.69   60.23   60.14
    60.1   59.91    59.9   59.95    60.1   60.47   60.79   61.05   61.09    61.1
   61.19   61.23    61.3    61.3   61.27   61.31   61.17   61.06   61.04   60.78
   60.56   60.54   60.36    60.3    60.4   60.31
                                                                                
                                                                                
                                                                                
                                                                                
                                                                                
                                                                                
                                                                                
                                                                                
                                                
Multiple Barrel Culv=1,4.5,,26,.013,.5,1,1,1,50.67,50.52, 2,Culvert #1  , 0 ,22
    6561    6613    6567    6619
Culvert Bottom n=.013
BC Design=,, 0 ,, 0 ,,,,,,

Type RM Length L Ch R = 1 ,26215.72,56.09,56.09,56.09
XS GIS Cut Line= 6
     3226283.015       13921752.     3223360.579    13920502.585
     3220593.089    13919330.924     3220452.118    13919256.279
     3219995.303    13919054.848     3217647.051    13918216.473
#Sta/Elev= 30
       0   61.59   55.41    61.6   82.89   60.67  373.54   60.47 1792.57   56.33
 2068.24   57.22 2748.23    56.4 3929.01   57.79 4043.48   56.97 4386.06   56.48
 4822.87    56.5 5136.91   57.63 5204.81    56.4 5276.21    56.6 5299.83   57.42
 6047.71    56.5    6389   57.74    6596   58.56    6612   50.74    6615   50.45
    6621   50.85    6625   58.62 6868.78   59.17 7007.81   58.53 7415.64   60.32
 7757.38   60.79 7821.11    59.9 8039.25   59.95 8097.91    61.3 9335.81   60.53
#Mann= 5 ,-1 , 0
       0     .04       0    6389     .06       0    6596    .045       0
    6625     .08       0 7821.11     .04       0
#XS Ineff= 2 , 0
       0    6586    55.4    6635       0    55.4
Permanent Ineff=
       F       F
Bank Sta=6596,6625
XS Rating Curve= 0
Exp/Cntr=.5,.3

Type RM Length L Ch R = 1 ,26159.63,200,809.4,1100
XS GIS Cut Line= 6
     3226450.006       13921752.     3223939.496    13920649.277
     3220638.221    13919267.472     3220455.147    13919194.892
     3220011.519    13919002.451     3217694.469     13918153.25
#Sta/Elev= 30
       0   60.16    88.4   61.36  665.72   59.85  750.18   60.73  1369.6   56.92
 2407.46   56.33 3336.32   56.39 3852.03   58.05 4937.77   56.05 5461.23   57.44
  5961.8   56.49 6524.75   58.74    6548   57.74    6755   58.56    6771   50.74
    6774   50.45    6780   50.85    6784   58.62 7166.97    58.5 7529.39   60.14
 7595.21   59.07 7707.04   59.74 7785.72   58.88 7829.31   60.91  7872.9   61.04
 7916.49   59.45  8021.9   59.14 8090.45    60.4 8346.75   61.18 9469.09   60.36
#Mann= 5 ,-1 , 0
       0     .04       0    6548     .06       0    6755    .045       0
    6784     .08       0  8021.9     .04       0
#XS Ineff= 2 , 0
       0 3852.03   58.05               0
Permanent Ineff=
       F       F
Bank Sta=6755,6784
XS Rating Curve= 0
Exp/Cntr=.3,.1