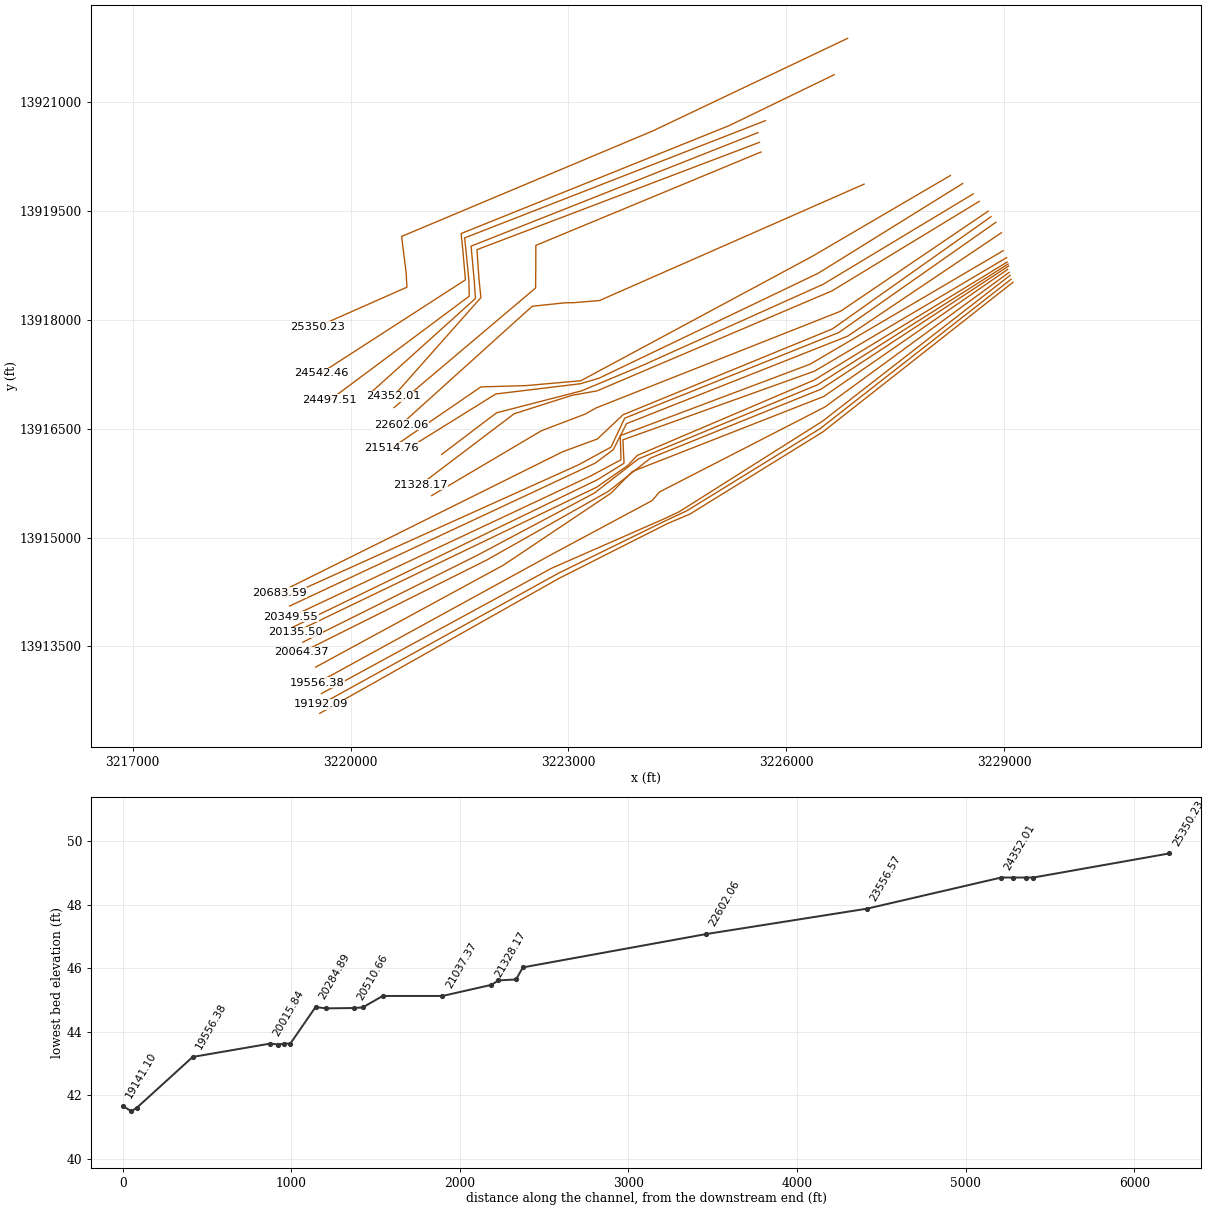
HEC-RAS study Q128-00-00.prj: Q128-00-00

--- Q128-00-00.g05 (geometry) --- (continued)

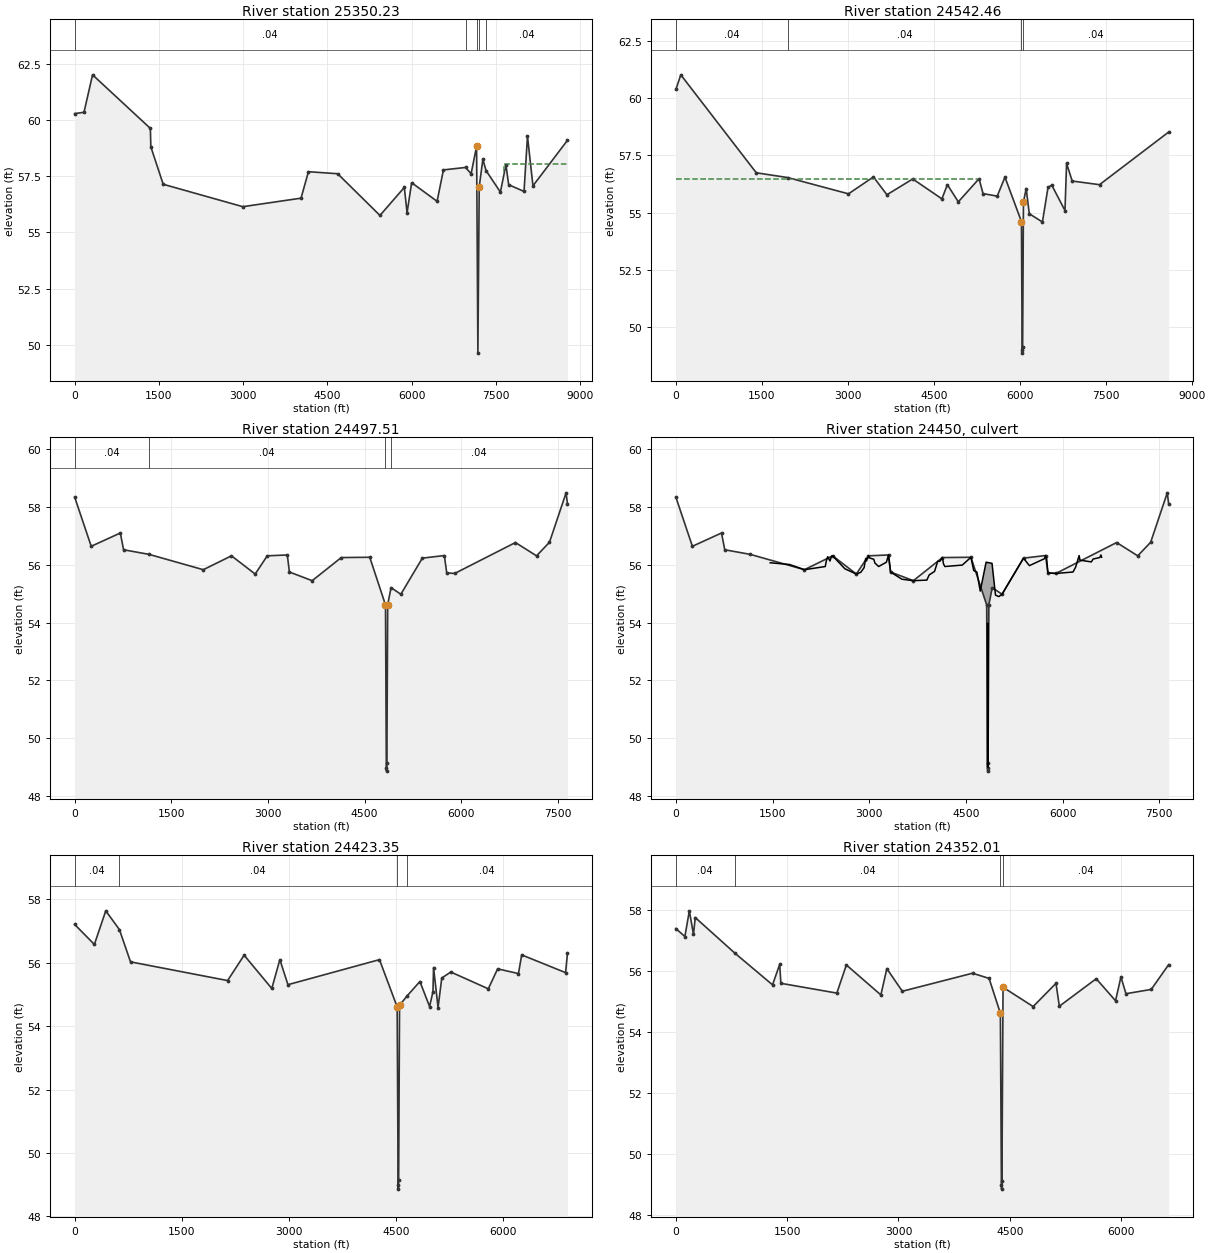
Type RM Length L Ch R = 1 ,25350.23,807.77,807.77,807.77
XS GIS Cut Line= 6
     3226845.511    13921875.046     3224161.608    13920599.604
     3220702.572    13919146.621     3220765.079    13918645.928
     3220775.579    13918447.486     3219539.783    13917901.511
#Sta/Elev= 30
       0    60.3   165.7   60.36  318.51   62.03 1348.18   59.64 1356.43   58.82
 1576.57   57.15 2994.66   56.15 4031.84   56.53 4163.61   57.71 4684.24   57.62
 5437.73   55.76 5871.92   57.01 5920.73   55.88 6002.07   57.22 6455.39   56.39
 6568.39   57.79 6962.38    57.9 7061.23   57.62    7159   58.84    7182   49.62
    7206   57.04 7270.76   58.26 7327.65   57.76 7582.98    56.8 7681.32   58.02
 7730.51   57.13 8003.81   56.83 8065.64   59.29 8163.04   57.08 8777.72   59.11
#Mann= 5 ,-1 , 0
       0     .04       0 6962.38     .06       0    7159    .045       0
    7206     .06       0 7327.65     .04       0
#XS Ineff= 2 , 0
       0 4684.24   57.62 7653.55       0   58.04
Permanent Ineff=
       F       F
Bank Sta=7159,7206
XS Rating Curve= 0
Exp/Cntr=.3,.1

Type RM Length L Ch R = 1 ,24542.46,44.95,44.95,44.95
BEGIN DESCRIPTION:
Section V -
END DESCRIPTION:
XS GIS Cut Line= 6
     3226660.942    13921374.073     3225213.577    13920672.735
     3221521.996      13919186.3     3221544.973    13918968.014
     3221581.436    13918548.694     3219591.234    13917263.521
#Sta/Elev= 30
       0   60.38   86.19   61.02 1402.98   56.74 1953.02   56.53 3011.71   55.82
 3447.14   56.56 3681.84   55.78 4132.76   56.47 4641.71    55.6 4736.66   56.22
 4927.89   55.47 5289.32   56.48 5359.31   55.83 5606.94   55.72 5741.26   56.55
    6029   54.61    6042   48.98    6045   48.86    6050   49.14    6064   55.46
    6112   56.05    6166   54.95 6395.15   54.59 6492.85    56.1 6557.98    56.2
 6788.85   55.09  6816.5   57.15 6915.09   56.38 7391.01   56.22 8597.42   58.52
#Mann= 4 ,-1 , 0
       0     .04       0 1953.02     .04       0    6029    .045       0
    6064     .04       0
#XS Ineff= 2 , 0
       0  5291.4   56.48 6557.98       0    56.2
Permanent Ineff=
       F       F
Bank Sta=6029,6064
XS Rating Curve= 0
Exp/Cntr=.5,.3

Type RM Length L Ch R = 1 ,24497.51,74.16,74.16,74.16
XS GIS Cut Line= 6
     3225713.882    13920741.597     3221570.498    13919126.423
     3221585.994    13918982.194      3221629.04    13918544.136
     3221634.048    13918323.764     3219714.716    13916893.075
#Sta/Elev= 30
       0   58.34  256.54   56.64  708.22    57.1  758.84   56.52 1154.66   56.36
 1995.52   55.83 2433.12   56.31 2800.49   55.68 2988.29   56.31 3299.57   56.34
 3331.77   55.75 3685.26   55.45 4136.74   56.25 4578.45   56.26    4823   54.61
    4836   48.98    4839   48.86    4844   49.14 4857.12   54.62 4909.32   55.21
    5061   54.98 5394.46   56.23 5736.27   56.32 5773.08   55.72  5896.7    55.7
 6839.47   56.77 7166.88   56.31 7367.68   56.78 7625.24   58.49 7646.61   58.11
#Mann= 4 ,-1 , 0
       0     .04       0 1154.66     .04       0    4823    .045       0
 4909.32     .04       0
#XS Ineff= 2 , 0
       0 4136.74    54.9 5394.46       0    54.9
Permanent Ineff=
       F       F
Bank Sta=4823,4857.12
XS Rating Curve= 0
Exp/Cntr=.5,.3

Type RM Length L Ch R = 2 ,24450   ,,,
BEGIN DESCRIPTION:
2=60" RCP, L=36'
END DESCRIPTION:
Bridge Culvert--1,0,-1,-1, 0
Deck Dist Width WeirC Skew NumUp NumDn MinLoCord MaxHiCord MaxSubmerge Is_Ogee
19,36,2.6,0, 59, 60, , , .95, 0, 0,0,,
  1464.1 1764.44 1995.52 2318.37 2334.01 2356.75 2391.22 2418.36 2433.12 2623.39
 2800.49 2869.61 2920.73 2945.38 2957.99 2988.29 3001.54 3071.31 3088.53 3146.58
 3267.37 3299.57 3331.77 3507.45 3685.26 3894.38 3931.27 4013.87 4063.08 4096.47
 4136.74 4152.84  4174.4 4444.77 4578.45    4622    4671    4723    4814    4906
    4960    5012    5061 5394.46 5485.28 5718.74 5736.27 5754.37 5773.08  5896.7
 6162.95 6203.38 6257.23 6271.16 6446.59 6475.52 6576.83 6595.99 6606.56
   56.07   56.01   55.83   55.94   56.13   56.28   56.13   56.31   56.31   55.86
   55.68   55.74    55.9   56.22   56.13   56.31   56.24   56.19   56.06   55.94
   56.09   56.34   55.75    55.5   55.45   55.47   55.65   55.77   56.12   56.12
   56.25   56.03   55.94   55.99   56.26    55.8   55.75   55.09   56.09   56.05
   54.95    54.9   54.98   56.23   55.97   56.21   56.32    56.2   55.72    55.7
   55.75   55.92   56.32   56.16    56.1    56.2   56.25   56.34   56.26
                                                                                
                                                                                
                                                                                
                                                                                
                                                                                
                                                                        
 1026.38  1790.1 1977.87 2139.72 2241.81 2370.84 2419.27 2661.25 2758.05 2870.97
 2951.63  2983.9  3097.5 3161.36 3193.62 3318.54 3371.08 3566.49 3623.28 3684.69
 3919.43 4021.66 4104.46 4171.63 4264.73 4291.27    4360    4413    4504    4554
    4596    4649 4830.63 4875.67 4965.87  5013.3 5021.32 5043.75 5052.77 5084.63
 5136.35 5243.95  5262.7 5297.06 5357.64 5380.06 5423.53 5468.33 5514.59  5556.6
  5626.7 5731.35 5787.42 5918.18 5963.02 6119.97 6173.12 6209.65 6254.49 6356.87
   55.87   55.62   55.94   55.44   56.11   56.24   55.87   55.62   55.19    56.1
   55.87   55.31   55.58   55.37    55.7   55.35   55.71   55.37   55.65   55.32
   55.81   55.58   56.13   55.85    56.1   55.77   55.75   55.09   56.09   56.09
   56.05   54.95   55.41   54.85   54.62   55.09   55.85   55.79   55.13   54.59
   55.52   55.33   55.71   55.26   55.51   55.22   55.51   55.26   55.59   55.36
   55.74   55.65   55.18   55.81   55.29   55.53   55.94   55.66   56.25   55.85
                                                                                
                                                                                
                                                                                
                                                                                
                                                                                
                                                                                
Multiple Barrel Culv=1,5,,36,.013,.2,1,1,3,48.99,48.86, 2,Culvert #1  , 0 ,19
    4836    4526    4842    4532
Culvert Bottom n=.013
BC Design=,, 0 ,, 0 ,,,,,,

Type RM Length L Ch R = 1 ,24423.35,71.34,71.34,71.34
XS GIS Cut Line= 5
      3225610.98    13920576.954     3221659.557    13919012.849
     3221702.471    13918539.072     3221719.881    13918292.438
     3220290.965    13917006.267
#Sta/Elev= 30
       0   57.21  275.47   56.58  434.92   57.64  625.64   57.05  781.26   56.03
 2139.72   55.44 2370.84   56.24 2758.05   55.19 2870.97    56.1  2983.9   55.31
 4264.73    56.1    4512   54.61    4526   48.98    4529   48.86    4533   49.14
 4545.68   54.66    4649   54.95 4830.63   55.41 4965.87   54.62  5013.3   55.09
 5021.32   55.85 5084.63   54.59 5136.35   55.52  5262.7   55.71 5787.42   55.18
 5918.18   55.81 6209.65   55.66 6254.49   56.25    6869   55.69 6895.19    56.3
#Mann= 4 ,-1 , 0
       0     .04       0  625.64     .04       0    4512    .045       0
    4649     .04       0
#XS Ineff= 2 , 0
       0 4104.46    54.9 5021.32       0    54.9
Permanent Ineff=
       F       F
Bank Sta=4512,4545.68
XS Rating Curve= 0
Exp/Cntr=.5,.3

Type RM Length L Ch R = 1 ,24352.01,795.44,795.44,795.44
XS GIS Cut Line= 5
     3225631.561    13920443.182     3221740.453    13918964.469
     3221768.307    13918559.329     3221794.769    13918304.412
      3220589.38    13916944.526
#Sta/Elev= 30
       0   57.38  121.74   57.12  181.82   57.96  237.29   57.19  261.42   57.74
  793.43   56.58 1303.24   55.54 1399.52   56.21 1415.56   55.59 2169.76   55.27
 2298.13   56.19 2763.48   55.21 2843.71   56.07 3052.32   55.33 3999.07   55.92
    4222   55.75    4374   54.61    4388   48.98    4391   48.86    4395   49.14
    4410   55.46 4815.85   54.83 5123.81   55.59 5168.59   54.84 5666.09   55.74
 5926.38   55.02 5999.22    55.8 6066.69   55.25 6407.44   55.39  6642.2    56.2
#Mann= 4 ,-1 , 0
       0     .04       0  793.43     .04       0    4374    .045       0
    4410     .04       0
#XS Ineff= 2 , 0
       0 2843.71   56.07 5123.81       0   55.59
Permanent Ineff=
       F       F
Bank Sta=4374,4410
XS Rating Curve= 0
Exp/Cntr=.3,.1

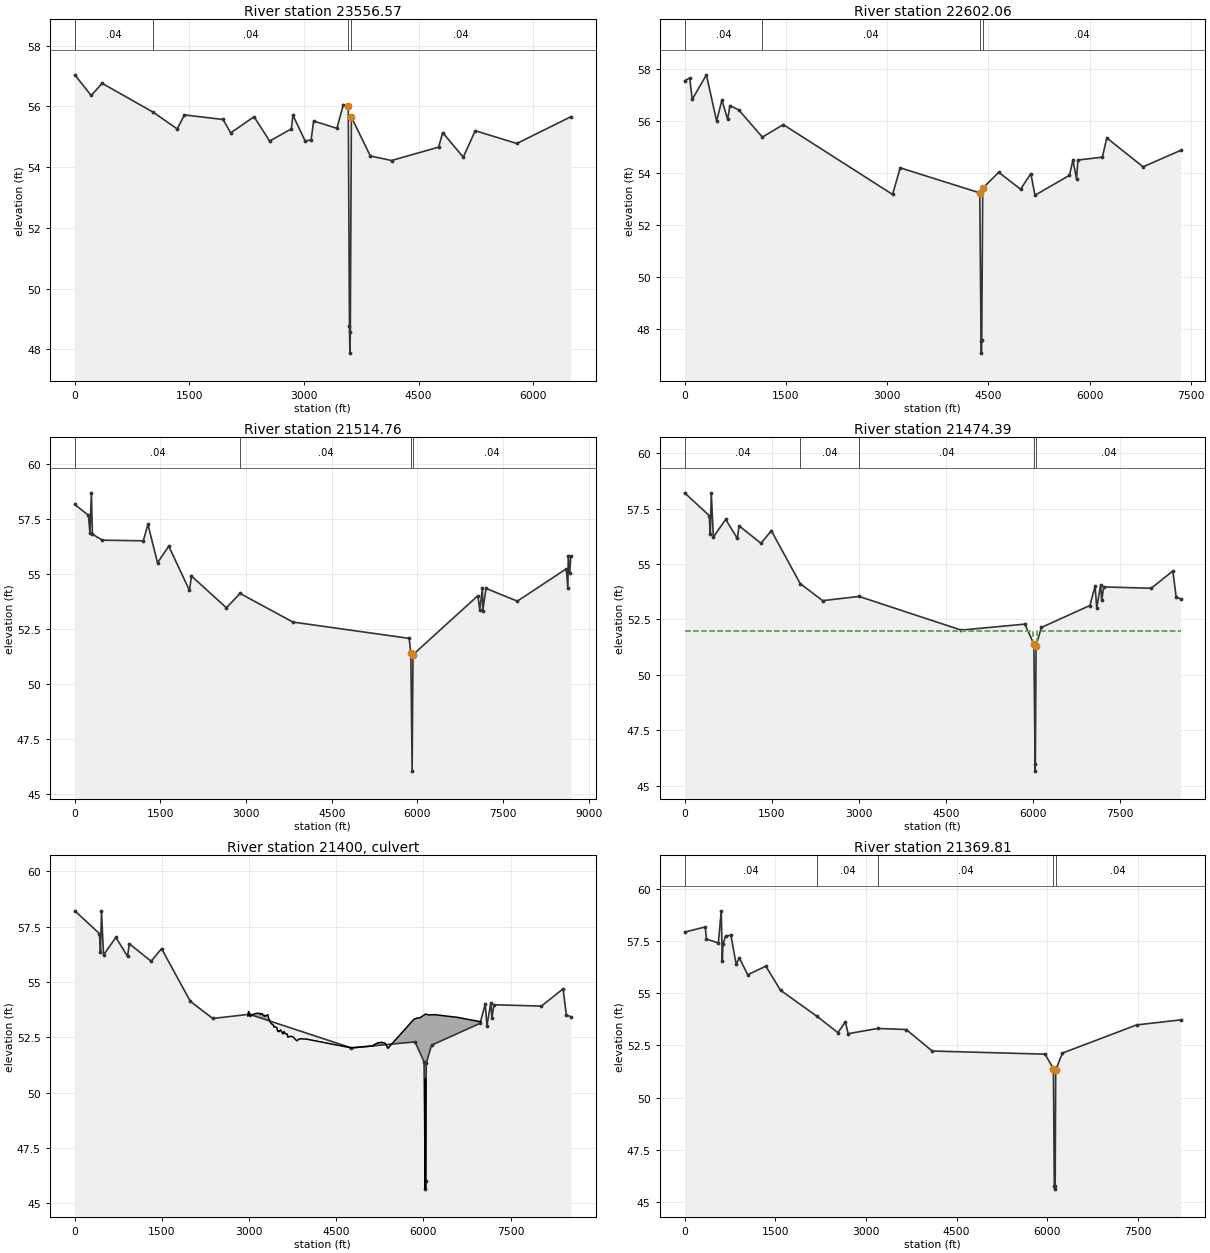
Type RM Length L Ch R = 1 ,23556.57,1500,954.51,250
BEGIN DESCRIPTION:
Section U -
END DESCRIPTION:
XS GIS Cut Line= 6
     3225652.141     13920309.41     3222551.494    13919023.157
     3222550.733    13918880.909     3222550.733    13918734.046
     3222547.787    13918436.466      3220599.67    13916790.174
#Sta/Elev= 30
       0   57.04  213.54   56.36  357.86   56.76 1025.68   55.81 1340.02   55.26
 1435.33   55.72 1940.88   55.57 2040.65   55.13 2346.87   55.66 2550.77   54.86
 2834.05   55.26 2855.81   55.71 3016.28   54.86 3093.88    54.9 3126.36   55.52
 3431.39   55.28 3515.98   56.06 3580.05      56    3596   48.77    3602   47.88
    3607   48.59    3621   55.65 3868.92   54.37 4146.33   54.22 4763.68   54.66
 4816.15   55.14 5085.84   54.33 5242.65    55.2 5787.68   54.78 6494.14   55.66
#Mann= 4 ,-1 , 0
       0     .04       0 1025.68     .04       0 3580.05    .045       0
    3621     .04       0
#XS Ineff= 2 , 0
       0 2855.81   55.71 4816.15       0   55.14
Permanent Ineff=
       F       F
Bank Sta=3580.05,3621
XS Rating Curve= 0
Exp/Cntr=.3,.1

Type RM Length L Ch R = 1 ,22602.06,1087.3,1087.3,1087.3
BEGIN DESCRIPTION:
Section T -
END DESCRIPTION:
XS GIS Cut Line= 6
     3227072.184    13919866.933     3223430.103    13918264.431
     3223085.011    13918235.217     3222953.341    13918232.685
     3222501.665     13918185.04     3220692.282      13916553.5
#Sta/Elev= 30
       0   57.53   74.02   57.64  113.04   56.82  322.52   57.76  473.57   55.99
  552.22   56.79  637.45   56.05  670.23   56.58  803.19   56.41 1151.76   55.37
 1460.94   55.85 3080.11   53.17 3193.94   54.19    4372   53.23    4391   47.54
    4396   47.08    4401   47.58    4416   53.41  4652.9   54.02 4977.06   53.37
 5128.66   53.97 5189.92   53.14 5699.72    53.9 5752.82   54.48    5806   53.77
  5826.2   54.49 6188.27    54.6 6253.82   55.34  6791.4   54.23 7347.59   54.86
#Mann= 4 ,-1 , 0
       0     .04       0 1151.76     .04       0    4372    .045       0
    4416     .04       0
#XS Ineff= 2 , 0
       0 3193.94   54.19 5128.66       0   53.97
Permanent Ineff=
       F       F
Bank Sta=4372,4416
XS Rating Curve= 0
Exp/Cntr=.3,.1

Type RM Length L Ch R = 1 ,21514.76,104,40.37,40.37
BEGIN DESCRIPTION:
Section S -
END DESCRIPTION:
XS GIS Cut Line= 6
     3228260.788    13919985.967     3226356.551    13918871.519
     3223171.103    13917159.065     3222421.524    13917092.558
     3221793.756    13917074.079       3220568.8    13916234.505
#Sta/Elev= 30
       0   58.14  237.89   57.65  264.11   56.84  290.03   58.67  307.75   56.79
  483.38   56.52 1199.53   56.49 1280.69   57.24 1448.18   55.49 1645.27   56.25
 2007.66   54.24 2043.58   54.89 2654.81   53.45 2894.72    54.1 3820.75    52.8
    5857   52.06    5886   51.39    5909   46.03    5924   51.32 7061.32      54
 7094.36   53.36 7140.75   54.35 7147.04   53.32 7202.59   54.33 7751.77   53.75
 8610.62   55.22 8636.88   54.33 8643.76   55.79  8670.3   55.03 8688.75   55.81
#Mann= 4 ,-1 , 0
       0     .04       0 2894.72     .04       0    5886    .045       0
    5924     .04       0
Bank Sta=5886,5924
XS Rating Curve= 0
Exp/Cntr=.5,.3

Type RM Length L Ch R = 1 ,21474.39,67,104.58,111
XS GIS Cut Line= 6
     3228430.263    13919875.808     3226442.043    13918640.615
     3223419.463    13917193.129     3223164.773    13917117.918
     3222000.129    13916976.764     3220805.473    13916234.505
#Sta/Elev= 30
       0   58.22  423.56   57.19  441.22   56.34  458.88   58.19   494.2   56.22
  706.11   57.02   907.1   56.16  937.21   56.73 1313.89   55.94 1492.28   56.51
    1989   54.12 2375.02   53.35 3002.27   53.54 4759.43   52.02 5856.37   52.29
    6011   51.39 6033.62   45.65 6036.66   45.98    6049   51.32 6140.25   52.14
 6974.88   53.13 7065.11      54 7093.53   53.03 7161.03   54.06 7178.69   53.37
 7214.01   53.97 8031.48   53.91 8403.76   54.69 8460.61   53.51 8537.22   53.43
#Mann= 5 ,-1 , 0
       0     .04       0    1989     .04       0 3002.27     .04       0
    6011    .045       0    6049     .04       0
#XS Ineff= 2 , 0
       0    6001      52    6059       0      52
Permanent Ineff=
       F       F
Bank Sta=6011,6049
XS Rating Curve= 0
Exp/Cntr=.5,.3

Type RM Length L Ch R = 2 ,21400   ,,,
BEGIN DESCRIPTION:
2-60" RCP, L=39"
END DESCRIPTION:
Bridge Culvert--1,0,-1,-1, 0
Deck Dist Width WeirC Skew NumUp NumDn MinLoCord MaxHiCord MaxSubmerge Is_Ogee
33,39,2.6,0, 65, 154, , , .95, 0, 0,0,,
 2978.23 2990.59 3002.27 3022.27 3031.96 3058.07 3112.36 3113.51 3120.16  3177.6
 3187.55 3196.96 3222.58 3247.71 3262.61 3268.11 3293.39 3322.75 3335.15  3361.5
  3362.4  3384.2 3402.39 3422.37 3428.93 3444.85 3477.64 3485.41 3499.16  3507.9
 3514.54 3543.13 3555.88 3578.61 3588.95 3597.87  3628.5 3638.07 3657.19 3665.34
 3683.88 3735.13 3761.55 3820.08 3868.85 3979.99 4759.43  5140.5 5141.96 5225.11
 5228.51 5275.01 5289.71 5330.21 5349.17    5389    5835    5890    5939    6036
    6090    6145    6203    6589    6989
   53.46   53.67   53.54   53.43   53.47   53.53   53.57   53.57   53.58   53.58
   53.58   53.53   53.57   53.47    53.5   53.45   53.48   53.52   53.36    53.2
   53.19   53.11   53.08   53.03   52.96   52.97   52.94   52.82   52.76   52.79
   52.75   52.83   52.77   52.66   52.66   52.76   52.65   52.65   52.64    52.5
   52.53   52.54    52.5   52.34   52.43   52.42   52.02   52.11   52.15   52.26
   52.25   52.27   52.26   52.25    52.2      52   53.31   53.37   53.38   53.55
   53.51   53.52   53.52    53.4    53.2
                                                                                
                                                                                
                                                                                
                                                                                
                                                                                
                                                                                
                                        
 3167.31 3195.29 3210.79 3217.19 3238.61 3240.65 3243.18 3269.63 3286.39 3291.27
 3307.37 3307.71 3307.88 3319.19 3338.44 3364.32 3388.36 3418.45 3439.25 3463.85
 3475.22  3502.5 3505.02 3509.02 3521.47 3534.79  3570.8 3576.31 3602.46 3623.35
 3637.71 3665.32 3683.01 3702.34 3720.54 3747.57  3750.4    3755 3784.55 3797.51
 3804.63  3845.7 3861.41 3863.87 3866.76 3878.48 3904.22 3916.09 3921.96 3951.36
 3967.29 3977.35 3981.86 3992.29 4008.57 4022.74 4031.19 4096.96 4113.77 4136.21
 4146.29 4147.56 4150.39  4173.9 4187.51 4195.62  4204.3 4232.48 4244.95 4249.69
 4268.67 4304.13 4310.72 4313.02 4319.88 4333.48 4338.82  4343.6 4347.93 4364.72
 4388.75 4397.21 4416.29 4438.29 4447.61  4462.6 4483.81 4519.42  4553.2 4567.42
 4579.77  4688.9 4690.88 4719.23 4721.79 4724.45 4728.65 4754.67 4760.33 4771.11
 4772.92 4787.56 4794.37    4804 4828.41 4849.21 4853.33  4866.7 4873.93 4918.48
 4919.01 4919.13 4919.19 4951.98  4954.3 5001.31 5009.97 5019.86 5021.32 5029.26
 5044.01 5056.83 5067.08 5078.06 5083.53  5089.4 5094.41 5134.79  5149.3 5157.49
 5342.37 5347.99 5361.82 5365.39 5374.34 5378.07 5400.74 5442.91 5443.04 5443.11
 5443.32 5549.52 5564.15    5590    6036    6091    6140    6237    6291    6346
    6404    6790    7190  7242.5
   53.24   53.31   53.36   53.32    53.2   53.22   53.19    53.3   53.46   53.44
   53.48   53.49   53.48   53.23   53.22   53.21   53.17   53.26    53.3   53.19
   53.11   53.22    53.2   53.26   53.21   53.24   53.19   53.15   53.16   53.28
   53.29   53.26   53.15   52.97   52.98   53.01      53   52.98   52.73   52.79
   52.81   52.58    52.5    52.5   52.48   52.58   52.57   52.53   52.54   52.48
   52.43   52.36   52.33   52.28   52.35   52.29   52.32   52.23   52.25   52.24
   52.02   51.99   51.98   52.05   52.01   52.03   52.14   52.17   52.19   52.16
   52.36   52.32    52.3   52.32   52.33   52.32   52.31   52.33   52.33   52.44
   52.31   52.38   52.39   52.29   52.36   52.45   52.42    52.5   52.47   52.44
    52.5   52.52   52.51   52.46   52.45   52.46   52.43   52.47   52.49   52.35
   52.34   52.38   52.39   52.29   52.29    52.4    52.4   52.29   52.28   52.35
   52.35   52.35   52.35   52.37   52.35   52.07   52.26   52.03   52.06   52.04
   52.11   52.17   52.07   52.11   52.07   52.02   52.04   52.05   51.88      52
   52.04   52.04   51.91   51.94   52.02   52.04   52.04   51.96   51.96   51.96
   51.97   51.95   51.95      52   53.31   53.37   53.38   53.55   53.51   53.52
   53.52    53.4    53.2   53.18
                                                                                
                                                                                
                                                                                
                                                                                
                                                                                
                                                                                
                                                                                
                                                                                
                                                                                
                                                                                
                                                                                
                                                                                
                                                                                
                                                                                
                                                                                
                                
Multiple Barrel Culv=1,5,,39,.013,.5,1,1,1,45.63,45.6, 2,Culvert #1  , 0 ,33
    6031    6122    6038    6129
Culvert Bottom n=.013
BC Design=,, 0 ,, 0 ,,,,,,

Type RM Length L Ch R = 1 ,21369.81,125,41.64,41
XS GIS Cut Line= 6
     3228574.317    13919731.754     3226506.497    13918486.611
     3224012.712    13917366.867     3223180.599    13917019.798
     3222008.929    13916717.106     3221253.974    13916144.224
#Sta/Elev= 30
       0   57.92   340.7   58.17  360.78   57.59  557.85    57.4  605.64   58.94
  623.15   56.55  634.35   57.34  677.15   57.73  765.49   57.77   852.1   56.39
  905.93   56.68 1043.38   55.88  1343.3   56.29 1586.17   55.14    2190   53.89
 2535.68   53.11  2659.4   53.62 2706.42   53.06 3195.29   53.31 3665.32   53.26
 4096.96   52.23 5961.86   52.08    6102   51.39 6117.33   45.76  6122.9   45.62
  6131.2   45.78    6140   51.32 6250.53   52.13 7479.63   53.48 8207.16   53.72
#Mann= 5 ,-1 , 0
       0     .04       0    2190     .04       0 3195.29     .04       0
    6102    .045       0    6140     .04       0
#XS Ineff= 2 , 0
       0    6092      51    6150       0      51
Permanent Ineff=
       F       F
Bank Sta=6102,6140
XS Rating Curve= 0
Exp/Cntr=.5,.3

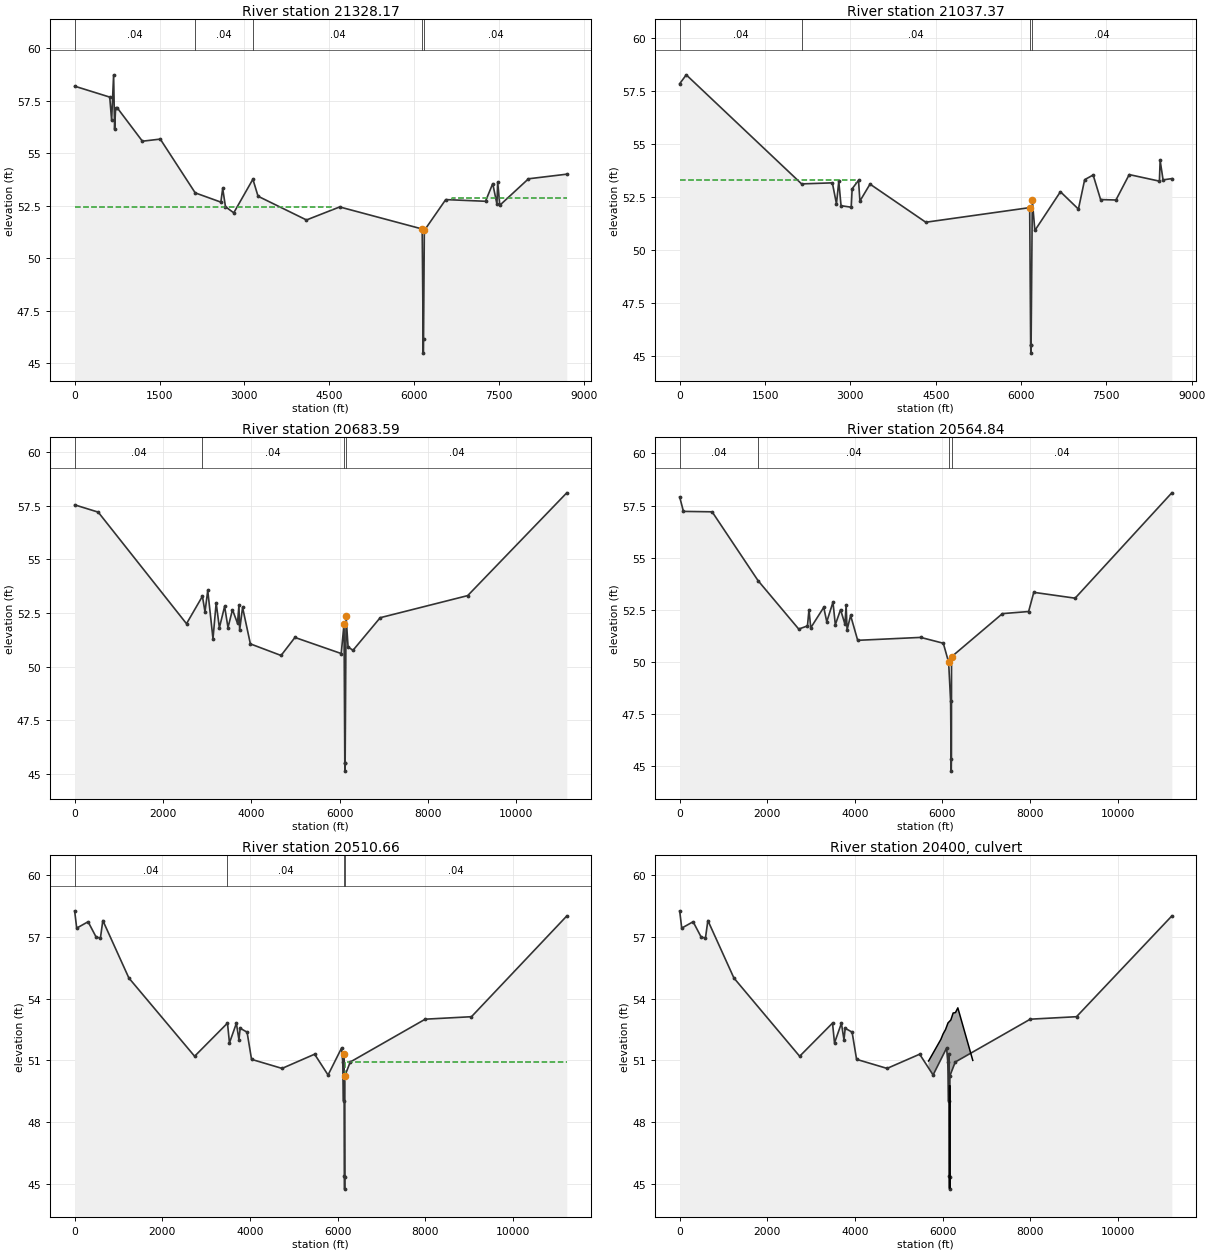
Type RM Length L Ch R = 1 ,21328.17,250,290.8,317
XS GIS Cut Line= 6
     3228659.054    13919630.069     3226630.717     13918397.25
     3223394.038    13917019.392     3223048.221    13916958.114
     3222252.522    13916704.394     3220961.005    13915725.906
#Sta/Elev= 30
       0   58.19  620.29   57.67  653.66   56.56  688.77   58.73  706.32   56.14
  723.87   57.13  752.38   57.16 1197.81   55.57 1513.77   55.67    2131   53.11
 2584.39   52.67 2616.99   53.32  2665.9   52.45 2812.62   52.16 3150.65   53.76
 3241.74   52.95 4097.88   51.82 4684.77   52.44    6143   51.39 6162.74   45.48
    6167   46.14    6181   51.32 6559.17   52.79 7262.24   52.71 7390.25   53.55
  7464.4   52.57 7477.41   53.63 7515.05   52.52 8021.97   53.78 8698.88      54
#Mann= 5 ,-1 , 0
       0     .04       0    2131     .04       0 3150.65     .04       0
    6143    .045       0    6181     .04       0
#XS Ineff= 2 , 0
       0  4557.2   52.46 6669.38       0   52.85
Permanent Ineff=
       F       F
Bank Sta=6143,6181
XS Rating Curve= 0
Exp/Cntr=.3,.1

Type RM Length L Ch R = 1 ,21037.37,353.78,353.78,353.78
XS GIS Cut Line= 6
     3228780.837    13919494.663     3226749.313    13918116.806
     3223383.169    13916785.576     3223231.241    13916700.117
       3222630.9    13916471.752      3221116.65    13915577.055
#Sta/Elev= 30
       0   57.85  115.22   58.27    2143   53.12 2683.51   53.17 2755.52   52.18
 2796.56   53.24 2836.33   52.09 3014.98   52.02 3031.49   52.89 3143.29   53.29
 3167.99   52.31 3345.63   53.11 4325.56   51.31    6152      52    6169   45.52
    6173   45.13    6177   45.53    6198   52.34    6243   50.92 6692.43   52.75
 7008.53   51.93 7118.41   53.32 7267.44   53.54 7398.56   52.38 7668.16   52.36
  7901.4   53.56 8432.18   53.25 8444.92   54.23 8496.51   53.31 8650.11   53.37
#Mann= 4 ,-1 , 0
       0     .04       0    2143     .04       0    6152    .045       0
    6198     .04       0
#XS Ineff= 2 , 0
       0 3103.39   53.31 6692.43       0   52.75
Permanent Ineff=
       F       F
Bank Sta=6152,6198
XS Rating Curve= 0
Exp/Cntr=.3,.1

Type RM Length L Ch R = 1 ,20683.59,85,118.74,160
XS GIS Cut Line= 6
     3228820.055    13919418.225     3226635.246    13917872.542
     3223752.104    13916690.559      3223398.81    13916357.045
     3222920.896    13916181.229     3219015.811    13914241.109
#Sta/Elev= 30
       0   57.54     534    57.2    2534      52 2894.89   53.28 2952.93   52.55
 3015.39   53.55 3134.03    51.3 3205.88   52.97 3278.77   51.81 3397.45   52.81
 3473.73   51.82 3575.78   52.65 3689.26   52.02 3721.69   52.85  3737.9    51.7
 3804.34   52.76 3981.07   51.06 4676.24   50.52 4990.46   51.36 6039.08   50.61
    6103      52    6120   45.52    6124   45.13    6128   45.53    6149   52.34
    6194   50.92 6305.29   50.76 6921.69   52.28 8904.28   53.31 11148.7    58.1
#Mann= 4 ,-1 , 0
       0     .04       0 2894.89     .04       0    6103    .045       0
    6149     .04       0
#XS Ineff= 2 , 0
       0 3804.34   52.76               0
Permanent Ineff=
       F       F
Bank Sta=6103,6149
XS Rating Curve= 0
Exp/Cntr=.3,.1

Type RM Length L Ch R = 1 ,20564.84,54.19,54.19,54.19
BEGIN DESCRIPTION:
Section R -  XS' central segment is manually adjusted for a skewed angle of 52 degree.  Skew option was not used because the skewed segment is small portion of entire XS which is NOT skewed.
END DESCRIPTION:
XS GIS Cut Line= 6
     3228887.845    13919341.962     3226724.341    13917823.427
     3223774.849    13916643.298     3223586.551    13916244.878
     3223139.126    13916001.263     3219098.017    13914179.455
#Sta/Elev= 30
       0   57.91   85.71   57.22     741    57.2 1790.15    53.9 2718.36   51.58
 2917.94   51.73    2953   52.51 2993.27   51.64 3289.53   52.62 3359.03   51.93
 3500.61   52.87 3554.24   51.79 3674.08   52.51 3774.21   51.81 3801.01   52.73
 3822.68   51.54 3903.46   52.23 4065.02   51.04 5504.44   51.18 6020.03    50.9
    6142   49.99    6187   48.13    6201   44.77    6206   45.36    6208   50.25
 7370.54   52.32 7968.45   52.42 8086.59   53.34 9030.25   53.0611238.42   58.11
#Mann= 4 ,-1 , 0
       0     .04       0 1790.15     .04       0    6142    .045       0
    6208     .04       0
#XS Ineff= 2 , 0
       0 3801.01   52.73               0
Permanent Ineff=
       F       F
Bank Sta=6142,6208
XS Rating Curve= 0
Exp/Cntr=.5,.3

Type RM Length L Ch R = 1 ,20510.66,161.11,161.11,161.11
BEGIN DESCRIPTION:
 XS' central segment is manually adjusted for a skewed angle of 52 degree.  Skew option was not used because the skewed segment is small portion of entire XS which is NOT skewed.
END DESCRIPTION:
XS GIS Cut Line= 6
     3228964.109    13919197.908     3226843.011      13917771.8
     3223800.456    13916568.145     3223617.292    13916209.014
     3223367.819    13916023.979     3219159.672    13914056.146
#Sta/Elev= 30
       0   58.26   46.55   57.42  306.56   57.73  493.86   56.97  588.81   56.95
  643.03   57.79    1237      55    2737    51.2    3487   52.81 3532.16   51.85
3690.129    52.8 3748.41      52 3776.29   52.563933.919   52.37 4035.79   51.05
  4731.9   50.61 5474.93    51.3 5781.55   50.296089.781    51.6  6116.9   50.92
 6134.77   49.03    6145   51.31    6154   45.37    6159   44.75    6163   45.36
    6165   50.25 6287.49   50.92 7998.75      53 9053.79   53.1211227.91   58.01
#Mann= 4 ,-1 , 0
       0     .04       0    3487     .04       0    6145    .045       0
    6165     .04       0
#XS Ineff= 2 , 0
       0    6145    50.9    6165       0    50.9
Permanent Ineff=
       F       F
Bank Sta=6145,6165
XS Rating Curve= 0
Exp/Cntr=.5,.3

Type RM Length L Ch R = 2 ,20400   ,,,
BEGIN DESCRIPTION:
2-60" RCP, L=66', at Adlong-Johnson Road
END DESCRIPTION:
Bridge Culvert--1,0,-1,-1, 0
Deck Dist Width WeirC Skew NumUp NumDn MinLoCord MaxHiCord MaxSubmerge Is_Ogee
48,66,2.6,0, 11, 12, , , .95, 0, 0,0,,
    5677    5687    5959    6011    6066    6122    6186    6239    6292    6346
    6687
   50.97      51   52.02   52.29    52.5   52.82   52.96    53.3   53.32   53.55
      51
                                                                                
        
 5511.14    5518    5887    5939    5994    6050    6114    6167    6220    6274
    6518 6533.59
    50.9      51   52.02   52.29    52.5   52.82   52.96    53.3   53.32   53.55
      51   50.87
                                                                                
                
Multiple Barrel Culv=1,5,,66,.013,.5,1,1,1,44.79,44.94, 2,Culvert #1  , 0 ,48
  6155.5  6081.5    6161    6087
Culvert Bottom n=.013
BC Design=,, 0 ,, 0 ,,,,,,

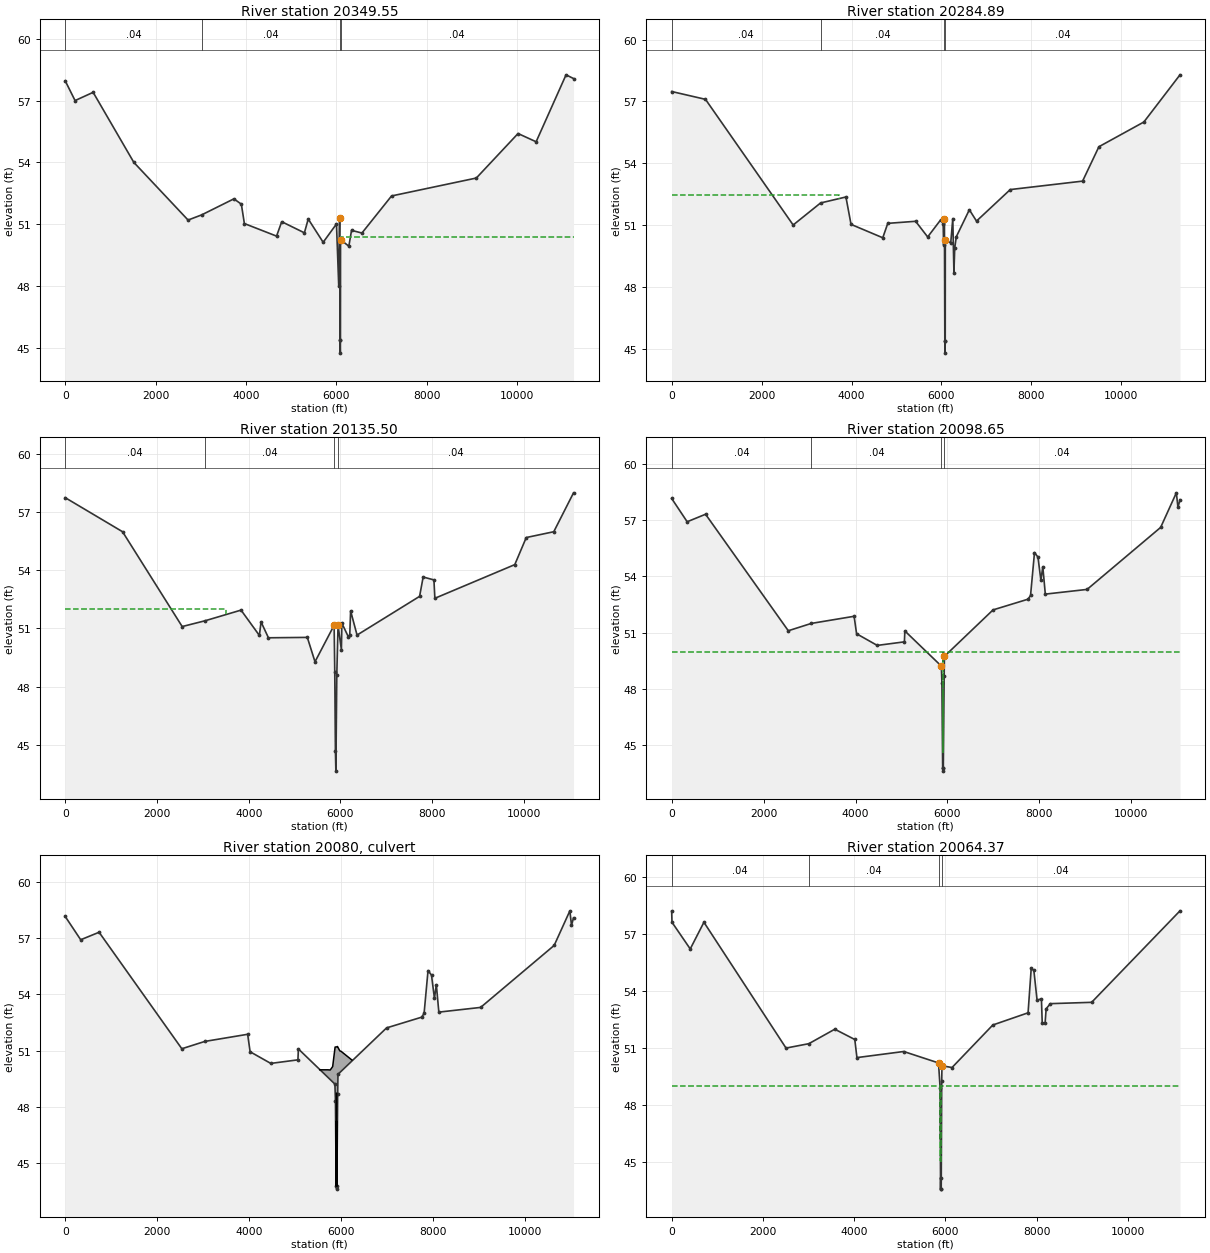
Type RM Length L Ch R = 1 ,20349.55,64.66,64.66,64.66
BEGIN DESCRIPTION:
 XS' central segment is manually adjusted for a skewed angle of 52 degree.  Skew option was not used because the skewed segment is small portion of entire XS which is NOT skewed.
END DESCRIPTION:
XS GIS Cut Line= 6
     3228987.838    13918949.996      3226330.16    13917387.664
     3223714.637    13916403.706     3223723.525    13916070.381
     3223303.659    13915846.332     3219177.879    13913907.413
#Sta/Elev= 30
       0   57.96     218      57     618    57.4    1518      542718.001    51.2
    3018   51.45 3732.22   52.23 3896.79   51.97 3963.71   51.034675.731   50.42
 4789.66   51.125291.439   50.585376.301   51.255706.791   50.12 6001.12   51.01
 6050.79   48.02    6071   51.31    6080   45.37    6086   44.74    6089   45.36
    6091   50.256274.871   49.93 6334.42    50.76564.311   50.57 7219.58   52.37
 9095.08   53.24   10018    55.4   10418      5511079.72   58.25 11245.4   58.07
#Mann= 4 ,-1 , 0
       0     .04       0    3018     .04       0    6071    .045       0
    6091     .04       0
#XS Ineff= 2 , 0
       0    6071    50.4    6091       0    50.4
Permanent Ineff=
       F       F
Bank Sta=6071,6091
XS Rating Curve= 0
Exp/Cntr=.5,.3

Type RM Length L Ch R = 1 ,20284.89,160,149.38,120
BEGIN DESCRIPTION:
 XS' central segment is manually adjusted for a skewed angle of 52 degree.  Skew option was not used because the skewed segment is small portion of entire XS which is NOT skewed.
END DESCRIPTION:
XS GIS Cut Line= 6
     3229035.313    13918855.047     3226389.323    13917291.142
     3223750.358    13916345.422     3223766.011    13916023.423
     3223398.877    13915795.539      3219193.43    13913759.681
#Sta/Elev= 30
       0   57.48     752    57.1    2702      51 3311.84   52.07 3875.53   52.36
 3989.09   51.03 4695.02   50.38 4806.13   51.08 5425.16   51.18 5693.46   50.42
  5982.4   51.25 6037.95   51.07 6048.12   50.03    6066   51.31    6075   45.37
    6080   44.78    6084   45.36    6086   50.25  6206.8   50.14 6252.02   51.31
 6277.42   48.68 6295.08   49.88 6330.39   50.43 6620.63   51.74 6779.41   51.19
 7530.24   52.72 9138.77   53.13    9502    54.8   10502      5611305.29   58.29
#Mann= 4 ,-1 , 0
       0     .04       0 3311.84     .04       0    6066    .045       0
    6086     .04       0
#XS Ineff= 2 , 0
       0 3717.87   52.47               0
Permanent Ineff=
       F       F
Bank Sta=6066,6086
XS Rating Curve= 0
Exp/Cntr=.3,.1

Type RM Length L Ch R = 1 ,20135.50,36.86,36.86,36.86
XS GIS Cut Line= 6
     3229042.095    13918794.007     3226382.971    13917167.534
     3223947.479    13916130.212     3223816.795    13915991.123
     3223387.394    13915692.195     3219240.083    13913697.478
#Sta/Elev= 30
       0   57.76    1250      56    2550    51.1    3050    51.4 3833.04   51.95
 4232.64   50.64 4268.97   51.34 4429.95   50.52 5277.76   50.54 5445.22   49.28
 5862.12   51.17 5875.89   48.75    5890   44.66    5900   43.63 5920.23    48.6
  5947.2   51.17 6020.34    49.9  6031.1   51.27 6173.98   50.56 6203.08   50.68
 6221.35   51.91 6361.65   50.66 7724.91   52.66 7802.74   53.66 8037.55   53.51
 8057.98   52.56    9800    54.3   10050    55.7   10650      5611080.69   58.01
#Mann= 4 ,-1 , 0
       0     .04       0    3050     .04       0 5862.12    .045       0
  5947.2     .04       0
#XS Ineff= 2 , 0
       0  3513.5   52.01               0
Permanent Ineff=
       F       F
Bank Sta=5862.12,5947.2
XS Rating Curve= 0
Exp/Cntr=.5,.3

Type RM Length L Ch R = 1 ,20098.65,34.28,34.28,34.28
XS GIS Cut Line= 6
     3229055.659    13918766.879     3226429.316    13917102.481
     3223963.858    13916082.326     3223357.941    13915612.316
     3221747.103    13914756.415     3219341.163    13913557.521
#Sta/Elev= 30
       0   58.14     337    56.9     737    57.3    2537    51.1    3037   51.49
 3968.57   51.87 4022.52   50.94 4471.98   50.32 5062.43   50.51 5072.61   51.09
 5866.65   49.22 5878.45   48.34    5895   43.78    5905   43.63    5909   43.78
 5927.15   48.67 5933.98   49.74 6990.93   52.21    7753   52.78 7806.97   52.98
 7892.65   55.26 7968.16   55.02  8032.1   53.78 8073.18   54.51    8128   53.05
    9037    53.3   10637    56.610978.31   58.4411013.61   57.67 11057.9   58.07
#Mann= 4 ,-1 , 0
       0     .04       0    3037     .04       0 5866.65    .045       0
 5933.98     .04       0
#XS Ineff= 2 , 0
       0    5892   49.97    5912       0   49.97
Permanent Ineff=
       F       F
Bank Sta=5866.65,5933.98
XS Rating Curve= 0
Exp/Cntr=.5,.3

Type RM Length L Ch R = 2 ,20080   ,,,
BEGIN DESCRIPTION:
1-60" & 2-42" RCP, L=24'
END DESCRIPTION:
Bridge Culvert--1,0,-1,-1, 0
Deck Dist Width WeirC Skew NumUp NumDn MinLoCord MaxHiCord MaxSubmerge Is_Ogee
5.14,24,2.6,0, 10, 10, , , .95, 0, 0,0,,
    5537    5712    5765    5818    5871    5907    5923    5973    6003    6237
   49.98   49.98   49.97   50.15   51.19    51.2   51.22   50.99   50.96    50.5
                                                                                
    5507    5712    5765    5818    5871    5907    5923    5973    6003    6207
   49.98   49.98   49.97   50.15   51.19    51.2   51.22   50.99   50.96    50.5
                                                                                
Multiple Barrel Culv=1,3.5,,24,.013,.2,1,1,3,43.77,43.59, 2,Culvert #1  , 0 ,5.14
    5895    5895    5909    5909
Culvert Bottom n=.013
Culvert=1,5,,24,.013,.2,1,1,3,43.76,5902,43.72,5902,Culvert #2  , 0 ,5.14
Culvert Bottom n=.013
BC Design=,, 0 ,, 0 ,,,,,,

Type RM Length L Ch R = 1 ,20064.37,48.53,48.53,48.53
XS GIS Cut Line= 6
     3229062.441     13918739.75     3226478.978    13917042.906
     3224134.761    13916096.298     3223549.283    13915635.668
     3221867.635    13914685.892     3219325.612    13913417.564
#Sta/Elev= 30
       0   58.18       7    57.6     407    56.2     707    57.6    2507      51
    3007   51.23 3576.08   51.99 4014.34   51.45 4061.38    50.5 5087.09   50.82
 5850.05   50.22 5884.75   48.93  5894.8    43.6    5898    44.2  5909.2    43.6
 5920.27   49.27 5925.88   50.07  6146.5   49.98 7040.14   52.21  7813.3   52.85
 7882.21   55.18 7940.58   55.07 8010.24   53.52 8106.16   53.58 8123.38   52.34
 8186.24    52.3 8209.52   53.06 8301.46   53.33    9207    53.411144.03    58.2
#Mann= 4 ,-1 , 0
       0     .04       0    3007     .04       0 5850.05    .045       0
 5925.88     .04       0
#XS Ineff= 2 , 0
       0    5892      49    5912       0      49
Permanent Ineff=
       F       F
Bank Sta=5850.05,5925.88
XS Rating Curve= 0
Exp/Cntr=.5,.3

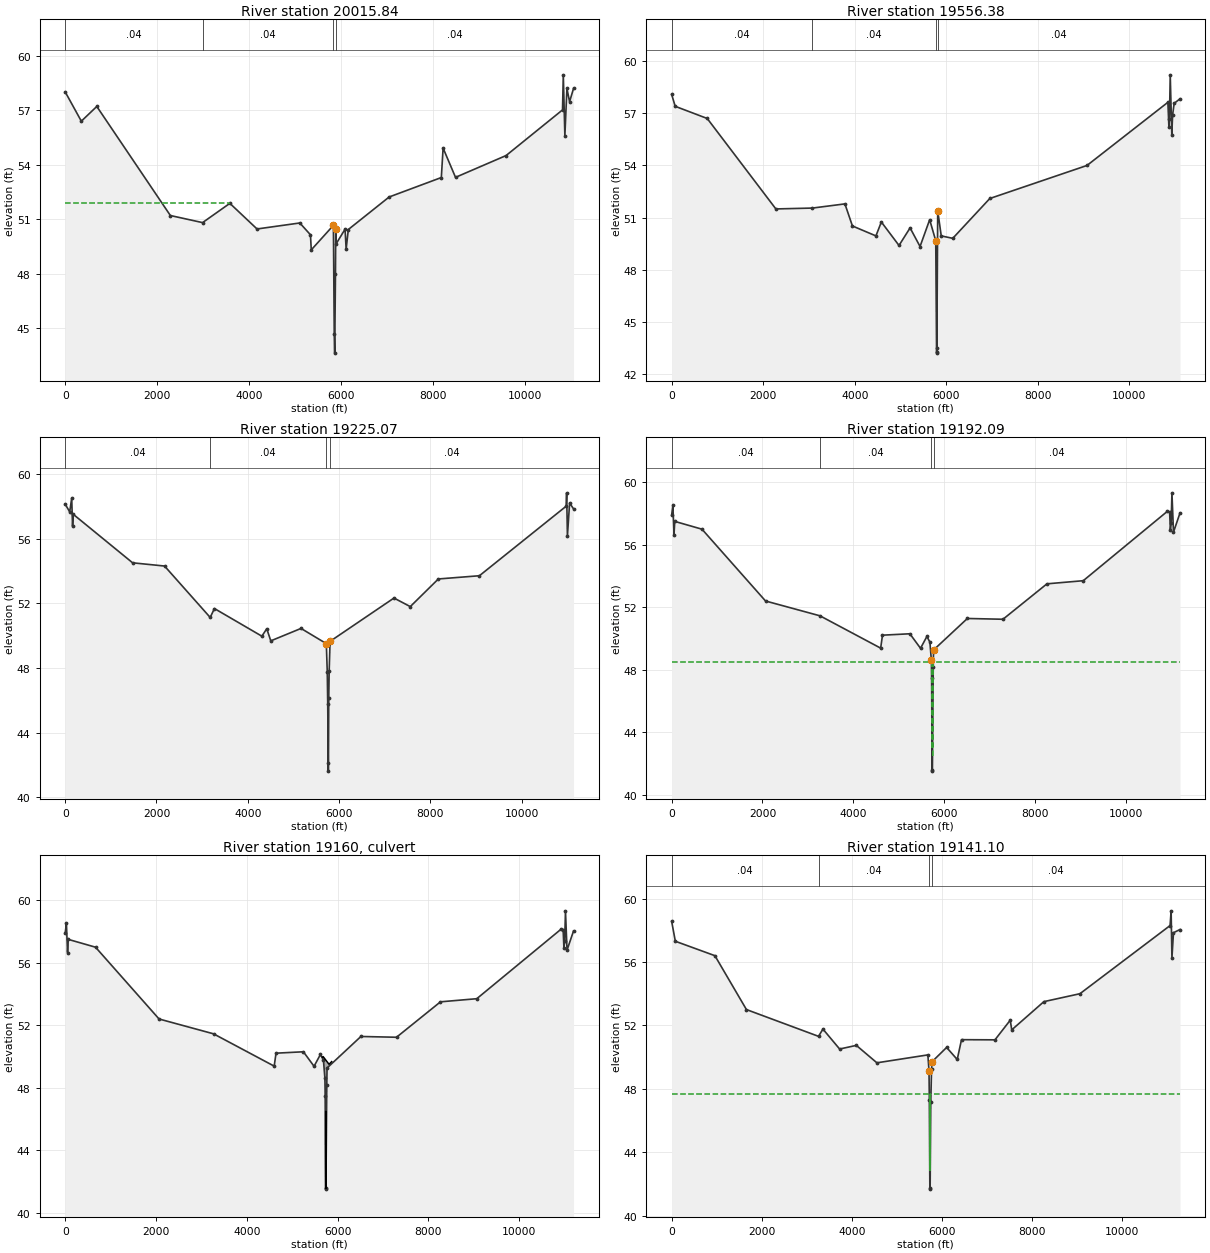
Type RM Length L Ch R = 1 ,20015.84,459.46,459.46,459.46
XS GIS Cut Line= 6
     3229048.877    13918692.275     3226518.753    13916943.497
     3223880.098    13915908.829     3223588.656    13915612.609
     3222105.774    13914620.097     3219519.997    13913215.403
#Sta/Elev= 30
       0      58  350.58   56.39     687    57.2    2287    51.2    2987   50.81
 3580.09   51.87 4171.19   50.46 5101.14   50.79 5332.84   50.14 5350.37   49.31
  5831.7   50.66    5850   44.66    5860   43.63 5876.65   47.97 5882.29   50.44
 5890.23   49.64  6085.3   50.45 6108.71   49.35 6156.11   50.43 7043.87   52.22
 8178.46   53.29 8217.11   54.91    8487    53.3    9587    54.510813.63   57.01
 10830.7   58.9410864.84   55.5810909.36   58.1910967.27   57.4611053.17   58.19
#Mann= 4 ,-1 , 0
       0     .04       0    2987     .04       0  5831.7    .045       0
 5882.29     .04       0
#XS Ineff= 2 , 0
       0 3551.64   51.88               0
Permanent Ineff=
       F       F
Bank Sta=5831.7,5882.29
XS Rating Curve= 0
Exp/Cntr=.3,.1

Type RM Length L Ch R = 1 ,19556.38,331.31,331.31,331.31
BEGIN DESCRIPTION:
Section Q -
END DESCRIPTION:
XS GIS Cut Line= 6
     3229069.223    13918651.583     3226531.094    13916796.775
     3224253.586     13915627.13     3224155.466    13915510.019
     3222795.457    13914781.223     3219543.323    13912997.692
#Sta/Elev= 30
       0   58.08      77    57.4     777    56.7    2277    51.5    3077   51.55
 3785.99   51.79 3950.16   50.52 4463.81   49.95 4582.18   50.75 4968.02    49.4
 5210.25   50.41  5427.7   49.34 5638.18   50.88    5771   49.67    5789   43.25
    5792   43.21    5795   43.48    5814    51.4 5890.84   49.95  6142.9   49.81
 6952.73    52.1    9077      54   10844   57.6310866.16   56.2210878.22   56.67
10895.33   59.2110929.54   55.7610946.65   56.8810980.87   57.5711108.78   57.83
#Mann= 4 ,-1 , 0
       0     .04       0    3077     .04       0    5771    .045       0
    5814     .04       0
#XS Ineff= 2 , 0
       0 3785.99   51.79               0
Permanent Ineff=
       F       F
Bank Sta=5771,5814
XS Rating Curve= 0
Exp/Cntr=.3,.1

Type RM Length L Ch R = 1 ,19225.07,32.98,32.98,32.98
XS GIS Cut Line= 6
     3229082.787     13918610.89     3226499.832    13916601.737
     3224525.789    13915354.927     3224316.889    13915256.807
     3222763.171    13914574.197     3219597.751     13912849.96
#Sta/Elev= 30
       0   58.13   98.53   57.65  142.29   58.49  161.29   56.77     177    57.5
    1477    54.5    2177    54.3    3177   51.12 3270.29   51.67 4309.61   49.96
 4416.88   50.42 4505.12   49.67 5167.91   50.44 5721.93    49.5 5742.61   47.76
 5752.93   45.78 5765.74   41.61 5768.94   42.12 5775.73   46.16 5784.95   47.83
 5804.12   49.64 7204.71   52.32 7561.98   51.79    8177    53.5    9077    53.7
   10977      5810988.46   58.8311005.54   56.1511053.46    58.2 11139.6   57.84
#Mann= 4 ,-1 , 0
       0     .04       0    3177     .04       0 5721.93    .045       0
 5804.12     .04       0
Bank Sta=5721.93,5804.12
XS Rating Curve= 0
Exp/Cntr=.5,.3

Type RM Length L Ch R = 1 ,19192.09,51,51,51
XS GIS Cut Line= 6
     3229096.352    13918556.633     3226465.202     13916498.57
     3224630.239    13915367.587     3224345.376    13915234.651
     3222868.531    13914511.228     3219589.975    13912702.227
#Sta/Elev= 30
       0   57.91    26.5   58.53   51.45   56.66      68    57.5     668      57
    2068    52.4    3268   51.45 4604.44   49.38 4644.66   50.21 5247.61    50.3
 5482.58   49.37 5623.23   50.13 5689.44   49.76 5721.69   48.59 5727.34   47.46
 5737.52    41.5 5744.31   41.55 5762.98   48.14 5769.27   49.26    6515   51.28
 7299.26   51.23    8268    53.5    9068    53.710918.94   58.1410970.33   58.12
10987.47   56.96 11004.6   57.3911021.73   59.3311055.99   56.8111199.33   58.04
#Mann= 4 ,-1 , 0
       0     .04       0    3268     .04       0 5721.69    .045       0
 5769.27     .04       0
#XS Ineff= 2 , 0
       0    5735    48.5    5747       0    48.5
Permanent Ineff=
       F       F
Bank Sta=5721.69,5769.27
XS Rating Curve= 0
Exp/Cntr=.5,.3

Type RM Length L Ch R = 2 ,19160   ,,,
BEGIN DESCRIPTION:
2-60" CMP, L= 25'
END DESCRIPTION:
Bridge Culvert--1,0,-1,-1, 0
Deck Dist Width WeirC Skew NumUp NumDn MinLoCord MaxHiCord MaxSubmerge Is_Ogee
13,25,2.6,0, 4, 3, , , .95, 0, 0,0,,
 5665.92    5683    5812    5871
   49.96   49.99    49.5   49.67
                                
    5674    5803    5862
    49.9    49.5   49.67
                        
Multiple Barrel Culv=1,5,,25,.024,.5,1,2,1,41.51,41.83, 2,Culvert #1  , 0 ,13
    5738    5729    5744    5735
Culvert Bottom n=.024
BC Design=,, 0 ,, 0 ,,,,,,

Type RM Length L Ch R = 1 ,19141.10,78.46,78.46,78.46
XS GIS Cut Line= 6
      3229123.48     13918515.94     3226503.272     13916453.71
     3224674.552    13915323.275     3224361.201    13915190.339
     3222870.588    13914437.336     3219574.425    13912577.821
#Sta/Elev= 30
       0   58.56   81.19   57.31     959    56.4    1659      53    3259   51.31
 3356.01   51.77  3726.6   50.51 4097.46   50.74 4553.91   49.64 5684.84   50.14
 5710.11   49.13 5717.43   47.28  5728.5   41.76 5734.92   41.67 5749.34   47.14
 5766.31   49.25 5777.61   49.71 6100.74   50.61 6336.01   49.85 6431.12    51.1
 7173.59   51.09 7512.38   52.33 7545.99   51.72    8259    53.5    9059      54
   11059    58.311082.37   59.2311100.05   56.2411134.49   57.8511279.22   58.05
#Mann= 4 ,-1 , 0
       0     .04       0    3259     .04       0 5710.11    .045       0
 5777.61     .04       0
#XS Ineff= 2 , 0
       0    5726    47.7    5738       0    47.7
Permanent Ineff=
       F       F
Bank Sta=5710.11,5777.61
XS Rating Curve= 0
Exp/Cntr=.5,.3