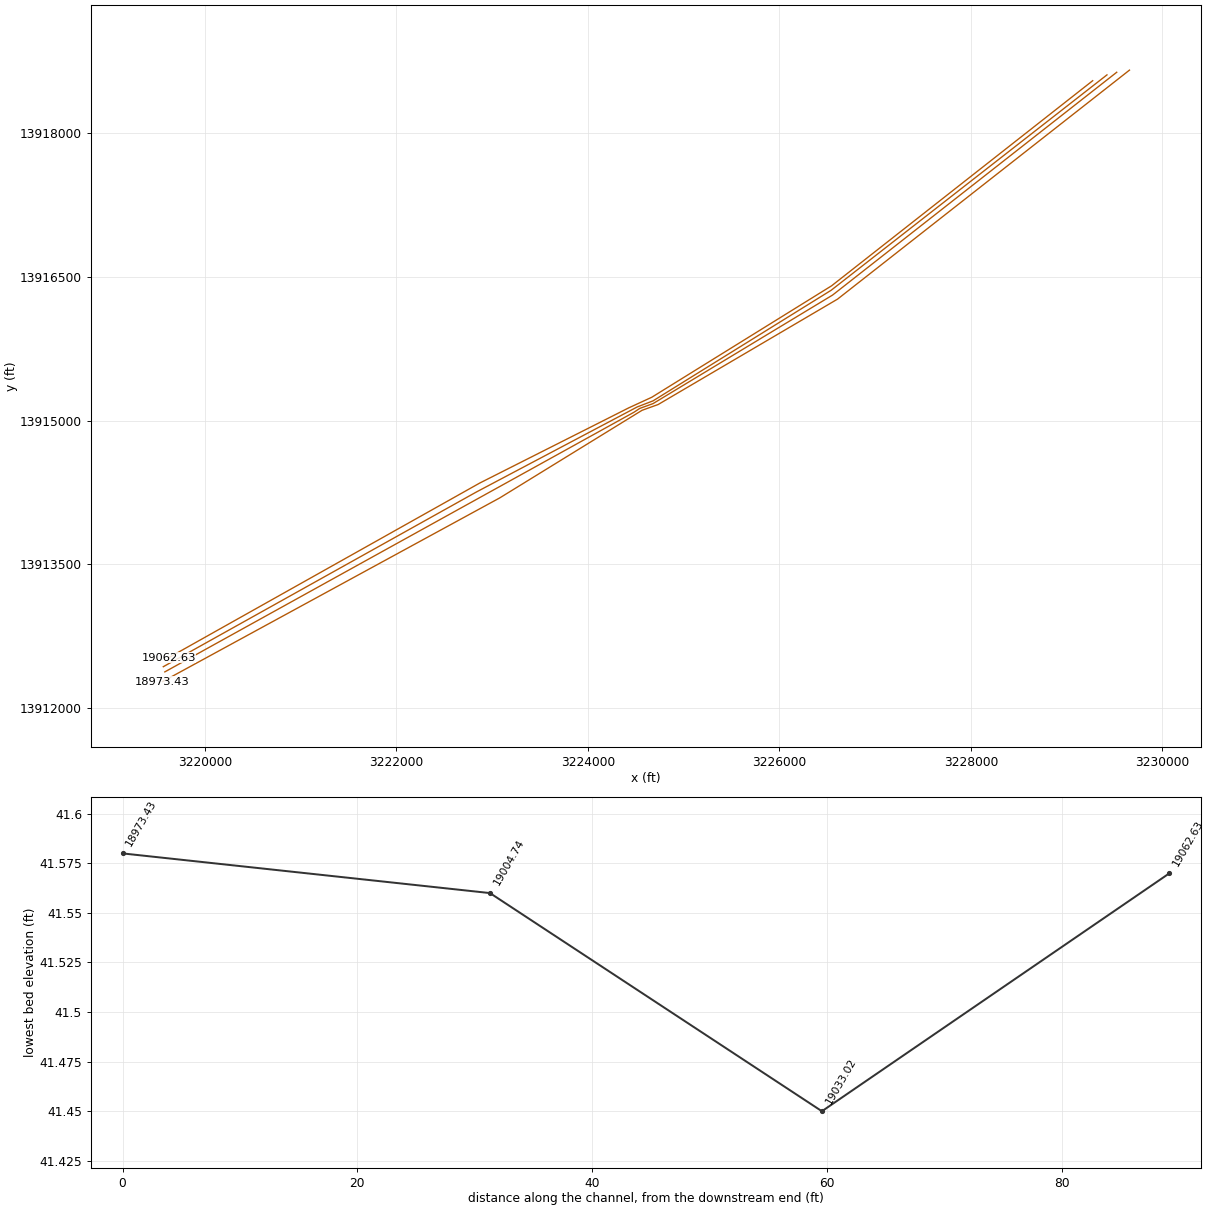
HEC-RAS study Q128-00-00.prj: Q128-00-00

--- Q128-00-00.g05 (geometry) --- (continued)

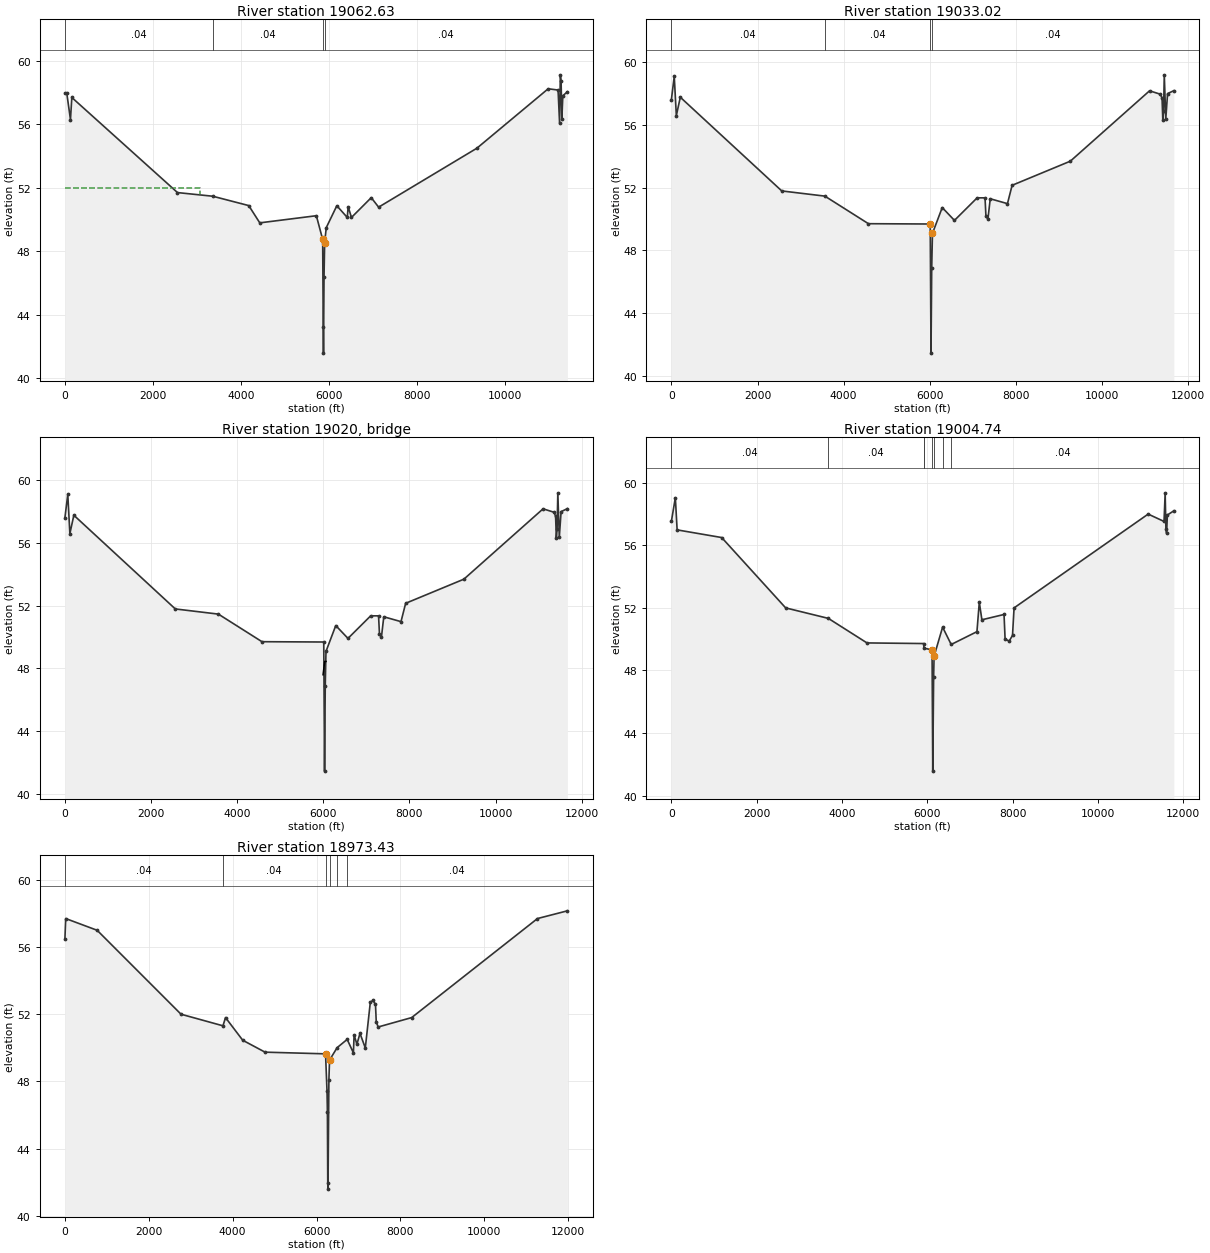
Type RM Length L Ch R = 1 ,19062.63,29.61,29.61,29.61
XS GIS Cut Line= 6
     3229272.687    13918549.851     3226546.755    13916408.537
     3224668.221    13915244.146      3224427.67    13915133.366
     3222872.257      13914348.5     3219621.077    13912523.393
#Sta/Elev= 30
       0   57.97   40.96      58  126.15   56.31     157    57.7    2557    51.7
    3357   51.47 4174.89   50.88 4425.83   49.79 5710.87   50.24  5854.3   48.74
 5866.83   43.25 5872.76   41.57 5885.02    46.4 5899.16   48.55 5936.17   49.49
 6175.69   50.87 6413.09   50.13 6432.74   50.81 6507.94   50.13 6957.58   51.38
 7124.96   50.78    9357    54.510975.78   58.2511200.55   58.1711234.96   56.09
11252.16   59.1311269.36   58.7111286.56   56.36 11308.5   57.8111412.02   58.06
#Mann= 4 ,-1 , 0
       0     .04       0    3357     .04       0  5854.3    .045       0
 5899.16     .04       0
#XS Ineff= 2 , 0
       0    3057      52               0
Permanent Ineff=
       F       F
Bank Sta=5854.3,5899.16
XS Rating Curve= 0
Exp/Cntr=.5,.3

Type RM Length L Ch R = 1 ,19033.02,28.28,28.28,28.28
XS GIS Cut Line= 6
     3229421.894     13918610.89     3226542.045    13916361.886
     3224680.882    13915206.164     3224516.294    13915142.861
     3222834.341    13914253.474     3219566.649    13912430.089
#Sta/Elev= 30
       0   57.62   66.54   59.11  115.28   56.61  207.43   57.78    2563    51.8
    3563   51.47 4574.82   49.71 6009.42   49.69 6027.94   41.45 6044.28   46.91
 6061.25   49.09 6288.43   50.74 6571.88   49.92 7098.89   51.36 7281.88   51.36
 7303.37   50.18 7348.97   50.01 7403.27    51.3 7802.83   50.99 7910.76   52.16
    9263    53.7 11101.7   58.1911355.73   57.9711392.25   57.7111409.53   56.31
11426.61   56.8811443.79   59.2111478.14   56.3711519.72   58.0111665.75    58.2
#Mann= 4 ,-1 , 0
       0     .04       0    3563     .04       0 6009.42    .045       0
 6061.25     .04       0
Bank Sta=6009.42,6061.25
XS Rating Curve= 0
Exp/Cntr=.5,.3

Type RM Length L Ch R = 3 ,19020   ,,,
BEGIN DESCRIPTION:
5" steel pipe crossing
END DESCRIPTION:
Bridge Culvert--1,0,-1,-1, 0
Deck Dist Width WeirC Skew NumUp NumDn MinLoCord MaxHiCord MaxSubmerge Is_Ogee
14,.42,2.6,0, 4, 4, , , .95, 0, 0,0,,
    5993    6007    6032    6063
    47.6   47.91   48.45   48.45
   47.18   47.49   48.03   48.03
    6110    6124    6149    6180
    47.6   47.91   48.45   48.45
   47.18   47.49   48.03   48.03
BR Coef=-1 , 0 , 0 ,, 0 ,,,.8,-1,,0,
WSPro=,,,, 1 ,,,, 0 ,,,, 0 ,,,,-1 ,-1 ,-1 , 0 , 0 , 0 , 0 , 0
BR U #Sta/Elev= 30
       0   57.62   66.54   59.11  115.28   56.61  207.43   57.78    2563    51.8
    3563   51.47 4574.82   49.71 6009.42   49.69 6027.94   41.45 6044.28   46.91
 6061.25   49.09 6288.43   50.74 6571.88   49.92 7098.89   51.36 7281.88   51.36
 7303.37   50.18 7348.97   50.01 7403.27    51.3 7802.83   50.99 7910.76   52.16
    9263    53.7 11101.7   58.1911355.73   57.9711392.25   57.7111409.53   56.31
11426.61   56.8811443.79   59.2111478.14   56.3711519.72   58.0111665.75    58.2
BR U #Mann= 4
       0     .04    3563     .04 6009.42    .044 6061.25     .04
BR D #Sta/Elev= 30
       0   57.53   92.95   59.05  134.65   56.99    1180    56.5    2680      52
    3680   51.33 4586.74   49.76 5917.88   49.72 5921.77   49.42 6112.45   49.32
 6129.17   41.56 6149.09   47.55 6160.22   48.91 6359.93   50.77 6561.39   49.66
 7164.98   50.48 7220.32   52.36 7281.28   51.24 7800.41   51.58 7825.33      50
 7921.82   49.88 7999.08   50.24 8035.44      52   11180      58 11552.3   57.53
11578.46   59.3611596.45   57.0411612.75   56.77 11629.9   57.9411782.25   58.21
BR D #Mann= 8
       0     .04    3680     .04 5917.88     .11 5921.77     .04 6112.45    .044
 6160.22     .04 6359.93     .11 6561.39     .04
BC Design=,, 0 ,, 0 ,,,,,,

Type RM Length L Ch R = 1 ,19004.74,31.3,31.3,31.3
XS GIS Cut Line= 6
     3229523.626    13918638.018     3226556.108    13916311.156
     3224680.882    13915177.678     3224541.615    13915127.035
     3224484.642    13915089.054       3219582.2    13912375.661
#Sta/Elev= 30
       0   57.53   92.95   59.05  134.65   56.99    1180    56.5    2680      52
    3680   51.33 4586.74   49.76 5917.88   49.72 5921.77   49.42 6112.45   49.32
 6129.17   41.56 6149.09   47.55 6160.22   48.91 6359.93   50.77 6561.39   49.66
 7164.98   50.48 7220.32   52.36 7281.28   51.24 7800.41   51.58 7825.33      50
 7921.82   49.88 7999.08   50.24 8035.44      52   11180      58 11552.3   57.53
11578.46   59.3611596.45   57.0411612.75   56.77 11629.9   57.9411782.25   58.21
#Mann= 8 ,-1 , 0
       0     .04       0    3680     .04       0 5917.88     .11       0
 5921.77     .04       0 6112.45    .045       0 6160.22     .04       0
 6359.93     .11       0 6561.39     .04       0
#XS Ineff= 2 , 0
       0                 7220.32       0   52.36
Permanent Ineff=
       F       F
Bank Sta=6112.45,6160.22
XS Rating Curve= 0
Exp/Cntr=.5,.3

Type RM Length L Ch R = 1 ,18973.43,635.26,635.26,635.26
XS GIS Cut Line= 6
     3229656.886    13918660.421     3226608.216    13916268.968
      3224734.69    13915168.182     3224566.936    13915108.045
     3223081.882    13914193.867     3219558.874    13912274.581
#Sta/Elev= 30
       0   56.49      19    57.7     769      57    2769      52    3769   51.31
 3829.77    51.8 4240.19   50.45 4772.22   49.74 6215.16   49.64  6250.4    47.4
 6259.45   46.15  6267.8   41.95 6273.37   41.58 6294.93   48.08 6310.32   49.27
 6491.77   50.01 6731.19    50.5 6878.93    49.7  6896.5   50.77 6962.82   50.21
 7036.48   50.86 7163.18   49.99 7283.14   52.72 7348.36   52.82 7406.16   52.58
 7424.31   51.54 7470.15   51.24    8269    51.8   11269    57.711981.93   58.16
#Mann= 6 ,-1 , 0
       0     .04       0    3769     .04       0 6215.16    .045       0
 6310.32     .04       0 6491.77     .11       0 6731.19     .04       0
#XS Ineff= 2 , 0
       0                 7348.36       0   52.82
Permanent Ineff=
       F       F
Bank Sta=6215.16,6310.32
XS Rating Curve= 0
Exp/Cntr=.3,.1