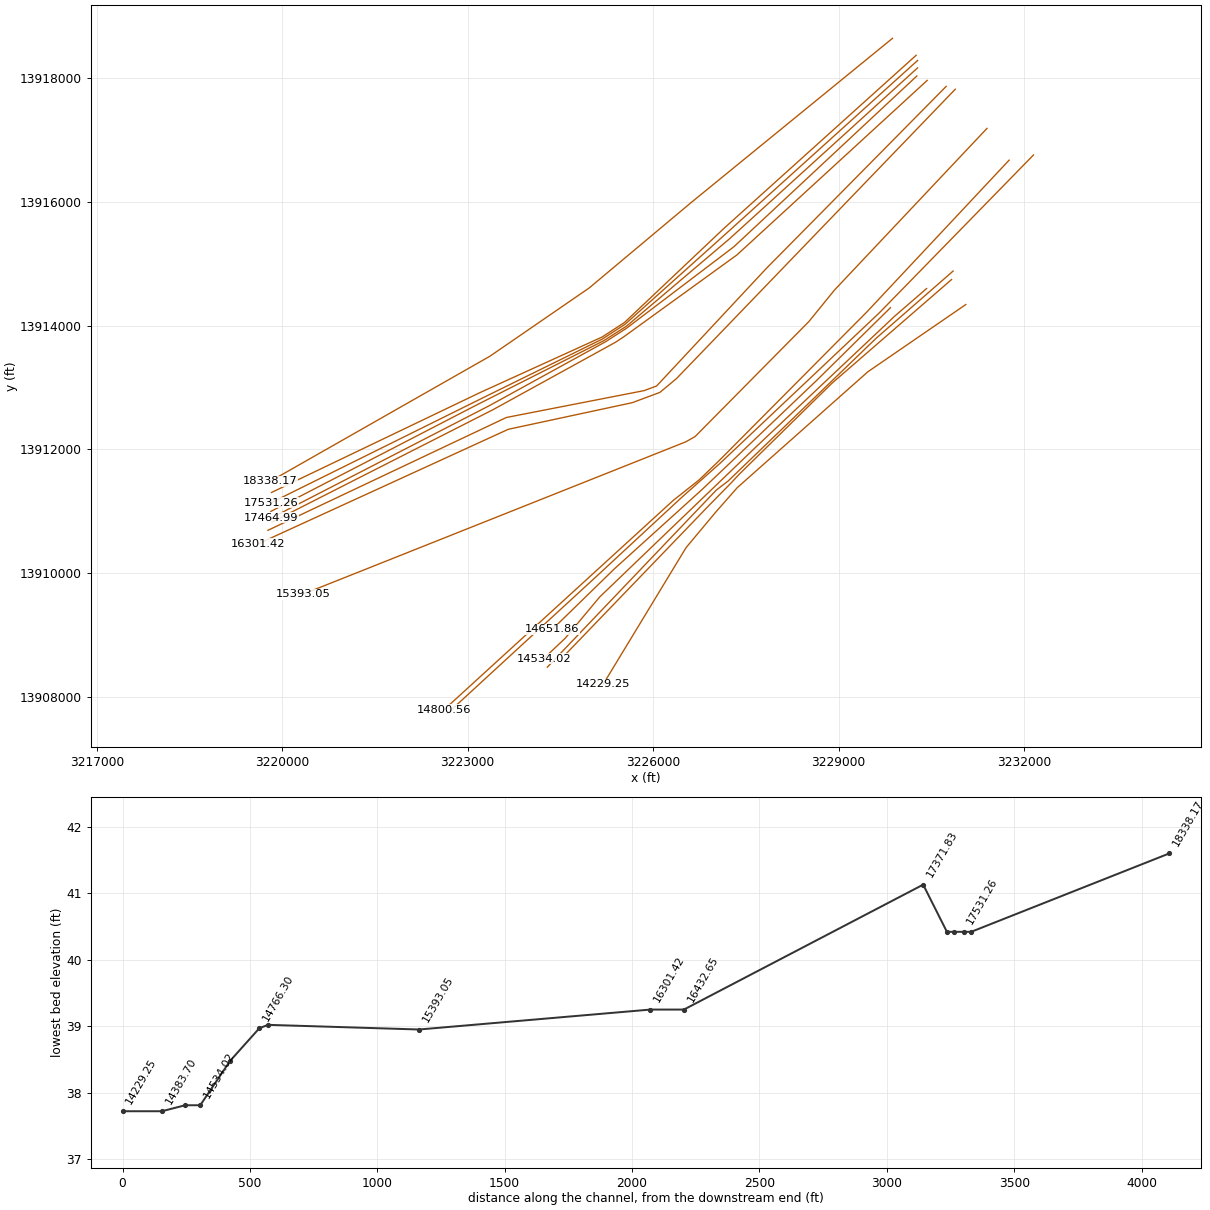
HEC-RAS study Q128-00-00.prj: Q128-00-00

--- Q128-00-00.g05 (geometry) --- (continued)

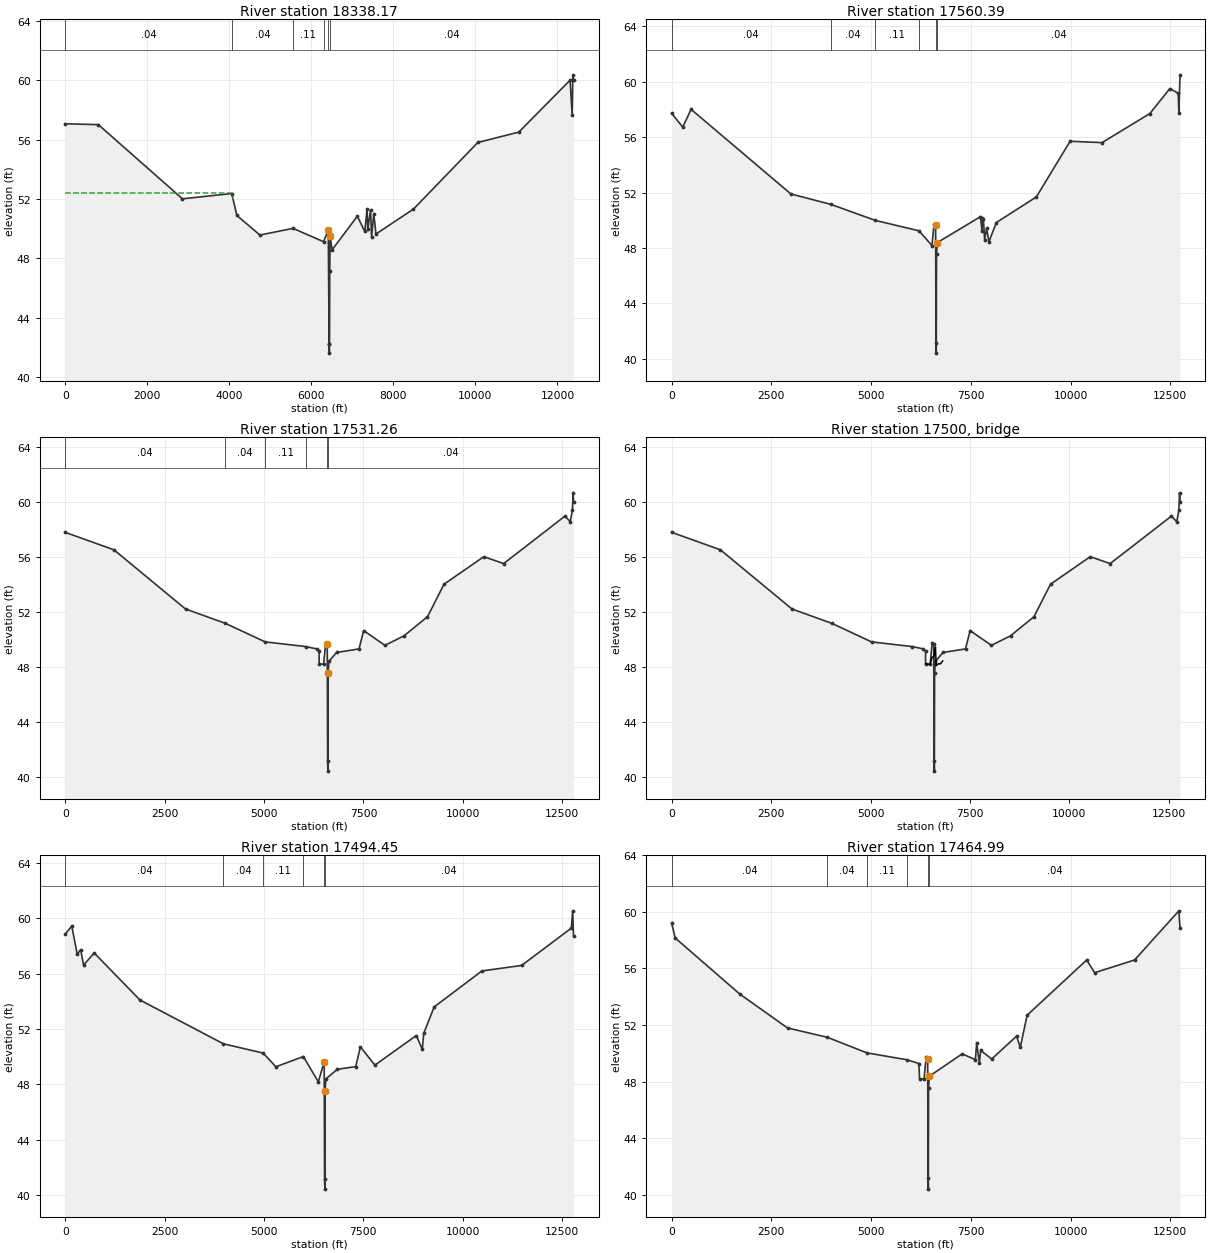
Type RM Length L Ch R = 1 ,18338.17,777.78,777.78,777.78
XS GIS Cut Line= 6
     3229871.858    13918648.478     3226621.311    13915997.331
     3224962.581     13914607.95       3224851.8    13914531.986
     3223359.223    13913505.738     3219806.398     13911482.75
#Sta/Elev= 30
       0   57.06     809      57    2859      52    4059   52.36 4185.21   50.88
 4745.97   49.56 5554.89   50.01 6299.05   49.11    6413   49.92    6434   42.19
    6439    41.6    6443   42.22    6449   47.14    6459   49.47    6508   48.57
 7121.82   50.83 7303.86    49.8 7358.47    51.3 7376.67   49.94 7443.13   51.25
 7469.61   49.42  7522.3   51.01 7575.51   49.63  8490.8   51.31   10059    55.8
   11059    56.5   12309      6012358.95   57.6512376.22   60.3612392.42   60.04
#Mann= 6 ,-1 , 0
       0     .04       0    4059     .04       0 5554.89     .11       0
 6299.05     .04       0    6413    .045       0    6459     .04       0
#XS Ineff= 2 , 0
       0 4091.88   52.39 7358.47       0    51.3
Permanent Ineff=
       F       F
Bank Sta=6413,6459
XS Rating Curve= 0
Exp/Cntr=.3,.1

Type RM Length L Ch R = 1 ,17560.39,29.14,29.14,29.14
BEGIN DESCRIPTION:
Section P -
END DESCRIPTION:
XS GIS Cut Line= 6
      3230254.03    13918373.792     3227143.422    13915572.305
     3225535.474    13914050.883     3225174.646    13913816.661
     3223195.994     13912916.04     3219825.506    13911301.218
#Sta/Elev= 30
       0   57.71  277.57   56.72     487      58    2987    51.9    3987   51.15
 5107.52   49.99 6199.87   49.24    6524   48.18    6577   49.75    6616   49.64
    6625   41.18    6632   40.42    6638   47.54    6657   48.39 7739.63   50.26
 7778.71   49.22  7789.5    50.2 7813.47   50.11 7844.67   48.59 7891.97   49.41
  7953.3   48.46 8138.52   49.84  9140.1   51.68    9987    55.7   10787    55.6
   11987    57.7   12487    59.512697.02   59.1612713.65   57.7212741.34   60.49
#Mann= 6 ,-1 , 0
       0     .04       0    3987     .04       0 5107.52     .11       0
 6199.87     .04       0    6616    .045       0    6657     .04       0
Bank Sta=6616,6657
XS Rating Curve= 0
Exp/Cntr=.5,.3

Type RM Length L Ch R = 1 ,17531.26,36.81,36.81,36.81
XS GIS Cut Line= 6
     3230277.916    13918290.192     3227147.656    13915461.094
     3225544.969    13914022.396     3225174.646    13913781.845
     3223245.376      13912832.7     3219825.506    13911138.795
#Sta/Elev= 30
       0   57.77    1225    56.5    3025    52.2    4025   51.16 5026.88   49.81
 6048.05   49.47 6329.25    49.3 6383.72   49.13    6385   48.22    6497   48.18
    6550   49.75    6589   49.64    6598   41.18    6605   40.42    6611   47.54
    6630   48.39 6821.33   49.04 7388.06    49.3 7503.88   50.63 8038.97   49.56
 8519.73   50.25 9109.04   51.64    9525      54   10525      56   11025    55.5
12566.32   58.9512699.64   58.5412753.21    59.412769.95   60.6412781.07   59.97
#Mann= 6 ,-1 , 0
       0     .04       0    4025     .04       0 5026.88     .11       0
 6048.05     .04       0    6589    .045       0    6611     .04       0
#XS Ineff= 2 , 0
       0    6589    48.3    6635       0    48.3
Permanent Ineff=
       F       F
Bank Sta=6589,6611
XS Rating Curve= 0
Exp/Cntr=.5,.3

Type RM Length L Ch R = 3 ,17500   ,,,
BEGIN DESCRIPTION:
Wood bridge
END DESCRIPTION:
Bridge Culvert--1,0,-1,-1, 0
Deck Dist Width WeirC Skew NumUp NumDn MinLoCord MaxHiCord MaxSubmerge Is_Ogee
14,10,2.6,0, 13, 13, , , .95, 0, 0,0,,
    6385    6441    6497    6550    6582    6582    6610    6632    6632    6652
    6705    6755    6815
   48.22   48.18   48.18   48.71   48.71   48.71   48.94   49.44   49.44   48.08
   48.22   48.21   48.42
                                           47.66   47.89   48.39
                        
    6310    6366    6422    6475    6507    6507    6535    6557    6557    6577
    6630    6680    6740
   48.22   48.18   48.18   48.71   48.71   48.71   48.94   49.44   49.44   48.08
   48.22   48.21   48.42
                                           47.66   47.89   48.39
                        
Pier Skew, UpSta & Num, DnSta & Num=  ,6605, 2 ,6530, 2 , 0 , 0 , 0 ,,
      .6      .6
      35      50
      .6      .6
      35      50
BR Coef=-1 , 1 , 1 ,1.05, 0 ,,,.8,-1,1.2,0,
WSPro=,,,, 1 ,,,, 0 ,,,, 0 ,,,,-1 ,-1 ,-1 , 0 , 0 , 0 , 0 , 0
BR U #Sta/Elev= 30
       0   57.77    1225    56.5    3025    52.2    4025   51.16 5026.88   49.81
 6048.05   49.47 6329.25    49.3 6383.72   49.13    6385   48.22    6497   48.18
    6550   49.75    6589   49.64    6598   41.18    6605   40.42    6611   47.54
    6630   48.39 6821.33   49.04 7388.06    49.3 7503.88   50.63 8038.97   49.56
 8519.73   50.25 9109.04   51.64    9525      54   10525      56   11025    55.5
12566.32   58.9512699.64   58.5412753.21    59.412769.95   60.6412781.07   59.97
BR U #Mann= 6
       0     .04    4025     .04 5026.88     .11 6048.05     .04    6589    .044
    6611     .04
BR D #Sta/Elev= 30
       0   58.86  165.13   59.45  303.18    57.4  388.42   57.74  461.41   56.63
     730    57.5    1880    54.1    3980   50.93 4979.13   50.26  5298.4   49.27
 5990.16   50.01    6366   48.18    6514   49.64    6523   41.18    6530   40.42
    6536   47.54    6555   48.39 6845.92   49.09 7306.68   49.28 7424.19   50.71
 7788.84   49.39 8830.96   51.53 8982.24   50.53 9015.85   51.68    9280    53.6
   10480    56.2   11480    56.6   12730    59.312763.07   60.5512785.05   58.76
BR D #Mann= 6
       0     .04    3980     .04 4979.13     .11 5990.16     .04    6514    .044
    6536     .04
BC Design=,, 0 ,, 0 ,,,,,,

Type RM Length L Ch R = 1 ,17494.45,29.45,29.45,29.45
XS GIS Cut Line= 6
     3230277.916    13918170.763     3227236.824    13915406.836
     3225567.125    13913990.745     3225199.967    13913756.523
     3223143.709    13912716.857     3219815.952     13910995.48
#Sta/Elev= 30
       0   58.86  165.13   59.45  303.18    57.4  388.42   57.74  461.41   56.63
     730    57.5    1880    54.1    3980   50.93 4979.13   50.26  5298.4   49.27
 5990.16   50.01    6366   48.18    6514   49.64    6523   41.18    6530   40.42
    6536   47.54    6555   48.39 6845.92   49.09 7306.68   49.28 7424.19   50.71
 7788.84   49.39 8830.96   51.53 8982.24   50.53 9015.85   51.68    9280    53.6
   10480    56.2   11480    56.6   12730    59.312763.07   60.5512785.05   58.76
#Mann= 6 ,-1 , 0
       0     .04       0    3980     .04       0 4979.13     .11       0
 5990.16     .04       0    6514    .045       0    6536     .04       0
#XS Ineff= 2 , 0
       0    6514      48    6560       0      48
Permanent Ineff=
       F       F
Bank Sta=6514,6536
XS Rating Curve= 0
Exp/Cntr=.5,.3

Type RM Length L Ch R = 1 ,17464.99,93.16,93.16,93.16
XS GIS Cut Line= 6
     3230265.973    13918039.391     3227306.687    13915277.229
      3225570.29    13913959.093     3225231.619    13913740.698
     3223357.634    13912709.838     3219825.506    13910890.383
#Sta/Elev= 30
       0   59.19   89.59   58.15    1704    54.2    2904    51.8    3904   51.14
 4893.99   50.04 5907.29   49.55 6196.31   49.29    6214   48.22    6326   48.18
    6379   49.75    6418   49.64    6427   41.18    6434   40.42    6440   47.54
    6459   48.39 7281.85   49.97 7613.18   49.56 7646.31   50.74 7712.31   49.35
  7746.2   50.21 8023.52   49.61 8645.96   51.22 8739.32   50.43 8910.78    52.7
   10404    56.6   10604    55.7   11604    56.612715.01   60.07 12743.1   58.85
#Mann= 6 ,-1 , 0
       0     .04       0    3904     .04       0 4893.99     .11       0
 5907.29     .04       0    6418    .045       0    6459     .04       0
Bank Sta=6418,6459
XS Rating Curve= 0
Exp/Cntr=.3,.1

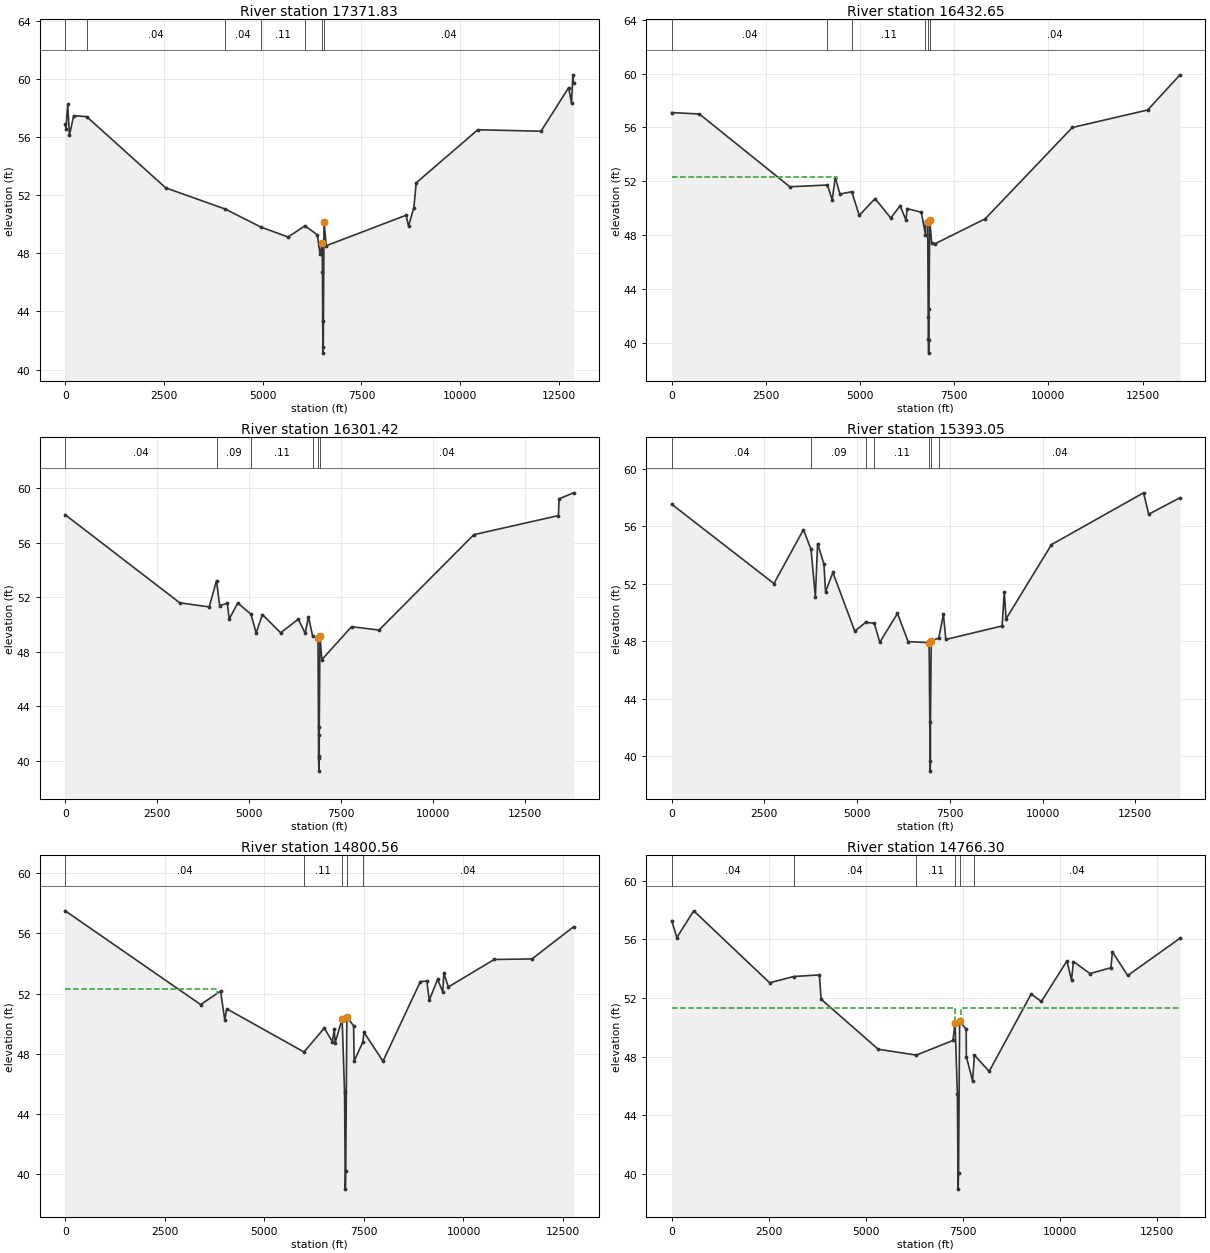
Type RM Length L Ch R = 1 ,17371.83,939.19,939.19,939.19
XS GIS Cut Line= 6
     3230433.173    13917967.734     3227355.312    13915144.512
     3225529.143    13913822.992     3225389.877    13913731.202
      3223413.74    13912643.164     3219835.061    13910823.502
#Sta/Elev= 30
       0   56.87   18.93   56.55   63.32   58.26   107.7   56.13  213.99   57.47
     545    57.4    2545    52.5    4045   51.05 4958.67    49.8 5642.78   49.12
 6068.64   49.89 6383.41   49.27    6451   47.92    6504   48.69    6513   46.74
    6518   43.35    6530   41.13    6533   41.54    6552   50.17 6608.37   48.52
 8629.55   50.62 8691.75   49.87 8826.11   51.15 8886.08   52.85   10445    56.5
   12045    56.4   12745    59.412817.21   58.3212850.87   60.2812868.16   59.72
#Mann= 7 ,-1 , 0
       0     .04       0     545     .04       0    4045     .04       0
 4958.67     .11       0 6068.64     .04       0    6504    .045       0
    6552     .04       0
Bank Sta=6504,6552
XS Rating Curve= 0
Exp/Cntr=.3,.1

Type RM Length L Ch R = 1 ,16432.65,131.23,131.23,131.23
XS GIS Cut Line= 6
      3230740.09    13917870.813     3227831.976    13914926.869
     3226056.892     13913024.95     3225854.641    13912949.535
     3223627.012    13912515.153     3219768.181    13910689.742
#Sta/Elev= 30
       0   57.11     736      57    3136    51.6    4136   51.73 4260.97   50.63
 4342.53   52.28 4467.51   51.06 4780.42   51.23 4979.72   49.48 5400.47   50.72
  5815.7   49.28 6064.82   50.19 6219.09   49.13 6250.94   49.98 6626.75   49.71
 6737.88   48.03    6741   49.03    6796      49    6811   41.93    6812   40.33
    6821   39.25    6830   40.21    6831    42.5    6850   49.17    6901   47.43
 6999.55   47.38 8321.64   49.22   10636      56   12636    57.313494.25   59.91
#Mann= 6 ,-1 , 0
       0     .04       0    4136     .09       0 4780.42     .11       0
 6737.88     .04       0    6796    .045       0    6850     .04       0
#XS Ineff= 2 , 0
       0 4382.34   52.31               0
Permanent Ineff=
       F       F
Bank Sta=6796,6850
XS Rating Curve= 0
Exp/Cntr=.3,.1

Type RM Length L Ch R = 1 ,16301.42,908.37,908.37,908.37
BEGIN DESCRIPTION:
Section O -
END DESCRIPTION:
XS GIS Cut Line= 6
     3230887.003    13917824.419     3226379.503    13913145.858
     3226109.104    13912920.525       3225663.3    13912754.558
     3223655.763    13912323.417     3219614.243    13910472.633
#Sta/Elev= 30
       0   58.06    3116    51.6    3916    51.3    4116   53.22 4201.32    51.4
 4409.78   51.56 4461.94   50.41 4693.02   51.59 5053.24   50.76 5194.76   49.39
 5363.88   50.74 5859.58    49.4 6340.16    50.4 6528.54   49.36 6615.93   50.58
 6733.08   49.13    6876      49    6891   41.93    6892   40.33    6901   39.25
    6910   40.21    6911    42.5    6930   49.17    6981   47.43 7790.42   49.85
 8536.33    49.6   11116    56.6   13416      5813435.56   59.2313827.37   59.67
#Mann= 6 ,-1 , 0
       0     .04       0    4116     .09       0 5053.24     .11       0
 6733.08     .04       0    6876    .045       0    6930     .04       0
#XS Ineff= 2 , 0
       0    4116   53.22               0
Permanent Ineff=
       F       F
Bank Sta=6876,6930
XS Rating Curve= 0
Exp/Cntr=.3,.1

Type RM Length L Ch R = 1 ,15393.05,592.49,592.49,592.49
XS GIS Cut Line= 6
     3231400.547    13917191.447     3228932.418    13914574.903
     3228517.876    13914064.823     3226678.095    13912205.598
     3226526.167    13912120.139     3220335.593    13909656.369
#Sta/Elev= 30
       0   57.52    2757      52 3554.19   55.75 3758.23   54.37  3874.2   51.08
 3934.73   54.77 4106.15   53.35 4148.78   51.42 4346.36   52.77 4937.23   48.69
 5236.29   49.31  5464.8   49.23 5612.52   47.91 6088.16   49.92  6376.9   47.96
    6942   47.89    6972   38.95    6977   39.66    6978   42.36    7000   48.02
 7201.05    48.2  7328.2   49.85 7392.52   48.11 8910.63   49.05 8968.53   51.42
 9016.78   49.5410241.89   54.7112724.59   58.3112863.97   56.8213707.29   57.97
#Mann= 7 ,-1 , 0
       0     .04       0 3758.23     .09       0 5236.29     .04       0
  5464.8     .11       0    6942    .045       0    7000     .11       0
 7201.05     .04       0
#XS Ineff= 2 , 0
       0 3554.19   55.75               0
Permanent Ineff=
       F       F
Bank Sta=6942,7000
XS Rating Curve= 0
Exp/Cntr=.3,.1

Type RM Length L Ch R = 1 ,14800.56,34.26,34.26,34.26
BEGIN DESCRIPTION:
Section N -
END DESCRIPTION:
XS GIS Cut Line= 6
     3231758.833    13916677.903     3229453.371     13914218.23
     3227063.964    13911813.259     3226741.398    13911502.933
     3226325.921    13911173.885     3222615.363    13907785.234
#Sta/Elev= 30
       0   57.49 3401.17   51.27 3901.81   52.16 4007.53   50.22  4053.4   50.99
  5997.3   48.12 6505.33   49.71 6707.29   48.81 6756.34   49.63 6777.48   48.74
    6954   50.31    7014   45.49 7033.59   39.02 7044.52   40.22    7072   50.43
    7242   49.87 7255.79   47.52 7469.95   48.76 7504.48   49.42 7979.47   47.51
 8917.54   52.79 9080.23   52.83 9141.24   51.56 9350.18   52.94  9480.5   52.12
  9507.3   53.34 9621.88   52.4410772.96   54.26   11723    54.312764.06   56.43
#Mann= 5 ,-1 , 0
       0     .04       0  5997.3     .11       0    6954    .045       0
    7072     .11       0 7469.95     .04       0
#XS Ineff= 2 , 0
       0 3809.82   52.32 8918.08       0   52.79
Permanent Ineff=
       F       F
Bank Sta=6954,7072
XS Rating Curve= 0
Exp/Cntr=.5,.3

Type RM Length L Ch R = 1 ,14766.30,114.44,114.44,114.44
XS GIS Cut Line= 6
     3232152.948    13916761.503     3229656.553    13914205.382
     3227095.538    13911785.632     3226456.371    13911217.037
     3225117.396    13909976.081     3222672.689    13907727.908
#Sta/Elev= 30
       0   57.28  133.68   56.13  568.58   57.95  2525.2   53.04    3141   53.47
 3807.04   53.58 3850.53   51.92 5323.21   48.51 6304.77   48.11    7248   49.11
    7302   50.31    7362   45.49 7381.15   38.97 7392.39   40.08    7420   50.43
    7590   49.87 7593.12   48.01 7753.81   46.35 7800.59   48.11 8180.68      47
 9261.96   52.27 9526.76   51.7710184.49   54.5310302.81   53.24 10354.2   54.49
10778.51   53.6711318.83   54.0711357.12   55.1511751.27   53.5413098.63   56.08
#Mann= 6 ,-1 , 0
       0     .04       0    3141     .04       0 6304.77     .11       0
    7302    .045       0    7420     .11       0 7800.59     .04       0
#XS Ineff= 2 , 0
       0    7302    51.3    7461       0    51.3
Permanent Ineff=
       F       F
Bank Sta=7302,7420
XS Rating Curve= 0
Exp/Cntr=.5,.3

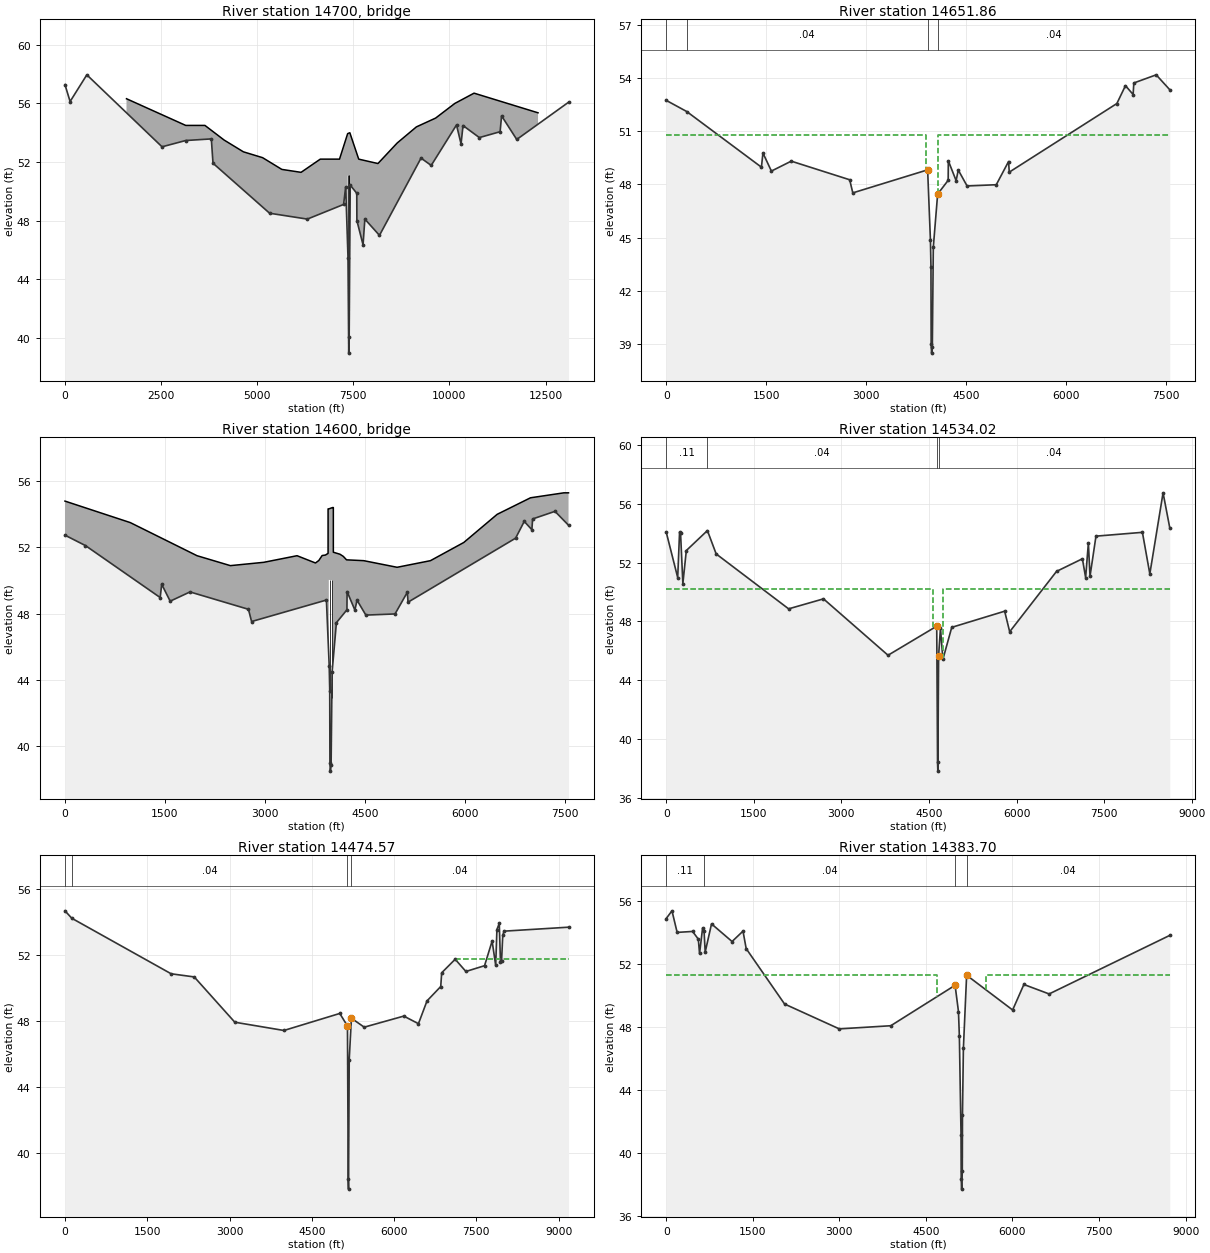
Type RM Length L Ch R = 3 ,14700   ,,,
BEGIN DESCRIPTION:
rail road bridge, north of 90A
END DESCRIPTION:
Bridge Culvert--1,0,-1,-1, 0
Deck Dist Width WeirC Skew NumUp NumDn MinLoCord MaxHiCord MaxSubmerge Is_Ogee
52,12,2.6,0, 22, 21, , , .95, 0, 0,0,,
 1600.09    3141    3641    4141    4641    5141    5641    6141    6641    7141
    7353    7353    7410    7410    7641    8141    8641    9141    9641   10141
   1064112305.27
   56.32    54.5    54.5    53.5    52.7    52.3    51.5    51.3    52.2    52.2
   53.94   53.94      54      54    52.2    51.9    53.3    54.4      55      56
    56.7   55.36
                                                                                
           51.07   51.13
                
    18.6     480     980    1480    1980    2480    2980    3480    3680    3957
    3957    4014    4014    4480    4980    5480    5980    6480    6980    7480
 7550.52
   52.85    54.5    53.5    52.7    52.3    51.5    51.3    52.2    52.2   53.94
   53.94      54      54    52.2    51.9    53.3    54.4      55      56    56.7
    56.7
                                                                                
   51.07   51.13
        
Pier Skew, UpSta & Num, DnSta & Num=  ,7367, 2 ,3971, 2 , 0 , 0 , 0 ,,
     1.4     1.4
      30      54
     1.4     1.4
      30      54
Pier Skew, UpSta & Num, DnSta & Num=  ,7381, 2 ,3985, 2 , 0 , 0 , 0 ,,
     1.4     1.4
      30      55
     1.4     1.4
      30      55
Pier Skew, UpSta & Num, DnSta & Num=  ,7397, 2 ,4001, 2 , 0 , 0 , 0 ,,
     1.4     1.4
      30      55
     1.4     1.4
      30      55
BR Coef=-1 , 1 , 1 ,.9, 0 ,,,.8,0,1.33,0,51.13
WSPro=,,,, 1 ,,,, 0 ,,,, 0 ,,,,-1 ,-1 ,-1 , 0 , 0 , 0 , 0 , 0
BR U #Sta/Elev= 30
       0   57.28  133.68   56.13  568.58   57.95  2525.2   53.04    3141   53.47
 3807.04   53.58 3850.53   51.92 5323.21   48.51 6304.77   48.11    7248   49.11
    7302   50.31    7362   45.49 7381.15   38.97 7392.39   40.08    7420   50.43
    7590   49.87 7593.12   48.01 7753.81   46.35 7800.59   48.11 8180.68      47
 9261.96   52.27 9526.76   51.7710184.49   54.5310302.81   53.24 10354.2   54.49
10778.51   53.6711318.83   54.0711357.12   55.1511751.27   53.5413098.63   56.08
BR U #Mann= 6
       0     .04    3141     .04 6304.77     .11    7302    .044    7420     .11
 7800.59     .04
BR D #Sta/Elev= 30
       0   52.74  307.65   52.11 1427.77   48.97 1450.53   49.77 1577.41   48.75
 1874.86   49.31 2751.13   48.26 2797.93   47.52    3920   48.82    3962   44.85
    3970   43.32 3972.68   38.99 3979.54   38.48 3990.34   38.84    4005   44.45
    4070   47.45    4228   48.23 4230.25   49.33 4347.26   48.21 4379.17   48.81
 4511.48   47.91 4949.28   47.98 5133.41   49.29 5144.03   48.69  6757.2   52.56
 6886.35   53.57 7001.17   53.07 7011.78   53.72 7347.22   54.18 7550.52   53.34
BR D #Mann= 4
       0     .04  307.65     .04    3920    .044    4070     .04
BC Design=,, 0 ,, 0 ,,,,,,

Type RM Length L Ch R = 1 ,14651.86,117.83,117.83,117.83
XS GIS Cut Line= 6
     3229839.176    13914290.816     3228630.308    13913100.264
     3227146.537    13911686.512     3226782.545    13911341.511
     3225372.781    13910066.006     3224369.225    13909087.628
#Sta/Elev= 30
       0   52.74  307.65   52.11 1427.77   48.97 1450.53   49.77 1577.41   48.75
 1874.86   49.31 2751.13   48.26 2797.93   47.52    3920   48.82    3962   44.85
    3970   43.32 3972.68   38.99 3979.54   38.48 3990.34   38.84    4005   44.45
    4070   47.45    4228   48.23 4230.25   49.33 4347.26   48.21 4379.17   48.81
 4511.48   47.91 4949.28   47.98 5133.41   49.29 5144.03   48.69  6757.2   52.56
 6886.35   53.57 7001.17   53.07 7011.78   53.72 7347.22   54.18 7550.52   53.34
#Mann= 4 ,-1 , 0
       0     .04       0  307.65     .04       0    3920    .045       0
    4070     .04       0
#XS Ineff= 2 , 0
       0    3900    50.8    4070       0    50.8
Permanent Ineff=
       F       F
Bank Sta=3920,4070
XS Rating Curve= 0
Exp/Cntr=.5,.3

Type RM Length L Ch R = 3 ,14600   ,,,
BEGIN DESCRIPTION:
90A west bound concrete bridge, 501/502  rail
END DESCRIPTION:
Bridge Culvert--1,0,-1,-1, 0
Deck Dist Width WeirC Skew NumUp NumDn MinLoCord MaxHiCord MaxSubmerge Is_Ogee
37,43,2.6,0, 30, 32, , , .95, 0, 0,0,,
       0     980    1980    2480    2980    3480    3756    3806    3856    3905
    3945    3945    3956    3956    4013    4013    4024    4024    4073    4123
    4173    4222    4480    4980    5480    5980    6480    6980    7480 7550.52
    54.8    53.5    51.5    50.9    51.1    51.5   51.06   51.21   51.51   51.54
   51.64   54.33   54.33   54.33   54.41   54.41   54.41   51.71   51.65   51.59
   51.46   51.25    51.2    50.8    51.2    52.3      54      55    55.3    55.3
                                                                                
                           50.04   50.01
                                                                                
       0    1645    2645    3145    3645    4145    4421    4471    4521    4570
    4610    4610    4621    4621    4678    4678    4689    4689    4738    4788
    4838    4887    4942    4992    5492    5992    6492    6992    7492    8492
 8509.16 8623.86
    54.8    53.5    51.5    50.9    51.1    51.5   51.06   51.21   51.51   51.54
   51.64   54.33   54.33   54.33   54.41   54.41   54.41   51.71   51.65   51.59
   51.46   51.25    51.2    50.8    51.2    52.3      54      55    55.3    56.8
   56.76   56.76
                                                                                
                           50.04   50.01
                                                                                
                
Pier Skew, UpSta & Num, DnSta & Num=  ,3970, 2 ,4635, 2 , 0 , 0 , 0 ,,
     1.4     1.4
      30      55
     1.4     1.4
      30      55
Pier Skew, UpSta & Num, DnSta & Num=  ,4001, 2 ,4665, 2 , 0 , 0 , 0 ,,
     1.4     1.4
      30      55
     1.4     1.4
      30      55
BR Coef=-1 , 1 , 1 ,1.05, 0 ,,,.8,0,1.2,0,50.8
WSPro=,,,, 1 ,,,, 0 ,,,, 0 ,,,,-1 ,-1 ,-1 , 0 , 0 , 0 , 0 , 0
BR U #Sta/Elev= 30
       0   52.74  307.65   52.11 1427.77   48.97 1450.53   49.77 1577.41   48.75
 1874.86   49.31 2751.13   48.26 2797.93   47.52    3920   48.82    3962   44.85
    3970   43.32 3972.68   38.99 3979.54   38.48 3990.34   38.84    4005   44.45
    4070   47.45    4228   48.23 4230.25   49.33 4347.26   48.21 4379.17   48.81
 4511.48   47.91 4949.28   47.98 5133.41   49.29 5144.03   48.69  6757.2   52.56
 6886.35   53.57 7001.17   53.07 7011.78   53.72 7347.22   54.18 7550.52   53.34
BR U #Mann= 4
       0     .04  307.65     .04    3920    .044    4070     .04
BR D #Sta/Elev= 30
       0   54.09  197.02   50.99  228.94   54.08  246.02   54.01  285.43   50.58
  344.54   52.83  705.72   54.19  855.78    52.6 2096.66   48.86 2693.69   49.54
 3799.05    45.7    4633   47.68    4647    38.4    4652   37.81    4665   45.65
    4697   47.55 4738.58   45.42 4890.13    47.6 5796.41    48.7 5882.37    47.3
 6684.71   51.41 7127.74   52.27 7183.07   50.99 7230.02   53.34 7258.29   51.08
 7360.17   53.81 8155.48   54.07 8282.38   51.24 8509.16   56.76 8623.86   54.38
BR D #Mann= 4
       0     .11  705.72     .04    4633    .044    4665     .04
BC Design=,, 0 ,, 0 ,,,,,,

Type RM Length L Ch R = 1 ,14534.02,59.46,59.46,59.46
XS GIS Cut Line= 6
     3230423.847    13914600.584     3229905.853     13914152.32
     3227634.647    13912010.612     3225134.327    13909609.908
     3224576.487    13908942.492     3224227.837    13908613.764
#Sta/Elev= 30
       0   54.09  197.02   50.99  228.94   54.08  246.02   54.01  285.43   50.58
  344.54   52.83  705.72   54.19  855.78    52.6 2096.66   48.86 2693.69   49.54
 3799.05    45.7    4633   47.68    4647    38.4    4652   37.81    4665   45.65
    4697   47.55 4738.58   45.42 4890.13    47.6 5796.41    48.7 5882.37    47.3
 6684.71   51.41 7127.74   52.27 7183.07   50.99 7230.02   53.34 7258.29   51.08
 7360.17   53.81 8155.48   54.07 8282.38   51.24 8509.16   56.76 8623.86   54.38
#Mann= 4 ,-1 , 0
       0     .11       0  705.72     .04       0    4633    .045       0
    4665     .04       0
#XS Ineff= 2 , 0
       0    4572    50.2    4742       0    50.2
Permanent Ineff=
       F       F
Bank Sta=4633,4665
XS Rating Curve= 0
Exp/Cntr=.5,.3

Type RM Length L Ch R = 1 ,14474.57,90.87,90.87,90.87
XS GIS Cut Line= 5
     3230852.546    13914883.486     3229607.171    13913796.279
     3227209.841    13911483.942     3227023.096    13911341.511
     3224288.275    13908475.794
#Sta/Elev= 30
       0   54.65  124.73    54.2 1935.77   50.84  2356.7   50.65 3096.28   47.91
 3991.35   47.41 5009.86   48.44    5150   47.68    5164    38.4    5169   37.81
    5182   45.65    5222   48.15 5455.41   47.61 6176.85   48.28 6444.05   47.82
 6600.16    49.2 6850.44   50.07  6867.4    50.9 7113.56   51.72  7309.1   50.98
 7649.08   51.33  7787.1   52.82 7852.28   51.35 7874.37   53.52 7917.46   53.89
 7939.18   51.57 7959.25   51.62 7981.18   53.17 8004.36   53.42 9180.07   53.66
#Mann= 4 ,-1 , 0
       0     .11       0  124.73     .04       0    5150    .045       0
    5222     .04       0
#XS Ineff= 2 , 0
       0                 7149.02       0   51.75
Permanent Ineff=
       F       F
Bank Sta=5150,5222
XS Rating Curve= 0
Exp/Cntr=.5,.3

Type RM Length L Ch R = 1 ,14383.70,154.45,154.45,154.45
XS GIS Cut Line= 6
     3230827.324    13914746.197     3228891.856    13913068.104
      3227392.67    13911596.365     3227266.813    13911461.786
     3226909.151    13911097.794     3224572.037    13908671.295
#Sta/Elev= 30
       0   54.91  100.09    55.4  189.64   54.03  457.44   54.09   556.6    53.6
  577.87   52.69  631.03   54.31  655.97   54.12  675.83   52.78  785.45   54.57
 1141.44   53.45 1330.97   54.11 1386.01      53 2051.19   49.48 2999.41    47.9
 3891.51    48.1 5006.05   50.67 5064.65      49 5080.29   47.42    5109   41.18
    5112   38.34    5120   37.72    5131   38.87    5134   42.43    5150   46.67
    5206   51.31 6003.25    49.1 6198.02   50.72  6635.6   50.12 8726.04   53.84
#Mann= 4 ,-1 , 0
       0     .11       0  655.97     .04       0 5006.05    .045       0
    5206     .04       0
#XS Ineff= 2 , 0
       0    4690    51.3    5550       0    51.3
Permanent Ineff=
       F       F
Bank Sta=5006.05,5206
XS Rating Curve= 0
Exp/Cntr=.5,.3

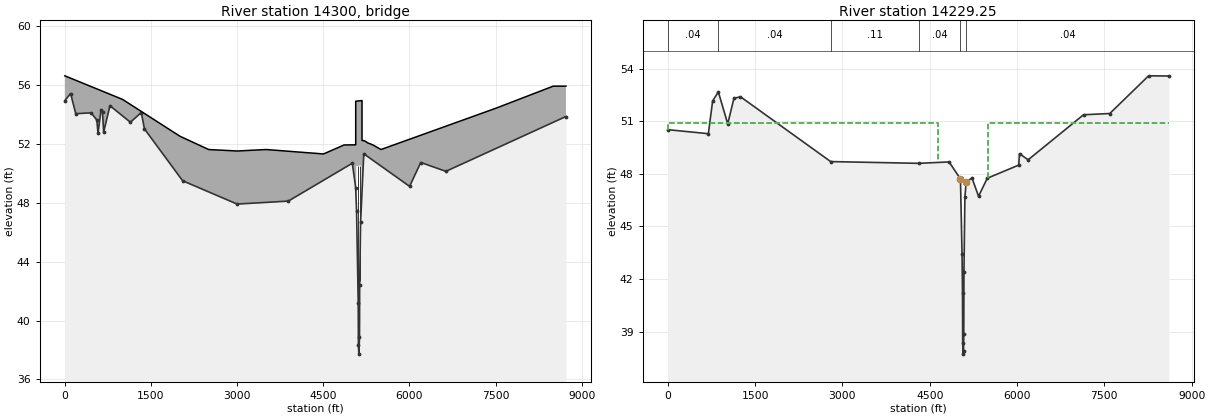
Type RM Length L Ch R = 3 ,14300   ,,,
BEGIN DESCRIPTION:
90A east bound concrete bridge, 501/502 rail
END DESCRIPTION:
Bridge Culvert--1,0,-1,-1, 0
Deck Dist Width WeirC Skew NumUp NumDn MinLoCord MaxHiCord MaxSubmerge Is_Ogee
56,43,2.6,0, 25, 25, , , .95, 0, 0,0,,
       0    1005    2005    2505    3005    3505    4505    4863    5065    5065
    5075    5075    5165    5165    5175    5175    5224    5278    5330    5383
    5505    6505    7505    8505 8726.04
    56.6      55    52.5    51.6    51.5    51.6    51.3   51.91   51.92   54.88
   54.88   54.88   54.92   54.92   54.92   52.22   52.18   52.04   51.97   51.87
    51.6      53    54.4    55.9    55.9
                                                                                
           50.48   50.52
                                        
       0     994    1994    2494    2994    3494    4494    4817    5019    5019
    5029    5029    5119    5119    5129    5129    5178    5232    5284    5337
    5494    6494    7494    8494 8606.86
    56.6      55    52.5    51.6    51.5    51.6    51.3   51.91   51.92   54.88
   54.88   54.88   54.92   54.92   54.92   52.22   52.18   52.04   51.97   51.87
    51.6      53    54.4    55.9    55.9
                                                                                
           50.48   50.52
                                        
Pier Skew, UpSta & Num, DnSta & Num=  ,5105, 2 ,5059, 2 , 0 , 0 , 0 ,,
     1.4     1.4
      30      55
     1.4     1.4
      30      55
Pier Skew, UpSta & Num, DnSta & Num=  ,5135, 2 ,5089, 2 , 0 , 0 , 0 ,,
     1.4     1.4
      30      55
     1.4     1.4
      30      55
BR Coef=-1 , 1 , 1 ,1.05, 0 ,,,.8,0,1.2,0,51.3
WSPro=,,,, 1 ,,,, 0 ,,,, 0 ,,,,-1 ,-1 ,-1 , 0 , 0 , 0 , 0 , 0
BR U #Sta/Elev= 30
       0   54.91  100.09    55.4  189.64   54.03  457.44   54.09   556.6    53.6
  577.87   52.69  631.03   54.31  655.97   54.12  675.83   52.78  785.45   54.57
 1141.44   53.45 1330.97   54.11 1386.01      53 2051.19   49.48 2999.41    47.9
 3891.51    48.1 5006.05   50.67 5064.65      49 5080.29   47.42    5109   41.18
    5112   38.34    5120   37.72    5131   38.87    5134   42.43    5150   46.67
    5206   51.31 6003.25    49.1 6198.02   50.72  6635.6   50.12 8726.04   53.84
BR U #Mann= 4
       0     .11  655.97     .04 5006.05    .044    5206     .04
BR D #Sta/Elev= 30
       0   50.52  697.59   50.29  771.31   52.16  869.56   52.67 1030.33   50.85
 1136.34    52.3 1247.86    52.4 2798.63    48.7 4312.21    48.6 4832.47   48.68
  5027.7   47.71    5055   43.42    5063   41.18    5066   38.34    5074   37.72
    5080   37.87    5085   38.87    5088   42.43    5104   46.67 5126.11   47.55
 5226.13   47.76 5338.43   46.72 5488.38   47.75 6028.99    48.5 6041.93   49.15
 6190.12    48.8 7141.62   51.37 7592.07   51.44 8259.31   53.59 8606.86   53.58
BR D #Mann= 6
       0     .04  869.56     .04 2798.63     .11 4312.21     .04  5027.7    .044
 5126.11     .04
BC Design=,, 0 ,, 0 ,,,,,,

Type RM Length L Ch R = 1 ,14229.25,150.03,150.03,150.03
XS GIS Cut Line= 6
     3231057.303    13914341.482     3229473.238    13913253.981
     3227359.631    13911378.527      3227010.34    13910981.057
     3226532.666    13910409.554     3225191.615     13908198.77
#Sta/Elev= 30
       0   50.52  697.59   50.29  771.31   52.16  869.56   52.67 1030.33   50.85
 1136.34    52.3 1247.86    52.4 2798.63    48.7 4312.21    48.6 4832.47   48.68
  5027.7   47.71    5055   43.42    5063   41.18    5066   38.34    5074   37.72
    5080   37.87    5085   38.87    5088   42.43    5104   46.67 5126.11   47.55
 5226.13   47.76 5338.43   46.72 5488.38   47.75 6028.99    48.5 6041.93   49.15
 6190.12    48.8 7141.62   51.37 7592.07   51.44 8259.31   53.59 8606.86   53.58
#Mann= 6 ,-1 , 0
       0     .04       0  869.56     .04       0 2798.63     .11       0
 4312.21     .04       0  5027.7    .045       0 5126.11     .04       0
#XS Ineff= 2 , 0
       0    4644    50.9    5504       0    50.9
Permanent Ineff=
       F       F
Bank Sta=5027.7,5126.11
XS Rating Curve= 0
Exp/Cntr=.5,.3