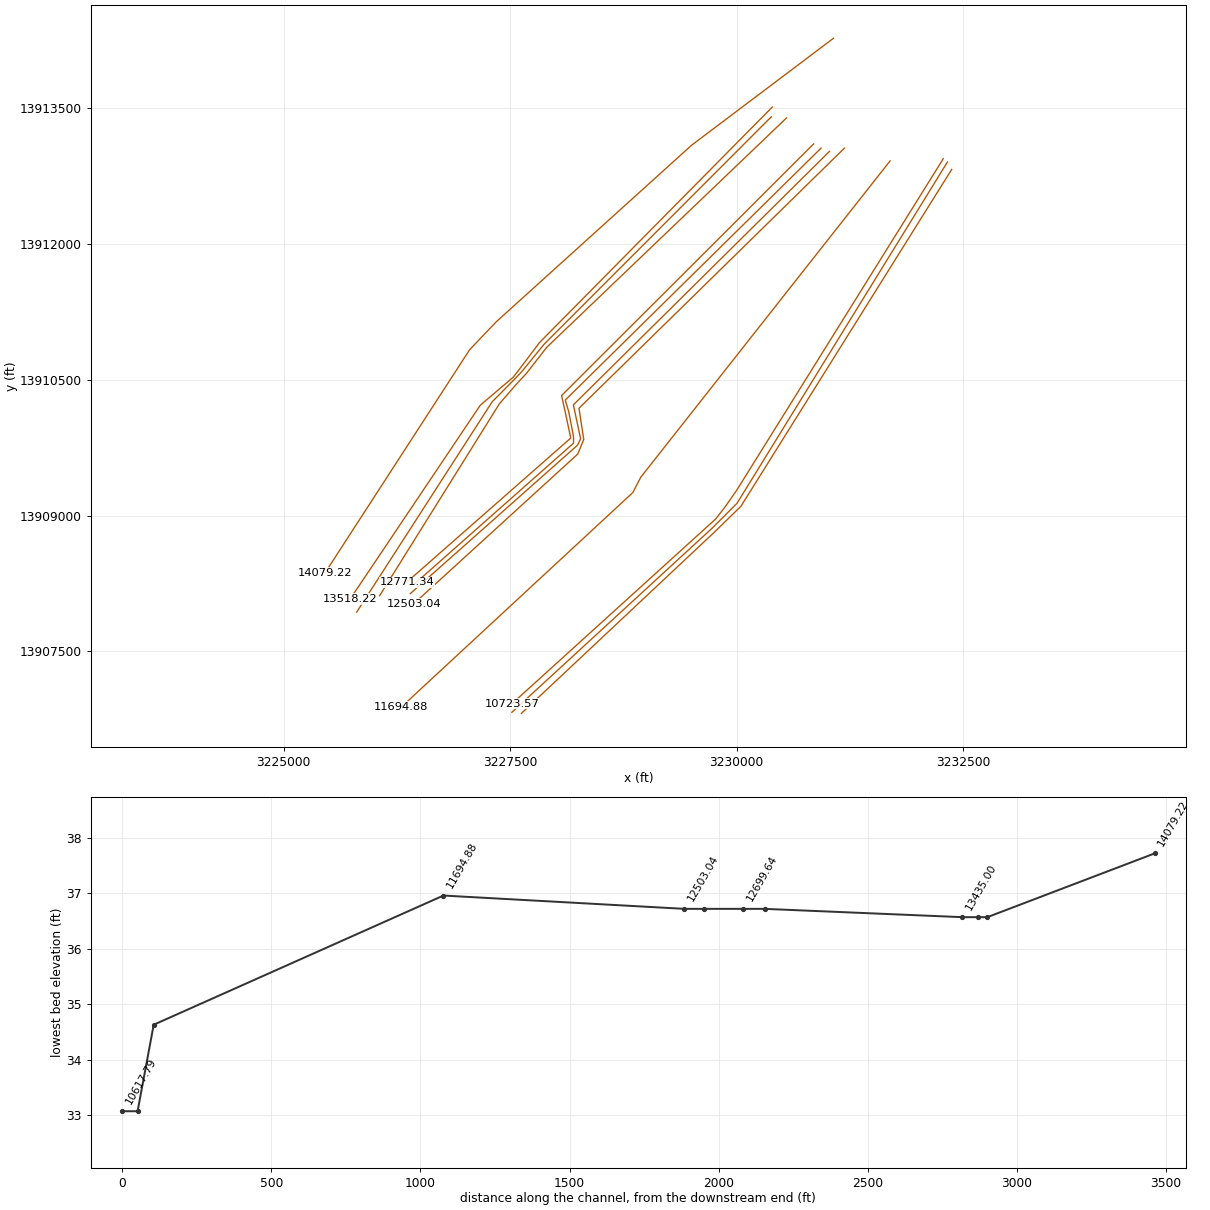
HEC-RAS study Q128-00-00.prj: Q128-00-00

--- Q128-00-00.g05 (geometry) --- (continued)

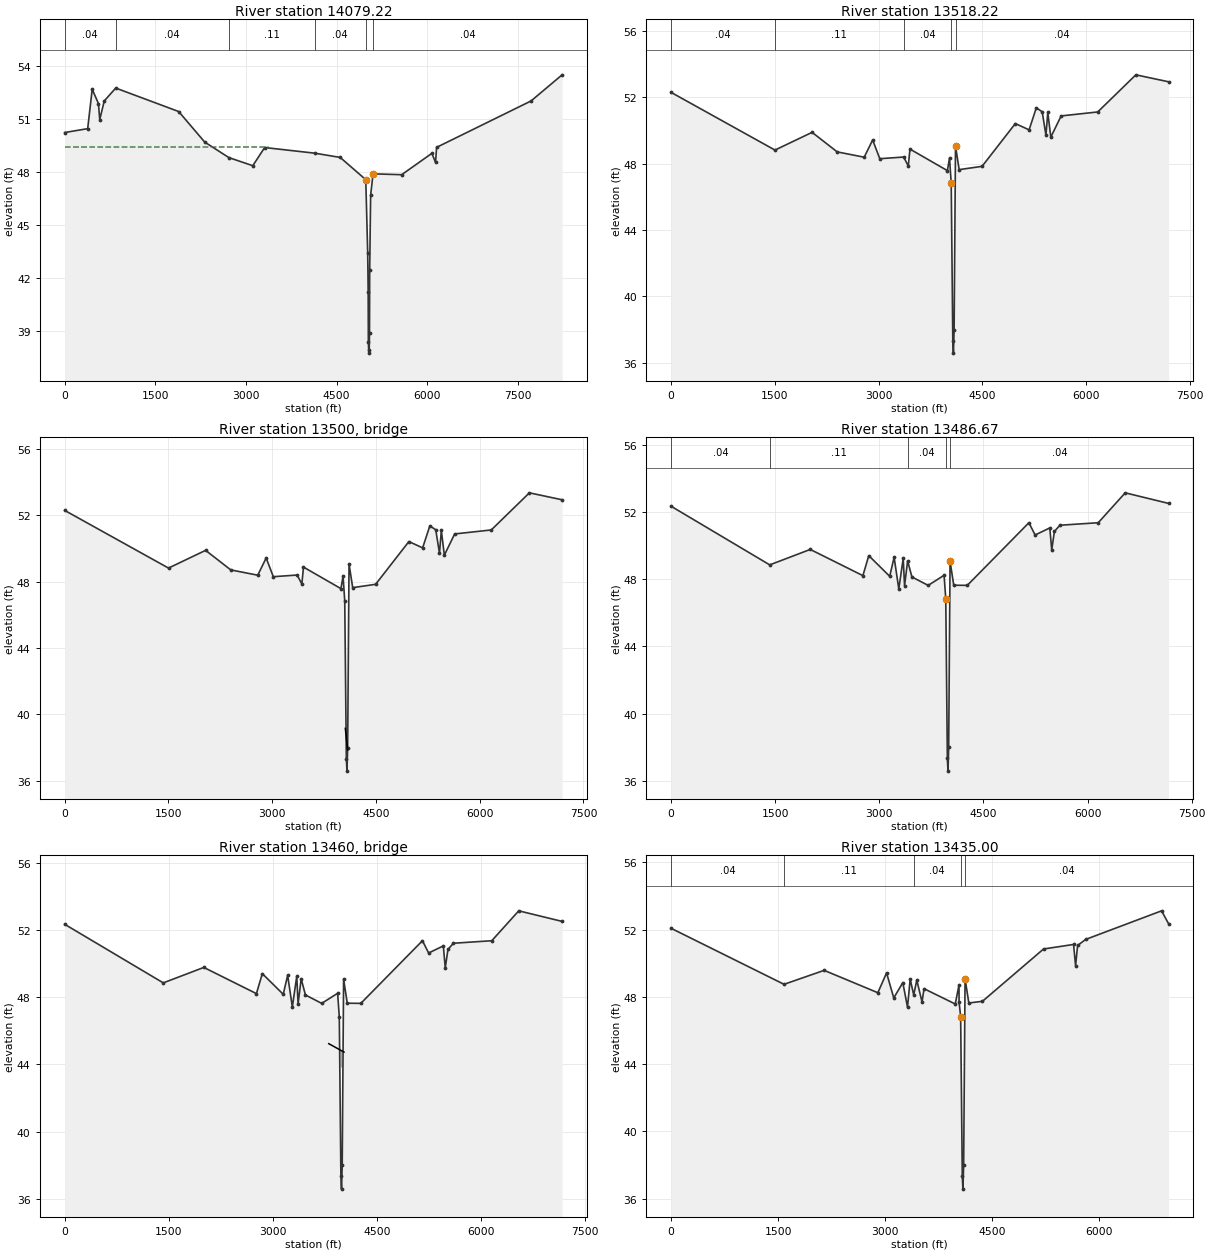
Type RM Length L Ch R = 1 ,14079.22,561.01,561.01,561.01
BEGIN DESCRIPTION:
Section M -
END DESCRIPTION:
XS GIS Cut Line= 5
     3231069.348    13914269.215     3229503.558     13913088.85
      3227347.96    13911140.559     3227053.672    13910832.032
     3225456.595    13908367.393
#Sta/Elev= 30
       0   50.22  380.89   50.44  455.64   52.67   559.2   51.86  580.23   50.95
  654.99   52.01  844.65   52.74 1886.44   51.41 2316.47   49.68 2716.74    48.8
 3112.48   48.34 3308.42   49.37 4137.39   49.05  4557.9   48.81 4981.49   47.55
    5013   43.42    5021   41.18    5024   38.34    5032   37.72    5038   37.87
    5043   38.87    5046   42.43    5062   46.67 5101.79   47.88 5575.05   47.83
 6074.33   49.04 6135.47   48.53 6153.14   49.38 7715.88   52.01 8229.67   53.49
#Mann= 6 ,-1 , 0
       0     .04       0  844.65     .04       0 2716.74     .11       0
 4137.39     .04       0 4981.49    .045       0 5101.79     .04       0
#XS Ineff= 2 , 0
       0 3366.76   49.39               0
Permanent Ineff=
       F       F
Bank Sta=4981.49,5101.79
XS Rating Curve= 0
Exp/Cntr=.5,.3

Type RM Length L Ch R = 1 ,13518.22,31.54,31.54,31.54
XS GIS Cut Line= 6
     3230394.854    13913510.409       3227825.8    13910911.483
     3227594.516    13910605.032      3227532.57    13910525.742
     3227170.806     13910218.49     3225733.619    13908078.325
#Sta/Elev= 30
       0    52.3 1501.13   48.82 2037.76   49.89  2401.1   48.71 2791.25   48.39
 2913.23   49.43 3016.29    48.3 3361.35    48.4 3428.57   47.86 3452.69   48.88
 3993.94   47.58 4024.41   48.34    4049   46.83    4072   37.33    4081   36.57
    4091   37.99    4111   49.07    4164   47.64 4495.08   47.84 4976.21   50.42
 5174.96   50.04 5279.34   51.37 5364.52   51.13 5418.33   49.72 5445.24   51.09
 5488.92    49.6 5638.12   50.88  6167.2   51.12 6718.37   53.36  7191.5   52.94
#Mann= 5 ,-1 , 0
       0     .04       0 1501.13     .11       0 3361.35     .04       0
    4049    .045       0    4111     .04       0
#XS Ineff= 2 , 0
       0 2037.76   49.89               0
Permanent Ineff=
       F       F
Bank Sta=4049,4111
XS Rating Curve= 0
Exp/Cntr=.5,.3

Type RM Length L Ch R = 3 ,13500   ,,,
BEGIN DESCRIPTION:
1' gas pipe crossing (approx 800' S 90A)
END DESCRIPTION:
Bridge Culvert--1,0,-1,-1, 0
Deck Dist Width WeirC Skew NumUp NumDn MinLoCord MaxHiCord MaxSubmerge Is_Ogee
15,1,2.6,0, 2, 2, , , .95, 0, 0,0,,
    4057    4091
   39.15   37.85
   38.15   36.93
    3975    4005
   39.15   37.93
   38.15   36.93
BR Coef=-1 , 0 , 0 ,, 0 ,,,.8,-1,,0,
WSPro=,,,, 1 ,,,, 0 ,,,, 0 ,,,,-1 ,-1 ,-1 , 0 , 0 , 0 , 0 , 0
BR U #Sta/Elev= 30
       0    52.3 1501.13   48.82 2037.76   49.89  2401.1   48.71 2791.25   48.39
 2913.23   49.43 3016.29    48.3 3361.35    48.4 3428.57   47.86 3452.69   48.88
 3993.94   47.58 4024.41   48.34    4049   46.83    4072   37.33    4081   36.57
    4091   37.99    4111   49.07    4164   47.64 4495.08   47.84 4976.21   50.42
 5174.96   50.04 5279.34   51.37 5364.52   51.13 5418.33   49.72 5445.24   51.09
 5488.92    49.6 5638.12   50.88  6167.2   51.12 6718.37   53.36  7191.5   52.94
BR U #Mann= 5
       0     .04 1501.13     .11 3361.35     .04    4049    .044    4111     .04
BR D #Sta/Elev= 30
       0   52.34 1420.75   48.85 2004.88   49.77 2763.01   48.21 2847.86    49.4
 3149.28   48.17 3212.94    49.3 3280.36   47.42 3343.97   49.24 3363.34   47.61
 3407.58   49.09  3469.4   48.13 3703.55   47.63 3932.87   48.23    3957   46.83
    3980   37.33    3989   36.57    3999   37.99    4019   49.07    4072   47.64
 4266.97   47.63 5154.96   51.36 5244.18   50.63 5455.99   51.05 5483.69   49.74
  5522.5   50.84 5601.03   51.21 6154.16   51.36  6542.6   53.14 7167.56   52.51
BR D #Mann= 5
       0     .04 1420.75     .11 3407.58     .04    3957    .044    4019     .04
BC Design=,, 0 ,, 0 ,,,,,,

Type RM Length L Ch R = 1 ,13486.67,51.67,51.67,51.67
XS GIS Cut Line= 6
     3230382.809    13913402.008     3227877.565    13910894.497
     3227631.684    13910592.643     3227549.915    13910505.919
     3227301.728    13910255.907     3225805.887     13907933.79
#Sta/Elev= 30
       0   52.34 1420.75   48.85 2004.88   49.77 2763.01   48.21 2847.86    49.4
 3149.28   48.17 3212.94    49.3 3280.36   47.42 3343.97   49.24 3363.34   47.61
 3407.58   49.09  3469.4   48.13 3703.55   47.63 3932.87   48.23    3957   46.83
    3980   37.33    3989   36.57    3999   37.99    4019   49.07    4072   47.64
 4266.97   47.63 5154.96   51.36 5244.18   50.63 5455.99   51.05 5483.69   49.74
  5522.5   50.84 5601.03   51.21 6154.16   51.36  6542.6   53.14 7167.56   52.51
#Mann= 5 ,-1 , 0
       0     .04       0 1420.75     .11       0 3407.58     .04       0
    3957    .045       0    4019     .04       0
#XS Ineff= 2 , 0
       0 2847.86    49.4               0
Permanent Ineff=
       F       F
Bank Sta=3957,4019
XS Rating Curve= 0
Exp/Cntr=.5,.3

Type RM Length L Ch R = 3 ,13460   ,,,
BEGIN DESCRIPTION:
1' gas pipe crossing (approx 850' S 90A)
END DESCRIPTION:
Bridge Culvert--1,0,-1,-1, 0
Deck Dist Width WeirC Skew NumUp NumDn MinLoCord MaxHiCord MaxSubmerge Is_Ogee
25,1,2.6,0, 2, 2, , , .95, 0, 0,0,,
    3805    4025
   45.23   44.73
   44.23   43.73
    4062    4122
   45.23   44.73
   44.23   43.73
BR Coef=-1 , 0 , 0 ,, 0 ,,,.8,-1,,0,
WSPro=,,,, 1 ,,,, 0 ,,,, 0 ,,,,-1 ,-1 ,-1 , 0 , 0 , 0 , 0 , 0
BR U #Sta/Elev= 30
       0   52.34 1420.75   48.85 2004.88   49.77 2763.01   48.21 2847.86    49.4
 3149.28   48.17 3212.94    49.3 3280.36   47.42 3343.97   49.24 3363.34   47.61
 3407.58   49.09  3469.4   48.13 3703.55   47.63 3932.87   48.23    3957   46.83
    3980   37.33    3989   36.57    3999   37.99    4019   49.07    4072   47.64
 4266.97   47.63 5154.96   51.36 5244.18   50.63 5455.99   51.05 5483.69   49.74
  5522.5   50.84 5601.03   51.21 6154.16   51.36  6542.6   53.14 7167.56   52.51
BR U #Mann= 5
       0     .04 1420.75     .11 3407.58     .04    3957    .044    4019     .04
BR D #Sta/Elev= 30
       0   52.08 1583.47   48.75 2145.76   49.58 2899.01   48.25 3021.27   49.43
  3121.8   47.94 3249.11   48.85 3314.74   47.39  3352.4   49.06 3401.53   48.12
 3444.93      49 3518.47    47.7 3546.17   48.49 3984.25   47.58 4036.93   48.71
    4038   47.69    4060   46.83    4083   37.33    4092   36.57    4102   37.99
    4122   49.07    4175   47.64 4365.79   47.74 5222.23   50.85 5643.41   51.12
 5671.74   49.85 5700.07   51.06 5813.38   51.42 6877.68   53.12 6976.01   52.35
BR D #Mann= 5
       0     .04 1583.47     .11 3401.53     .04    4060    .044    4122     .04
BC Design=,, 0 ,, 0 ,,,,,,

Type RM Length L Ch R = 1 ,13435.00,550,663.67,750
XS GIS Cut Line= 6
     3230551.433    13913389.964     3227903.341    13910856.609
     3227678.763    13910567.865     3227592.038    13910476.185
      3227382.57    13910235.296     3226058.822    13908114.458
#Sta/Elev= 30
       0   52.08 1583.47   48.75 2145.76   49.58 2899.01   48.25 3021.27   49.43
  3121.8   47.94 3249.11   48.85 3314.74   47.39  3352.4   49.06 3401.53   48.12
 3444.93      49 3518.47    47.7 3546.17   48.49 3984.25   47.58 4036.93   48.71
    4038   47.69    4060   46.83    4083   37.33    4092   36.57    4102   37.99
    4122   49.07    4175   47.64 4365.79   47.74 5222.23   50.85 5643.41   51.12
 5671.74   49.85 5700.07   51.06 5813.38   51.42 6877.68   53.12 6976.01   52.35
#Mann= 5 ,-1 , 0
       0     .04       0 1583.47     .11       0 3401.53     .04       0
    4060    .045       0    4122     .04       0
#XS Ineff= 2 , 0
       0 3021.27   49.41               0
Permanent Ineff=
       F       F
Bank Sta=4060,4122
XS Rating Curve= 0
Exp/Cntr=.5,.3

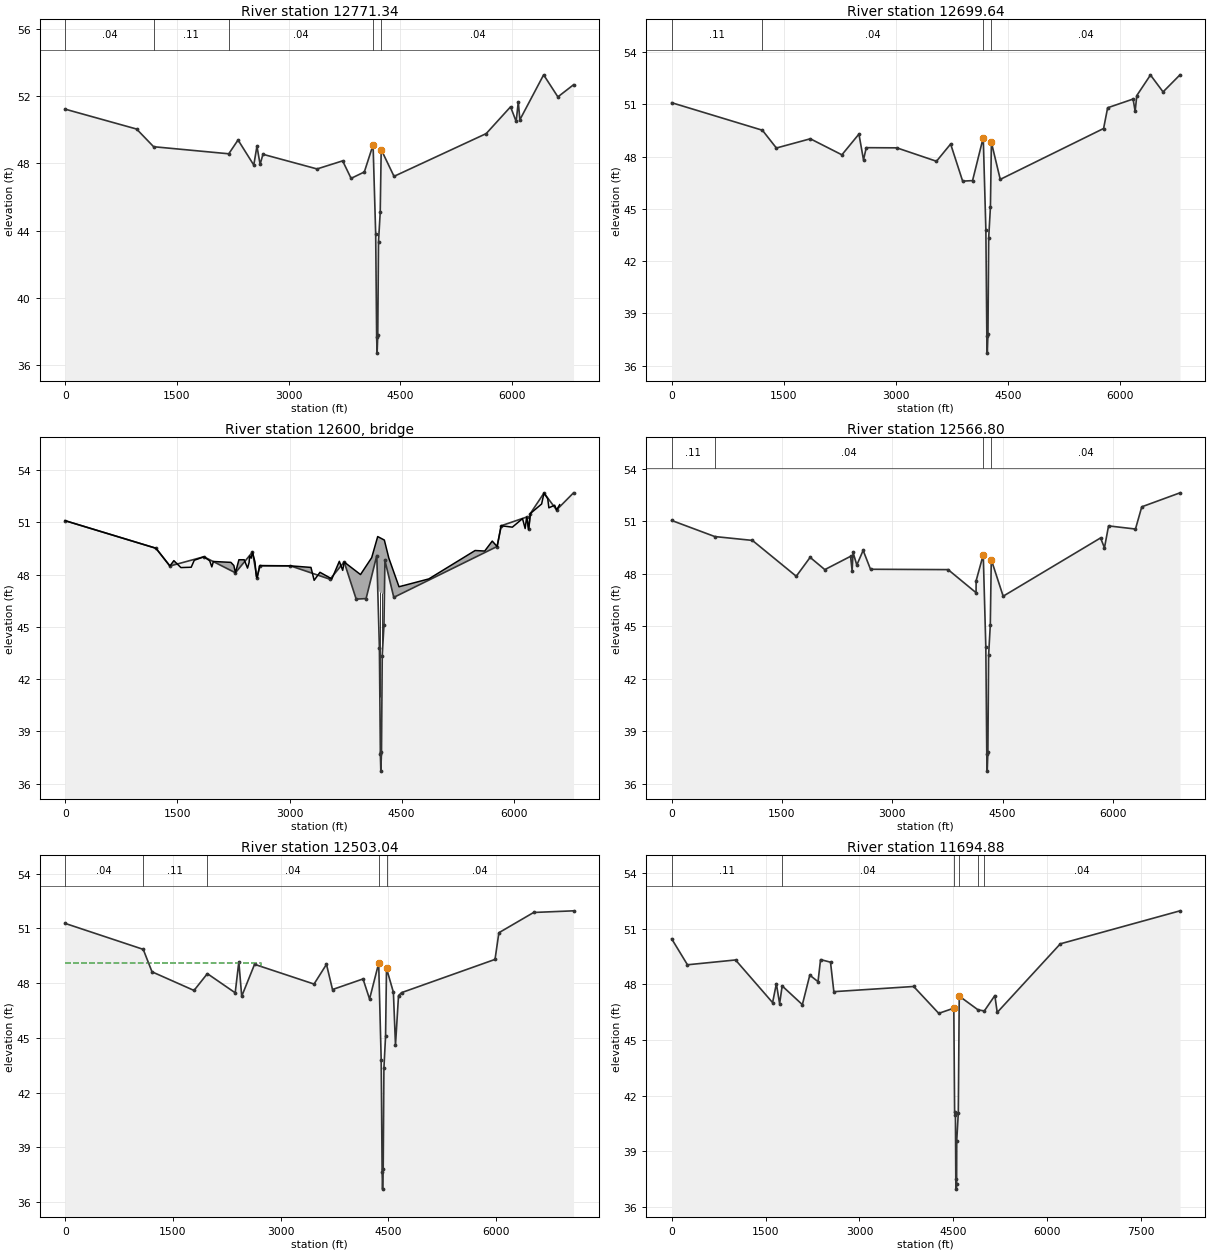
Type RM Length L Ch R = 1 ,12771.34,71.7,71.7,71.7
BEGIN DESCRIPTION:
Section L -  XS' central segment is manually adjusted for a skewed angle of 55 degree.  Skew option was not used because the skewed segment is small portion of entire XS which is NOT skewed.
END DESCRIPTION:
XS GIS Cut Line= 5
     3230850.941    13913103.607     3228068.152    13910324.831
     3228109.314     13910138.23     3228169.685    13909855.583
     3226359.597    13908265.006
#Sta/Elev= 30
       0   51.21 958.021   50.031186.641   48.98 2195.16   48.56  2319.7   49.38
 2530.92   47.89 2573.38   49.01 2615.84   47.93 2653.96   48.533380.061   47.66
3723.471   48.14 3836.94    47.1 4014.52   47.48    4132   49.09    4167    43.8
    4180   37.68    4186   36.72    4195    37.8    4205   43.35    4228    45.1
    4241   48.81 4413.17   47.225650.471   49.76 5977.13   51.356052.331   50.48
 6080.93   51.646102.189   50.586421.051   53.256612.361   51.94 6822.37   52.66
#Mann= 5 ,-1 , 0
       0     .04       01186.641     .11       0 2195.16     .04       0
    4132    .045       0    4241     .04       0
#XS Ineff= 2 , 0
       0 2573.38   49.01               0
Permanent Ineff=
       F       F
Bank Sta=4132,4241
XS Rating Curve= 0
Exp/Cntr=.5,.3

Type RM Length L Ch R = 1 ,12699.64,132.84,132.84,132.84
BEGIN DESCRIPTION:
 XS' central segment is manually adjusted for a skewed angle of 55 degree.  Skew option was not used because the skewed segment is small portion of entire XS which is NOT skewed.
END DESCRIPTION:
XS GIS Cut Line= 6
     3230933.063     13913056.68     3228109.314    13910275.437
     3228147.732    13910143.718     3228199.871    13909872.048
     3228200.117    13909798.938     3226442.188    13908242.481
#Sta/Elev= 30
       0   51.091213.509   49.511400.191   48.49 1854.32   49.02 2276.51    48.1
2504.399   49.29 2565.54   47.81 2602.47   48.513011.371    48.5 3541.38   47.73
 3730.77   48.723891.411   46.594024.021   46.62    4167   49.09    4202    43.8
    4215   37.68    4221   36.72    4230    37.8    4240   43.35    4263    45.1
    4276   48.81 4394.39   46.695776.474   49.61 5830.65    50.8 6171.23    51.3
6198.371   50.59  6220.5    51.5  6403.4   52.68 6571.92   51.71 6798.34   52.69
#Mann= 4 ,-1 , 0
       0     .11       01213.509     .04       0    4167    .045       0
    4276     .04       0
#XS Ineff= 2 , 0
       04145.997    47.6    4311       0    47.6
Permanent Ineff=
       F       F
Bank Sta=4167,4276
XS Rating Curve= 0
Exp/Cntr=.5,.3

Type RM Length L Ch R = 3 ,12600   ,,,
BEGIN DESCRIPTION:
Concrete bridge at Adlong School Road, bridge deck is manually skewed 55 degree only for the channel section NOT the overbank sections, bridge piers are NOT skewed.
END DESCRIPTION:
Bridge Culvert--1,0,-1,-1, 0
Deck Dist Width WeirC Skew NumUp NumDn MinLoCord MaxHiCord MaxSubmerge Is_Ogee
55.5,22,2.6,0, 60, 60, , , .95, 0, 0,0,,
       0  1213.5 1400.19 1453.02 1547.29 1685.17 1726.06 1854.32 1932.66 1960.71
 1981.77 2215.51 2255.46 2276.52 2323.08 2393.47 2438.26 2459.47    2466 2487.06
  2504.4 2538.35 2554.93 2565.55 2602.47 3011.38 3286.81 3329.23 3407.23 3566.21
  3666.1 3711.09 3730.78 3949.26 4098.96 4179.26 4179.26 4268.17 4268.17 4327.82
 4464.06 4862.77 5482.31 5610.27 5711.21 5776.47 5830.65 5980.12 6115.89  6151.2
 6171.23 6198.37  6220.5 6371.58  6403.4  6453.4 6468.47 6545.82 6571.92 6613.08
   51.09   49.51   48.49    48.8    48.4   48.42   48.82   49.02   48.79   48.44
   48.75    48.7   48.52    48.1   48.85   48.85   48.37   48.69   49.07   48.94
   49.29   48.72    47.9   47.81   48.51    48.5   48.41   47.67   48.13   47.75
   48.76   48.24   48.72      48   48.97   50.18   50.18   49.98   49.98   48.95
    47.3   47.75   49.38   49.35   49.92   49.61    50.8   50.72   51.21   50.64
    51.3   50.59    51.5   52.05   52.68   52.35   51.83   51.98   51.71   52.01
                                                                                
                                                                                
                                                                                
                                                   47.06   46.86
                                                                                
                                                                                
      54  454.96  517.18   980.8  1016.1 1097.42 1153.42 1186.39 1258.95 1693.76
  1882.3 2082.05 2258.47 2401.88 2432.03 2444.53 2453.24 2465.87 2516.88 2533.77
 2567.37 2603.09  2667.9 2703.19 3186.94 3276.19 3358.83 3510.75 3596.04 3638.68
 3681.35 3706.97 3757.87 3800.28 4018.26 4167.96 4248.26 4248.26 4337.17 4337.17
 4427.22    4754 4786.78    4933 5709.99 5810.43 5830.48 5883.95 5939.53 5965.42
  6238.2 6251.68 6284.17 6305.43 6326.68 6390.99 6561.54 6715.05 6870.27 6964.83
   51.05   50.11   50.39   50.06    49.7   49.91   49.67   49.04    49.4   47.86
   48.94   48.24   48.68    48.4      49   48.22   48.18   49.23    48.5   48.83
   48.71   49.34   49.03   48.26   48.48      48   48.35   47.86   48.37   47.69
   48.26   47.81   48.24   47.71      48   48.97   50.18   50.18   49.98   49.98
   48.67      47   47.74   47.61   49.59   49.44   50.05   49.49   50.74    50.4
   50.93   50.56   51.21   50.56   51.33   51.83   51.44    52.2   52.01   52.63
                                                                                
                                                                                
                                                                                
                                                           47.06   46.86
                                                                                
                                                                                
Pier Skew, UpSta & Num, DnSta & Num=  ,4208, 2 ,4277, 2 , 0 , 0 , 0 ,,
     1.3     1.3
      30      50
     1.3     1.3
      30      50
Pier Skew, UpSta & Num, DnSta & Num=  ,4240, 2 ,4309, 2 , 0 , 0 , 0 ,,
     1.3     1.3
      30      50
     1.3     1.3
      30      50
BR Coef=-1 , 1 , 1 ,1.05, 0 ,,,.8,0,1.2,0,47.06
WSPro=,,,, 1 ,,,, 0 ,,,, 0 ,,,,-1 ,-1 ,-1 , 0 , 0 , 0 , 0 , 0
BR U #Sta/Elev= 30
       0   51.09 1213.51   49.51 1400.19   48.49 1854.32   49.02 2276.51    48.1
  2504.4   49.29 2565.54   47.81 2602.47   48.51 3011.37    48.5 3541.38   47.73
 3730.77   48.72 3891.41   46.59 4024.02   46.62    4167   49.09    4202    43.8
    4215   37.68    4221   36.72    4230    37.8    4240   43.35    4263    45.1
    4276   48.81 4394.39   46.69 5776.47   49.61 5830.65    50.8 6171.23    51.3
 6198.37   50.59  6220.5    51.5  6403.4   52.68 6571.92   51.71 6798.34   52.69
BR U #Mann= 4
       0     .11 1213.51     .04    4167    .044    4276     .04
BR D #Sta/Elev= 30
       0   51.05  586.45   50.13 1097.41   49.91 1693.76   47.86  1882.3   48.94
 2082.05   48.24 2432.02      49 2453.24   48.18 2465.86   49.23 2516.88    48.5
 2603.09   49.34 2703.18   48.26 3757.87   48.24 4138.44   46.92    4139    47.6
    4236   49.09    4271    43.8    4284   37.68    4290   36.72    4299    37.8
    4309   43.35    4332    45.1    4345   48.81 4506.72   46.72 5830.48   50.05
 5883.95   49.49 5939.52   50.74 6305.42   50.56    6391   51.83 6910.83   52.63
BR D #Mann= 4
       0     .11  586.45     .04    4236    .044    4345     .04
BC Design=,, 0 ,, 0 ,,,,,,

Type RM Length L Ch R = 1 ,12566.80,63.75,63.75,63.75
BEGIN DESCRIPTION:
XS' central segment is manually adjusted for a skewed angle of 55 degree.  Skew option was not used because the skewed segment is small portion of entire XS which is NOT skewed.
END DESCRIPTION:
XS GIS Cut Line= 6
     3231026.916    13913021.485     3228198.538    13910222.364
     3228218.931     13910126.81     3228278.399    13909846.814
     3228244.364    13909777.088     3226397.138    13908137.366
#Sta/Elev= 30
       0   51.05  586.45   50.131097.409   49.911693.761   47.86  1882.3   48.94
 2082.05   48.24 2432.02      492453.241   48.18 2465.86   49.23 2516.88    48.5
 2603.09   49.34 2703.18   48.263757.871   48.244138.441   46.924139.001    47.6
    4236   49.09    4271    43.8    4284   37.68    4290   36.72    4299    37.8
    4309   43.35    4332    45.1    4345   48.81 4506.72   46.72 5830.48   50.05
 5883.95   49.495939.521   50.74 6305.42   50.56    6391   51.83 6910.83   52.63
#Mann= 4 ,-1 , 0
       0     .11       0  586.45     .04       0    4236    .045       0
    4345     .04       0
#XS Ineff= 2 , 0
       0    4215    47.1    4370       0    47.1
Permanent Ineff=
       F       F
Bank Sta=4236,4345
XS Rating Curve= 0
Exp/Cntr=.5,.3

Type RM Length L Ch R = 1 ,12503.04,950,808.16,750
BEGIN DESCRIPTION:
XS' central segment is manually adjusted for a skewed angle of 55 degree.  Skew option was not used because the skewed segment is small portion of entire XS which is NOT skewed.
END DESCRIPTION:
XS GIS Cut Line= 5
     3231191.159     13913056.68     3228260.242     13910184.88
     3228313.089    13909839.381     3228246.332    13909678.676
     3226434.679    13908024.742
#Sta/Elev= 30
       0   51.27  1086.7   49.85 1209.07   48.62 1793.98    47.6 1979.99   48.52
 2367.71   47.472418.289   49.17 2458.39   47.282637.339   49.033465.729   47.95
 3639.02   49.033722.919   47.65    4148   48.234239.041   47.13    4366   49.09
    4401    43.8    4414   37.68    4420   36.72    4429    37.8    4439   43.35
    4462    45.1    4475   48.81    4571    47.54600.089    44.6 4642.46   47.32
4684.931   47.48 5986.41    49.3 6040.29   50.76 6524.34   51.87 7079.97   51.96
#Mann= 5 ,-1 , 0
       0     .04       0  1086.7     .11       0 1979.99     .04       0
    4366    .045       0    4475     .04       0
#XS Ineff= 2 , 0
       0 2729.29   49.11               0
Permanent Ineff=
       F       F
Bank Sta=4366,4475
XS Rating Curve= 0
Exp/Cntr=.3,.1

Type RM Length L Ch R = 1 ,11694.88,971.31,971.31,971.31
BEGIN DESCRIPTION:
Section K -
END DESCRIPTION:
XS GIS Cut Line= 4
      3231695.62    13912915.901     3228942.459    13909423.104
     3228855.735    13909254.611     3226299.062    13906885.833
#Sta/Elev= 30
       0   50.46  252.25   49.06 1020.61   49.32  1612.7   47.02 1672.78   48.04
 1724.77   46.96  1765.5   47.92 2088.23   46.91 2206.82    48.5 2338.49   48.15
    2379   49.34 2537.92    49.2 2591.32   47.61 3866.46   47.89 4267.56   46.44
    4508   46.72    4521   41.11    4534   40.94    4540   37.53    4548   36.96
    4553   37.21    4555   39.58    4580   41.08    4595   47.37 4895.19   46.63
 4995.58   46.57 5163.75    47.4 5201.58   46.49 6209.94   50.19 8122.27   51.97
#Mann= 6 ,-1 , 0
       0     .11       0  1765.5     .04       0    4508    .045       0
    4595     .04       0 4895.19     .08       0 4995.58     .04       0
#XS Ineff= 2 , 0
       0    2379   49.34               0
Permanent Ineff=
       F       F
Bank Sta=4508,4595
XS Rating Curve= 0
Exp/Cntr=.3,.1

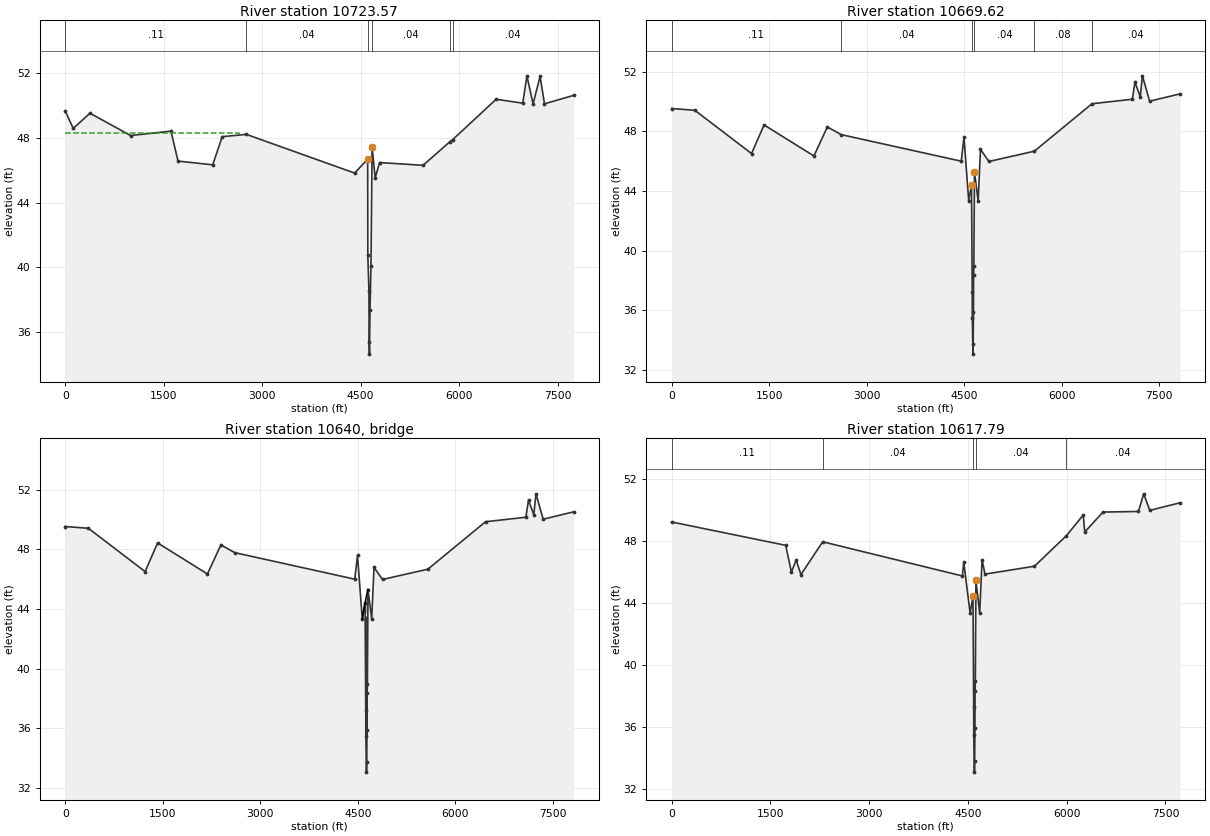
Type RM Length L Ch R = 1 ,10723.57,53.96,53.96,53.96
BEGIN DESCRIPTION:
Section J -
END DESCRIPTION:
XS GIS Cut Line= 5
     3232282.202    13912939.364     3230003.169    13909281.245
     3229874.126     13909096.03     3229770.057    13908962.227
     3227519.153    13906921.028
#Sta/Elev= 30
       0   49.66  122.41   48.58  377.24   49.52  996.14   48.14 1611.04   48.41
  1719.2   46.56 2247.12   46.33 2391.95   48.07  2760.5   48.21 4408.41   45.82
    4608   46.68    4610   40.75    4627   38.54    4630    35.4    4635   34.63
    4643   37.37    4658   40.05    4675   47.41    4722   45.53 4789.92   46.47
 5451.97    46.3  5855.5   47.74  5901.1   47.88 6564.42   50.38 6970.52   50.14
 7033.33   51.83  7127.5    50.1  7234.3   51.79 7301.29    50.1 7743.81   50.62
#Mann= 6 ,-1 , 0
       0     .11       0  2760.5     .04       0    4608    .045       0
    4675     .04       0  5855.5     .08       0  5901.1     .04       0
#XS Ineff= 2 , 0
       0 2640.35    48.3               0
Permanent Ineff=
       F       F
Bank Sta=4608,4675
XS Rating Curve= 0
Exp/Cntr=.5,.3

Type RM Length L Ch R = 1 ,10669.62,51.82,51.82,51.82
XS GIS Cut Line= 4
     3232329.129    13912904.169     3230005.451    13909135.675
     3229722.978    13908853.202     3227519.153    13906827.175
#Sta/Elev= 30
       0   49.53  356.82   49.41 1228.89   46.51 1421.41   48.43 2188.16   46.35
 2394.68   48.29 2608.08   47.78 4454.63      46 4497.05    47.6    4570   43.34
    4613   44.43    4624   37.26    4625    35.5    4635   33.07    4639   33.76
    4643   35.91    4645   38.34    4649   38.96 4658.39   45.28    4715   43.34
    4751   46.79 4881.46   45.98  5579.6   46.67 6466.71   49.85 7086.85   50.15
  7127.6   51.29 7209.11   50.32 7242.43   51.72 7353.25   50.02 7820.38   50.51
#Mann= 6 ,-1 , 0
       0     .11       0 2608.08     .04       0    4613    .045       0
 4658.39     .04       0  5579.6     .08       0 6466.71     .04       0
#XS Ineff= 2 , 0
       0 4614.54   43.34 4658.39       0   43.34
Permanent Ineff=
       F       F
Bank Sta=4613,4658.39
XS Rating Curve= 0
Exp/Cntr=.5,.3

Type RM Length L Ch R = 3 ,10640   ,,,
BEGIN DESCRIPTION:
Wood bridge
END DESCRIPTION:
Bridge Culvert--1,0,-1,-1, 0
Deck Dist Width WeirC Skew NumUp NumDn MinLoCord MaxHiCord MaxSubmerge Is_Ogee
20,12,2.6,0, 6, 6, , , .95, 0, 0,0,,
    4570    4613    4613    4657    4657 4658.39
   43.34   44.43   44.43   45.34   45.34   45.28
                   43.23   44.13
    4533    4576    4576    4620    4620 4621.06
   43.34   44.43   44.43   45.34   45.34   45.47
                   43.23   44.13
Pier Skew, UpSta & Num, DnSta & Num=  ,4627, 2 ,4590, 2 , 0 , 0 , 0 ,,
     1.2     1.2
      30      50
     1.2     1.2
      30      50
Pier Skew, UpSta & Num, DnSta & Num=  ,4642, 2 ,4605, 2 , 0 , 0 , 0 ,,
     1.2     1.2
      30      50
     1.2     1.2
      30      50
BR Coef=-1 , 1 , 1 ,1.05, 0 ,,,.8,-1,1.2,0,
WSPro=,,,, 1 ,,,, 0 ,,,, 0 ,,,,-1 ,-1 ,-1 , 0 , 0 , 0 , 0 , 0
BR U #Sta/Elev= 30
       0   49.53  356.82   49.41 1228.89   46.51 1421.41   48.43 2188.16   46.35
 2394.68   48.29 2608.08   47.78 4454.63      46 4497.05    47.6    4570   43.34
    4613   44.43    4624   37.26    4625    35.5    4635   33.07    4639   33.76
    4643   35.91    4645   38.34    4649   38.96 4658.39   45.28    4715   43.34
    4751   46.79 4881.46   45.98  5579.6   46.67 6466.71   49.85 7086.85   50.15
  7127.6   51.29 7209.11   50.32 7242.43   51.72 7353.25   50.02 7820.38   50.51
BR U #Mann= 6
       0     .11 2608.08     .04    4613    .044 4658.39     .04  5579.6     .08
 6466.71     .04
BR D #Sta/Elev= 30
       0   49.24  1731.8   47.73 1818.25   46.01 1891.02   46.77 1962.89   45.84
 2293.73   47.96 4415.13   45.75 4436.38   46.64    4533   43.34    4576   44.43
    4587   37.26    4588    35.5    4598   33.07    4602   33.76    4606   35.91
    4608   38.34    4612   38.96 4621.06   45.47    4678   43.34    4714   46.79
 4758.83   45.87 5510.19   46.38 5996.14   48.36 6250.83   49.69 6273.71   48.59
  6550.3   49.88 7089.16   49.92 7168.62   51.06 7261.69   49.99 7720.35   50.48
BR D #Mann= 5
       0     .11 2293.73     .04    4576    .044 4621.06     .04 5996.14     .04
BC Design=,, 0 ,, 0 ,,,,,,

Type RM Length L Ch R = 1 ,10617.79,46.6,46.6,46.6
XS GIS Cut Line= 4
     3232376.055    13912822.047     3230047.574    13909100.986
     3229760.145     13908820.99     3227624.738    13906815.443
#Sta/Elev= 30
       0   49.24  1731.8   47.73 1818.25   46.01 1891.02   46.77 1962.89   45.84
 2293.73   47.96 4415.13   45.75 4436.38   46.64    4533   43.34    4576   44.43
    4587   37.26    4588    35.5    4598   33.07    4602   33.76    4606   35.91
    4608   38.34    4612   38.96 4621.06   45.47    4678   43.34    4714   46.79
 4758.83   45.87 5510.19   46.38 5996.14   48.36 6250.83   49.69 6273.71   48.59
  6550.3   49.88 7089.16   49.92 7168.62   51.06 7261.69   49.99 7720.35   50.48
#Mann= 5 ,-1 , 0
       0     .11       0 2293.73     .04       0    4576    .045       0
 4621.06     .04       0 5996.14     .04       0
#XS Ineff= 2 , 0
       0    4576   43.34 4621.06       0   43.34
Permanent Ineff=
       F       F
Bank Sta=4576,4621.06
XS Rating Curve= 0
Exp/Cntr=.5,.3