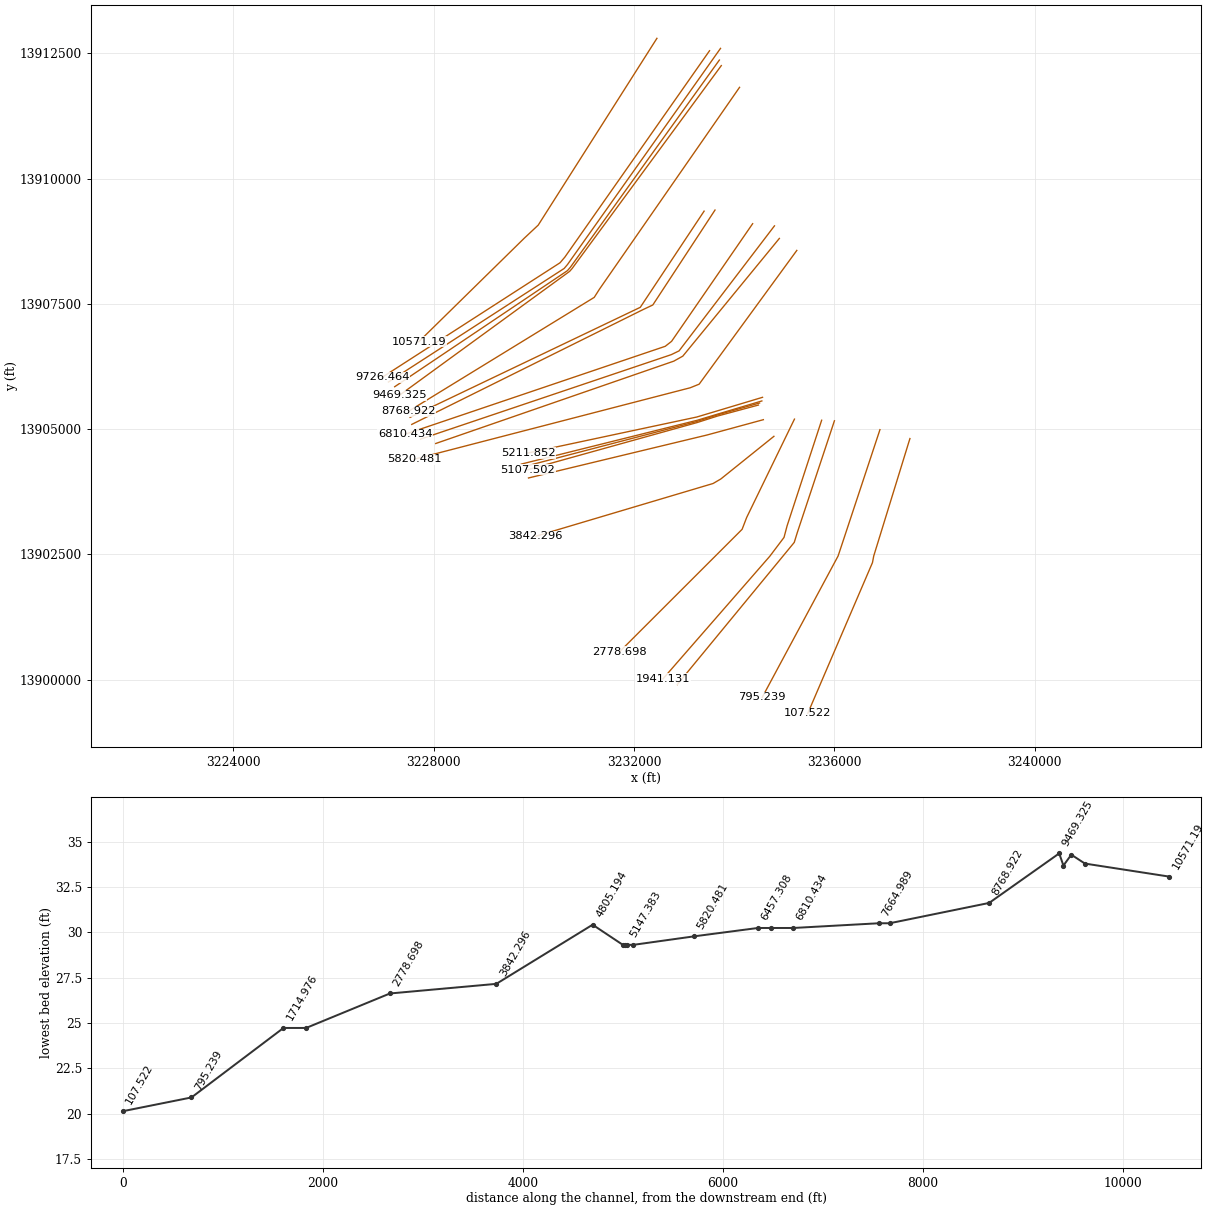
HEC-RAS study Q128-00-00.prj: Q128-00-00

--- Q128-00-00.g05 (geometry) --- (continued)

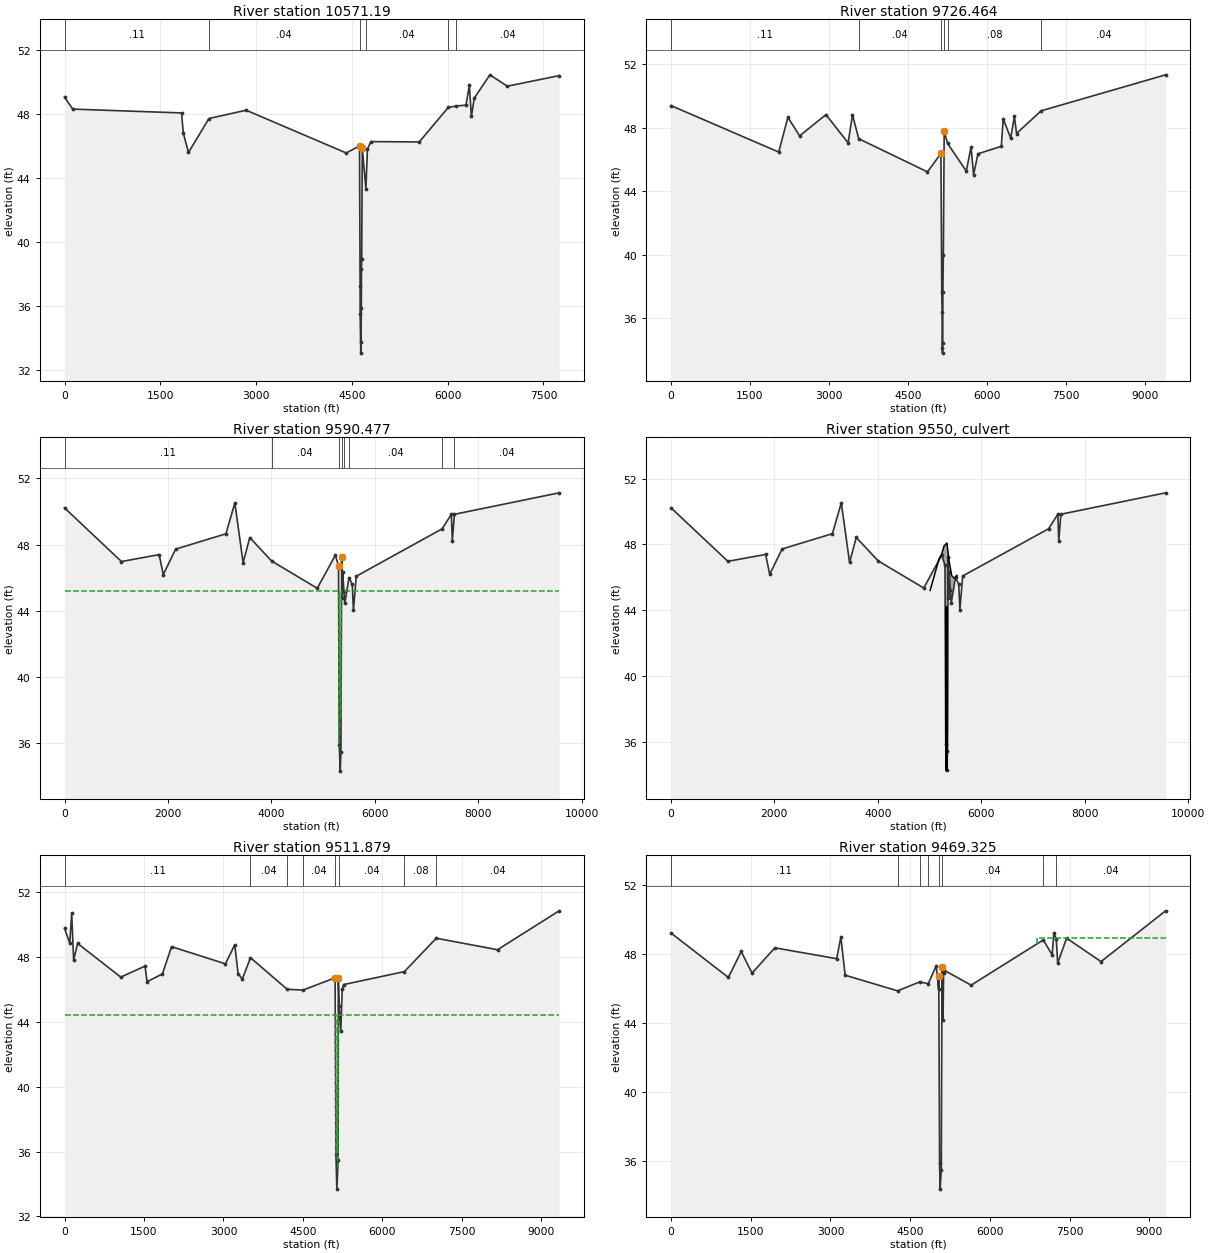
Type RM Length L Ch R = 1 ,10571.19,844.73,844.73,844.73
XS GIS Cut Line= 4
     3232458.177    13912798.584     3230089.697    13909071.252
      3229812.18    13908811.079     3227706.859    13906745.054
#Sta/Elev= 30
       0   49.06  128.73   48.31 1832.31   48.07 1860.28   46.81 1941.49    45.6
 2261.39   47.72 2844.49   48.24 4411.82   45.57 4620.11   46.01    4629   37.26
    4630    35.5    4640   33.07    4644   33.76    4648   35.91    4650   38.34
    4654   38.96 4662.98   45.87    4720   43.34 4743.83   45.81 4796.11   46.28
 5555.56   46.26 6009.13   48.41 6128.02    48.5 6287.13   48.56 6340.16   49.79
 6371.98   47.85 6417.22      49 6661.74   50.45 6935.38   49.74  7746.3    50.4
#Mann= 6 ,-1 , 0
       0     .11       0 2261.39     .04       0 4620.11    .045       0
    4720     .04       0 6009.13     .08       0 6128.02     .04       0
#XS Ineff= 2 , 0
       0 2844.49   48.24 6340.16       0   48.24
Permanent Ineff=
       F       F
Bank Sta=4620.11,4662.98
XS Rating Curve= 0
Exp/Cntr=.3,.1

Type RM Length L Ch R = 1 ,9726.464,135.99,135.99,135.99
BEGIN DESCRIPTION:
Section I -
END DESCRIPTION:
XS GIS Cut Line= 4
     3233508.549    13912551.269     3230622.432    13908434.448
     3230525.797    13908320.467     3226975.555    13906033.904
#Sta/Elev= 30
       0    49.4 2047.24   46.47 2221.61   48.66  2444.2   47.49 2944.87   48.83
  3366.2   47.05 3449.29   48.81 3567.71   47.31  4874.5   45.22    5130   46.38
    5146   37.66    5153   36.39    5155   34.09    5160   33.79    5164    34.4
    5167   37.62    5176   39.97    5192   47.77 5257.34   47.01 5612.13   45.27
 5702.29   46.78 5750.64   45.05 5833.74   46.36 6276.98   46.83 6313.45   48.56
 6456.19   47.35  6526.3   48.73 6566.51   47.64  7033.7   49.07 9400.01   51.34
#Mann= 6 ,-1 , 0
       0     .11       0 3567.71     .04       0    5130    .045       0
    5192     .04       0 5257.34     .08       0  7033.7     .04       0
#XS Ineff= 2 , 0
       0 2944.87   48.83 6313.45       0   48.56
Permanent Ineff=
       F       F
Bank Sta=5130,5192
XS Rating Curve= 0
Exp/Cntr=.5,.3

Type RM Length L Ch R = 1 ,9590.477,78.6,78.6,78.6
XS GIS Cut Line= 4
     3233727.357    13912598.156     3230674.467    13908285.777
     3230607.565    13908206.487     3227100.588    13905940.129
#Sta/Elev= 30
       0   50.22 1100.52   46.97 1829.37   47.39 1909.17   46.18 2148.09   47.72
 3120.64   48.65 3292.81   50.52 3452.95    46.9  3581.6   48.42  4004.3      47
 4886.46   45.35 5235.65   47.35    5297   46.72    5312   35.87    5330   34.28
    5344   35.46    5358   47.26  5364.8   44.76 5379.31   46.32 5400.85   45.21
 5417.87   44.43 5500.78      46 5563.58   45.58 5585.28   44.03 5639.67   46.08
 7300.84   48.95 7479.44   49.83  7497.3   48.23 7538.06   49.83 9562.93   51.13
#Mann= 8 ,-1 , 0
       0     .11       0  4004.3     .04       0    5297    .045       0
    5358     .04       0 5400.85     .08       0 5500.78     .04       0
 7300.84     .08       0 7538.06     .04       0
#XS Ineff= 2 , 0
       0  5313.5    45.2  5346.5       0    45.2
Permanent Ineff=
       F       F
Bank Sta=5297,5358
XS Rating Curve= 0
Exp/Cntr=.5,.3

Type RM Length L Ch R = 2 ,9550    ,,,
BEGIN DESCRIPTION:
3-120" CMP. L=51', at New Road
END DESCRIPTION:
Bridge Culvert--1,0,-1,-1, 0
Deck Dist Width WeirC Skew NumUp NumDn MinLoCord MaxHiCord MaxSubmerge Is_Ogee
13.5,51,2.6,0, 9, 7, , , .95, 0, 0,0,,
    5010    5182    5233    5281    5335    5376    5428    5480 5528.41
    45.2   47.12   47.41   47.91   48.08   46.99   46.09   45.94   46.12
                                                                        
    4930    4990    5043    5091    5145    5186 5240.52
    45.2   47.12   47.41   47.91   48.08   46.99   46.01
                                                        
Multiple Barrel Culv=1,10,,51,.0275,.5,1,2,1,34.23,33.69, 3,Culvert #1  , 0 ,13.5
    5319    5129    5330    5140    5341    5151
Culvert Bottom n=.0275
BC Design=,, 0 ,, 0 ,,,,,,

Type RM Length L Ch R = 1 ,9511.879,42.55,42.55,42.55
XS GIS Cut Line= 4
     3233704.521    13912364.966     3230731.475      13908230.6
     3230671.989    13908161.886     3227225.622    13905846.354
#Sta/Elev= 30
       0   49.77   98.58   48.86  135.53    50.7  172.48   47.81  246.58   48.84
 1061.84   46.76 1519.61   47.44 1558.15   46.48 1847.87   46.96 2019.82   48.64
 3036.21   47.58 3212.77   48.76 3276.39   46.97 3355.52   46.64 3509.68   47.96
 4202.07   46.01 4500.94   45.96    5107   46.72    5122   35.87    5140   33.68
    5164   35.46 5167.37   46.69 5183.23   44.95 5213.63   43.41 5240.52   46.01
 5267.42    46.3 6414.18    47.1  7015.7   49.16 8172.26   48.45 9335.23   50.85
#Mann= 8 ,-1 , 0
       0     .11       0 3509.68     .04       0 4202.07     .11       0
 4500.94     .04       0    5107    .045       0 5183.23     .04       0
 6414.18     .08       0  7015.7     .04       0
#XS Ineff= 2 , 0
       0  5123.5    44.4  5156.5       0    44.4
Permanent Ineff=
       F       F
Bank Sta=5107,5167.37
XS Rating Curve= 0
Exp/Cntr=.5,.3

Type RM Length L Ch R = 1 ,9469.325,700.4,700.4,700.4
XS GIS Cut Line= 5
     3233742.986    13912254.315     3230930.484    13908428.832
     3230765.016    13908203.767     3230715.822    13908147.864
     3227319.397    13905674.433
#Sta/Elev= 30
       0   49.23 1079.05   46.65 1321.04   48.16 1523.63    46.9 1954.08   48.37
 3115.45   47.74 3194.96   48.99 3275.94   46.78 4262.67   45.87 4676.77   46.39
 4839.82   46.29 4988.76   47.33 5033.38   45.97    5037   46.72    5052   35.87
    5062   34.35    5084   35.46    5098   47.26 5116.94   44.19 5127.08   46.89
 5132.37   47.08 5644.68    46.2 7003.58   48.83 7169.33   47.96 7201.54   49.22
 7247.25   48.88 7272.73   47.48 7441.71   48.93 8088.11   47.57 9303.53   50.52
#Mann= 8 ,-1 , 0
       0     .11       0 4262.67     .04       0 4676.77     .11       0
 4839.82     .04       0    5037    .045       0    5098     .04       0
 7003.58     .08       0 7247.25     .04       0
#XS Ineff= 2 , 0
       0 3194.96   48.99 6889.91       0   48.92
Permanent Ineff=
       F       F
Bank Sta=5037,5098
XS Rating Curve= 0
Exp/Cntr=.3,.1

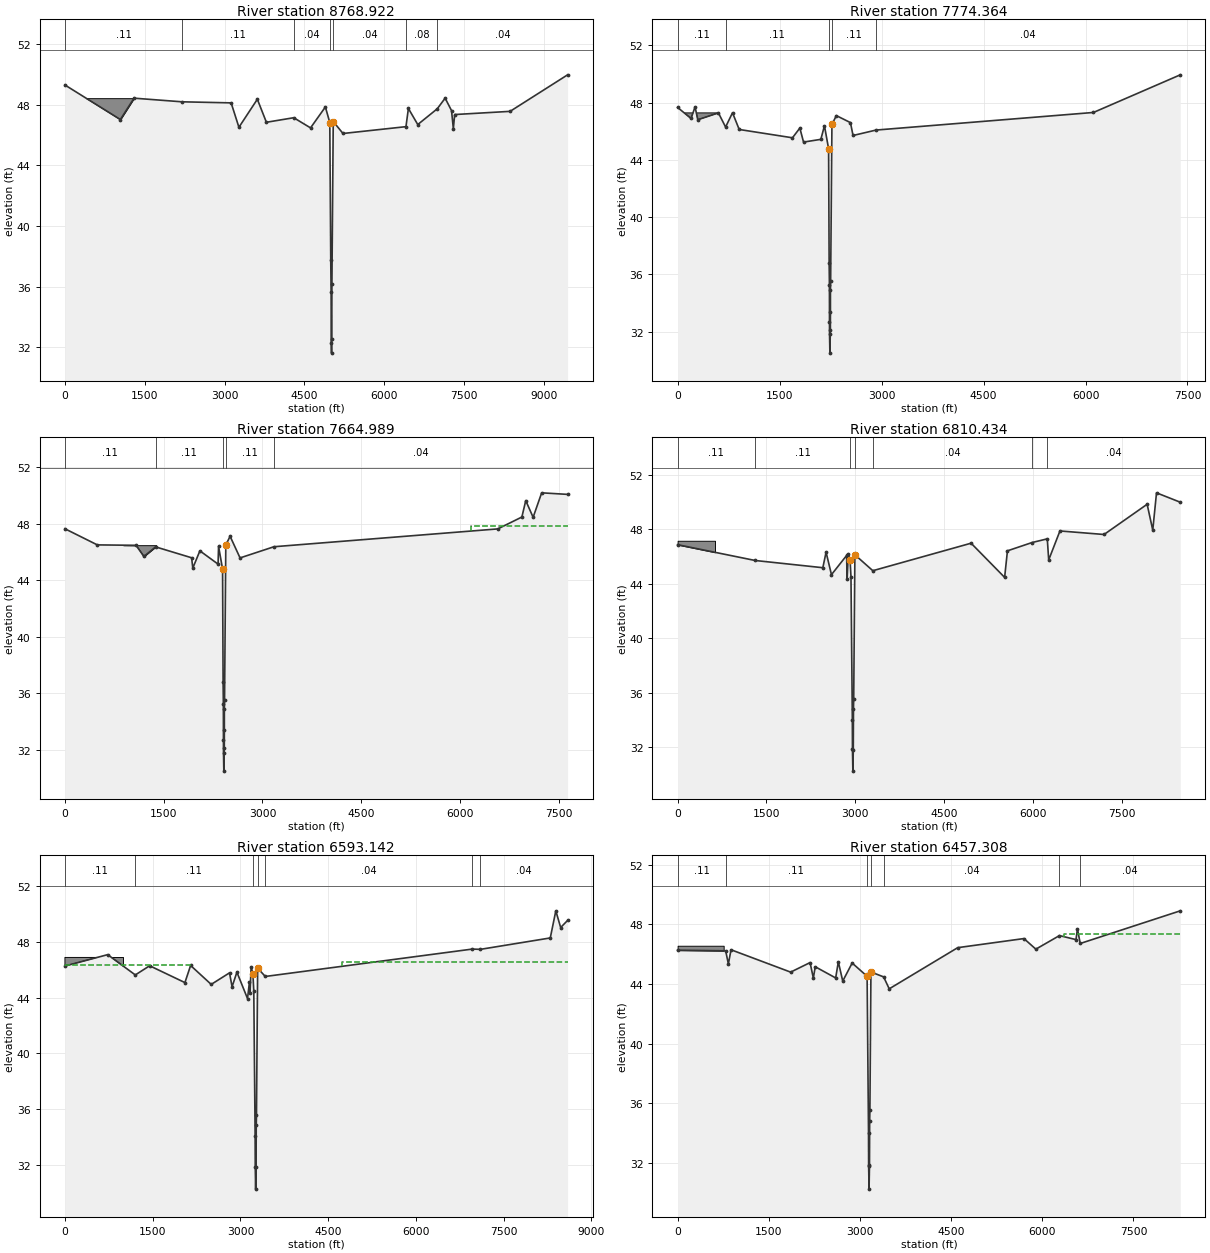
Type RM Length L Ch R = 1 ,8768.922,1150,994.56,800
BEGIN DESCRIPTION:
Section H,  use Blocked Obstruction Areas at DA boundary
END DESCRIPTION:
XS GIS Cut Line= 4
     3234107.241     13911820.75     3231311.271    13907792.688
     3231207.202    13907629.151     3227500.459    13905355.465
#Sta/Elev= 30
       0   49.31 1041.78   47.03 1298.82   48.44    2200    48.2 3123.35   48.13
 3269.43   46.52 3615.75   48.37 3785.64   46.85  4299.7   47.15 4615.37   46.48
 4894.28   47.86    4977   46.83    4995   37.79    5002   35.63    5005    32.3
    5010   31.62    5014   32.55    5017   36.18    5042    46.9 5225.11   46.11
 6408.27   46.56 6454.18   47.76 6630.15    46.7 6996.48   47.74 7144.72   48.44
 7264.69   47.62 7298.83   46.43 7323.79   47.36 8365.19   47.57 9445.69   49.98
#Mann= 7 ,-1 , 0
       0     .11       0    2200     .11       0  4299.7     .04       0
    4977    .045       0    5042     .04       0 6408.27     .08       0
 6996.48     .04       0
#XS Ineff= 2 , 0
       0 3615.75   48.37 7144.72       0   48.44
Permanent Ineff=
       F       F
#Block Obstruct= 2 , 0
       0 1298.82   48.44               0
Bank Sta=4977,5042
XS Rating Curve= 0
Exp/Cntr=.3,.1

Type RM Length L Ch R = 1 ,7774.364,109.38,109.38,109.38
BEGIN DESCRIPTION:
use Blocked Obstruction Areas at DA boundary
END DESCRIPTION:
XS GIS Cut Line= 4
      3233399.76     13909350.01      3232228.07     13907584.55
     3232126.479    13907430.924     3227533.112    13905235.738
#Sta/Elev= 30
       0   47.67  197.63    46.9  256.57   47.71  297.13   46.81  600.19   47.29
  705.81    46.3  807.52    47.3  906.24   46.13 1689.57   45.55 1798.07   46.23
 1852.32   45.25 2106.89   45.44    2160   46.39    2221   44.78    2229   36.77
    2233   35.24    2234    32.7    2235   31.81    2240    30.5    2247   32.13
    2248    33.4    2248    34.9    2251   35.55    2270   46.48    2335    47.1
 2542.47   46.61 2580.51   45.71 2919.11   46.09 6116.83   47.32 7394.03   49.95
#Mann= 5 ,-1 , 0
       0     .11       0  705.81     .11       0    2221    .045       0
    2270     .11       0 2919.11     .04       0
#XS Ineff= 2 , 0
       0  807.52    47.3               0
Permanent Ineff=
       F       F
#Block Obstruct= 2 , 0
       0  600.19   47.29               0
Bank Sta=2221,2270
XS Rating Curve= 0
Exp/Cntr=.3,.1

Type RM Length L Ch R = 1 ,7664.989,854.55,854.55,854.55
BEGIN DESCRIPTION:
Section G,  use Blocked Obstruction Areas at DA boundary
END DESCRIPTION:
XS GIS Cut Line= 4
     3233617.446    13909371.778     3232376.741    13907478.003
     3232173.558    13907381.367     3227565.765    13905094.241
#Sta/Elev= 30
       0   47.63     492   46.49 1080.16   46.46 1198.82   45.67    1377   46.35
 1923.87   45.58  1941.8   44.85  2049.4   46.07 2325.64   45.13    2333   46.39
    2394   44.78    2402   36.77    2406   35.24    2407    32.7    2408   31.81
    2413    30.5    2420   32.13    2421    33.4    2421    34.9    2424   35.55
    2443   46.48    2508    47.1 2659.35   45.57 3174.49   46.36 6573.83   47.62
 6938.89   48.46 6997.71   49.62 7109.71   48.44 7239.42   50.17 7633.19   50.06
#Mann= 5 ,-1 , 0
       0     .11       0    1377     .11       0    2394    .045       0
    2443     .11       0 3174.49     .04       0
#XS Ineff= 2 , 0
       0                 6159.31       0   47.85
Permanent Ineff=
       F       F
#Block Obstruct= 2 , 0
       0 1385.89   46.47               0
Bank Sta=2394,2443
XS Rating Curve= 0
Exp/Cntr=.3,.1

Type RM Length L Ch R = 1 ,6810.434,217.29,217.29,217.29
BEGIN DESCRIPTION:
use Blocked Obstruction Areas at DA boundary
END DESCRIPTION:
XS GIS Cut Line= 4
     3234368.464    13909099.671     3232750.894    13906751.997
     3232624.524    13906652.883     3227435.153    13904898.324
#Sta/Elev= 30
       0   46.87 1310.53   45.71 2452.74   45.18 2507.39   46.32 2598.47   44.67
 2854.32   46.08    2863   44.36    2883   46.21    2913   45.73    2928   44.51
    2951   34.03    2953   31.86    2960   30.24    2967   31.82    2970   34.83
    2974   35.54    2994   46.13 3297.16   44.96 4956.51   46.98 5522.94   44.47
 5570.44   46.42 5986.81   47.03 6243.64    47.3 6267.14   45.75 6457.15   47.88
 7202.14   47.62 7929.73   49.84 8024.73   47.94 8088.07   50.68 8489.54   49.99
#Mann= 7 ,-1 , 0
       0     .11       0 1310.53     .11       0    2913    .045       0
    2994     .11       0 3297.16     .04       0 5986.81     .08       0
 6243.64     .04       0
#XS Ineff= 2 , 0
       0                 4956.51       0   46.98
Permanent Ineff=
       F       F
#Block Obstruct= 2 , 0
       0  631.16   47.16               0
Bank Sta=2913,2994
XS Rating Curve= 0
Exp/Cntr=.3,.1

Type RM Length L Ch R = 1 ,6593.142,135.83,135.83,135.83
BEGIN DESCRIPTION:
use Blocked Obstruction Areas at DA boundary
END DESCRIPTION:
XS GIS Cut Line= 4
     3234803.837    13909056.133     3232899.917    13906561.354
     3232745.102    13906486.443     3227739.914    13904800.365
#Sta/Elev= 30
       0   46.28  731.11    47.1 1202.84   45.64 1448.14    46.3 2050.88   45.09
 2148.37   46.32 2500.35   44.96 2813.14   45.79  2857.1   44.79 2939.56   45.84
 3121.06   43.94 3154.33   45.15    3163   44.36    3183   46.21    3213   45.73
    3228   44.51    3251   34.03    3253   31.86    3260   30.24    3267   31.82
    3270   34.83    3274   35.54    3294   46.13 3424.63   45.53 6963.41    47.5
 7100.59   47.48 8295.72    48.3 8390.44   50.25 8473.32   49.05 8591.82   49.56
#Mann= 7 ,-1 , 0
       0     .11       0 1202.84     .11       0    3213    .045       0
    3294     .11       0 3424.63     .04       0 6963.41     .08       0
 7100.59     .04       0
#XS Ineff= 2 , 0
       0 2148.37   46.32 4740.26       0   46.59
Permanent Ineff=
       F       F
#Block Obstruct= 2 , 0
       0  995.28    46.9               0
Bank Sta=3213,3294
XS Rating Curve= 0
Exp/Cntr=.3,.1

Type RM Length L Ch R = 1 ,6457.308,636.83,636.83,636.83
BEGIN DESCRIPTION:
Section F, use Blocked Obstruction Areas at DA boundary
END DESCRIPTION:
XS GIS Cut Line= 4
     3234901.796    13908805.794     3232974.827    13906456.479
     3232795.043    13906356.599     3228044.675     13904713.29
#Sta/Elev= 30
       0   46.26  790.49   46.22  835.33   45.34  879.07   46.29 1859.63   44.79
 2179.38   45.43 2233.29   44.39 2264.64   45.15 2600.76    44.4 2644.31   45.48
 2717.16   44.19 2871.91    45.4    3118   44.51    3141   34.03    3143   31.86
    3150   30.24    3157   31.82    3160   34.83    3164   35.54  3180.9    44.8
 3389.83   44.47 3481.79   43.67 4608.72   46.43 5698.27   47.04 5894.36   46.33
 6282.98   47.24 6554.95   46.97 6578.54    47.7 6624.48   46.71 8270.75    48.9
#Mann= 7 ,-1 , 0
       0     .11       0  790.49     .11       0    3118    .045       0
  3180.9     .11       0 3389.83     .04       0 6282.98     .08       0
 6624.48     .04       0
#XS Ineff= 2 , 0
       0                 6358.82       0   47.36
Permanent Ineff=
       F       F
#Block Obstruct= 2 , 0
       0  757.72   46.56               0
Bank Sta=3118,3180.9
XS Rating Curve= 0
Exp/Cntr=.3,.1

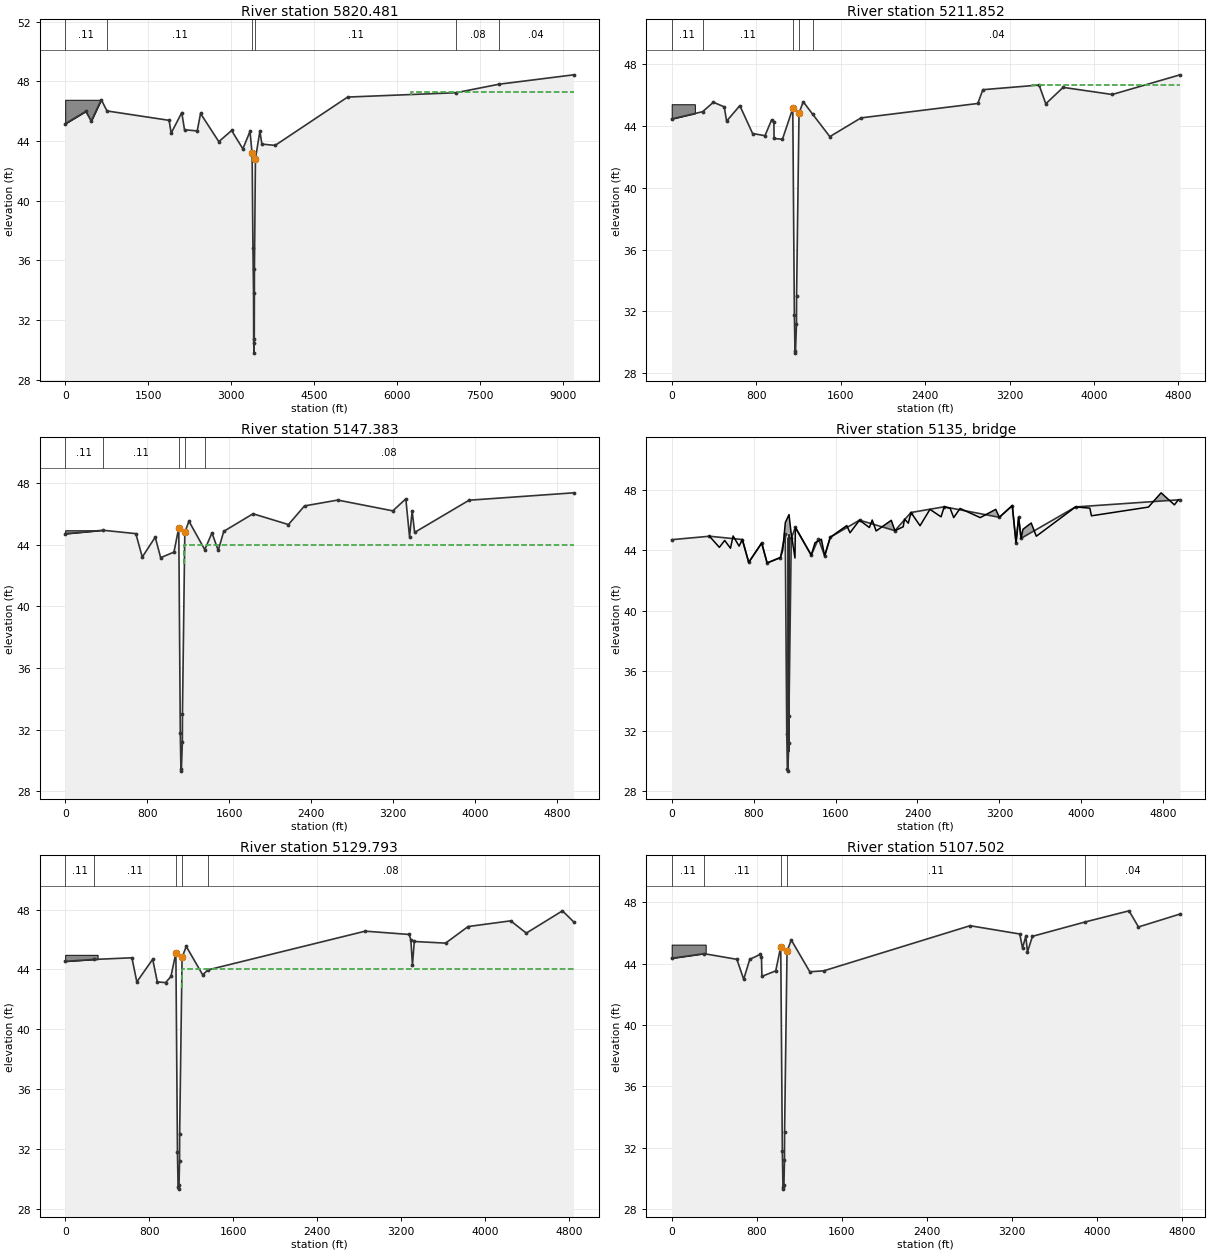
Type RM Length L Ch R = 1 ,5820.481,700,608.63,500
BEGIN DESCRIPTION:
use Blocked Obstruction Areas at DA boundary
END DESCRIPTION:
XS GIS Cut Line= 4
     3235250.094    13908566.339     3233300.974    13905897.143
     3233122.569    13905825.286     3227609.303    13904397.645
#Sta/Elev= 30
       0   45.15   372.4   45.98  470.86   45.33  652.19   46.76  755.52   46.01
 1878.82   45.38 1915.96   44.52  2108.1    45.9 2157.42   44.75 2387.21   44.67
 2447.53   45.84 2778.19   43.95 3009.02    44.7 3212.84   43.47    3342   44.64
    3380   43.16    3395   36.85    3406   33.79    3408   30.72    3414   29.78
    3419   30.49    3422   35.41    3440   42.81 3520.41   44.65 3556.98   43.79
 3795.74    43.7 5107.45   46.94  7066.1   47.23  7843.8    47.8 9192.54   48.43
#Mann= 6 ,-1 , 0
       0     .11       0  755.52     .11       0    3380    .045       0
    3440     .11       0  7066.1     .08       0  7843.8     .04       0
#XS Ineff= 2 , 0
       0                 6248.47       0   47.29
Permanent Ineff=
       F       F
#Block Obstruct= 2 , 0
       0  652.19   46.76               0
Bank Sta=3380,3440
XS Rating Curve= 0
Exp/Cntr=.3,.1

Type RM Length L Ch R = 1 ,5211.852,64.47,64.47,64.47
BEGIN DESCRIPTION:
Section E, use Blocked Obstruction Areas at DA boundary
END DESCRIPTION:
XS GIS Cut Line= 4
     3234565.697    13905634.801     3233664.579    13905364.529
     3233253.876    13905241.702     3229884.696     13904523.82
#Sta/Elev= 30
       0   44.43  293.16    44.9  395.05   45.51  498.12   45.21  520.34   44.29
  645.62   45.29  766.52   43.49  883.62   43.35  946.26   44.37  967.97   44.23
     970   43.17    1049   43.12    1147   45.11    1162   31.77    1168   29.43
    1172   29.31    1182   31.18    1183      33    1206   44.81    1246   45.54
    1335   44.74 1497.87   43.29 1793.49    44.5 2899.05   45.43 2947.24   46.32
 3479.87   46.62 3543.19   45.41 3707.44   46.47  4172.6   46.01 4814.26   47.28
#Mann= 5 ,-1 , 0
       0     .11       0  293.16     .11       0    1147    .045       0
    1206     .11       0    1335     .04       0
#XS Ineff= 2 , 0
       0                 3409.45       0   46.61
Permanent Ineff=
       F       F
#Block Obstruct= 2 , 0
       0  219.47   45.38               0
Bank Sta=1147,1206
XS Rating Curve= 0
Exp/Cntr=.5,.3

Type RM Length L Ch R = 1 ,5147.383,17.59,17.59,17.59
BEGIN DESCRIPTION:
use Blocked Obstruction Areas at DA boundary
END DESCRIPTION:
XS GIS Cut Line= 4
     3234552.083    13905562.191     3233667.991    13905299.392
     3233265.003    13905177.455     3229751.744    13904302.234
#Sta/Elev= 30
       0   44.72  369.01   44.95  689.87   44.73  752.46   43.21   879.1    44.5
     932   43.17    1062   43.53    1109   45.11    1124   31.77    1130   29.43
    1134   29.31    1144   31.18    1145      33    1168   44.81    1208   45.54
 1362.94   43.69 1433.05   44.78 1494.05   43.64 1548.44   44.88  1834.2   46.02
 2179.99   45.32 2336.82   46.53 2661.45   46.91 3199.35   46.21 3326.16   46.99
 3362.75   44.52 3387.99    46.2 3412.25   44.81 3943.98    46.9 4963.99   47.38
#Mann= 5 ,-1 , 0
       0     .11       0  369.01     .11       0    1109    .045       0
    1168     .11       0 1362.94     .08       0
#XS Ineff= 2 , 0
       0    1109      44    1164       0      44
Permanent Ineff=
       F       F
#Block Obstruct= 2 , 0
       0  369.01   44.95               0
Bank Sta=1109,1168
XS Rating Curve= 0
Exp/Cntr=.5,.3

Type RM Length L Ch R = 3 ,5135    ,,,
BEGIN DESCRIPTION:
Wood Bridge
END DESCRIPTION:
Bridge Culvert--1,0,-1,-1, 0
Deck Dist Width WeirC Skew NumUp NumDn MinLoCord MaxHiCord MaxSubmerge Is_Ogee
3,12,2.6,0, 60, 60, , , .95, 0, 0,0,,
  369.01   465.6  517.73  574.17  599.75  658.57  689.87  752.46   879.1     932
    1062    1084    1110    1110    1146    1164    1164    1204    1208 1362.94
 1399.83 1461.88 1494.05 1548.44 1710.09 1741.56  1834.2 1930.62  1958.3 1996.73
 2144.46 2179.99 2261.33 2273.71 2310.83 2336.82 2425.48 2522.32 2630.53 2661.45
 2719.22  2754.2 2816.03 3013.19 3164.74 3199.35 3326.16 3362.75 3387.99 3412.25
 3429.99 3510.98 3560.75 3943.98 4083.62 4099.09 4655.59 4779.25 4909.68 4947.99
   44.95   44.21   44.67   44.15   44.97   44.29   44.73   43.21    44.5   43.17
   43.53      44   45.87   45.87   46.39    45.3    45.3    43.5   45.54   43.69
   44.52   44.75   43.64   44.88   45.66   45.18   46.02   45.53   46.03    45.3
   46.01   45.32   45.58    46.1   45.82   46.53   45.65   46.74   46.24   46.91
   46.81   46.19    46.8   46.19   46.74   46.21   46.99   44.52    46.2   44.81
   45.41   45.83   44.95    46.9   46.82   46.31   46.89   47.84   47.04   47.38
                                                                                
                           44.67   45.19    44.1
                                                                                
                                                                                
                                                                                
                                                                                
  277.46  308.63  386.58  433.34  504.64  573.64  601.85  635.99  662.61  682.76
  740.54  833.99  861.56     878     957    1040    1056    1056    1092    1110
    1110    1150    1154    1288 1310.44 1360.45 1434.46 1465.47  1620.5  1651.5
 1852.71 1882.16 2086.37 2395.64 2473.15 2725.12 2767.71 2860.73 2904.37 3168.98
  3279.3 3294.81 3310.31 3327.35  3625.9 3759.89 3813.47  3840.9 3914.92 3964.71
 4183.87 4246.34 4380.01 4395.51 4411.01 4457.52 4488.52 4627.25 4740.16 4825.64
   44.67   44.98   44.29   44.69   44.24   44.54   44.16   44.78   44.21   43.17
   44.14   44.68   44.03   43.17   43.12      44   45.87   45.87   46.39    45.5
    45.5      44   45.54   44.35   43.64   43.97   43.64   44.16   44.34   44.74
   44.65   45.11   44.67   45.33   45.85   45.88   46.54   46.56   45.94   45.94
   46.34   45.97   44.29   45.87   45.76    46.5   46.35   46.87   46.97   46.49
   46.75   47.25   46.85   46.43   46.93   46.64   47.05   47.03   47.92   47.19
                                                                                
                                                           44.67   45.19    44.3
                                                                                
                                                                                
                                                                                
                                                                                
Pier Skew, UpSta & Num, DnSta & Num=  ,1126, 2 ,1072, 2 , 0 , 0 , 0 ,,
     1.2     1.2
      20      50
     1.2     1.2
      20      50
Pier Skew, UpSta & Num, DnSta & Num=  ,1141, 2 ,1087, 2 , 0 , 0 , 0 ,,
     1.2     1.2
      30      50
     1.2     1.2
      30      50
BR Coef=-1 , 1 , 1 ,1.05, 0 ,,,.8,-1,1.2,0,
WSPro=,,,, 1 ,,,, 0 ,,,, 0 ,,,,-1 ,-1 ,-1 , 0 , 0 , 0 , 0 , 0
BR U #Sta/Elev= 30
       0   44.72  369.01   44.95  689.87   44.73  752.46   43.21   879.1    44.5
     932   43.17    1062   43.53    1109   45.11    1124   31.77    1130   29.43
    1134   29.31    1144   31.18    1145      33    1168   44.81    1208   45.54
 1362.94   43.69 1433.05   44.78 1494.05   43.64 1548.44   44.88  1834.2   46.02
 2179.99   45.32 2336.82   46.53 2661.45   46.91 3199.35   46.21 3326.16   46.99
 3362.75   44.52 3387.99    46.2 3412.25   44.81 3943.98    46.9 4963.99   47.38
BR U #Mann= 5
       0     .11  369.01     .11    1109    .044    1168     .11 1362.94     .08
BR D #Sta/Elev= 30
       0   44.54  277.46   44.67  635.99   44.78  682.76   43.17  833.99   44.68
     878   43.17     957   43.12    1008   43.53    1055   45.11    1070   31.77
    1076   29.43    1080   29.31    1085   29.61    1090   31.18    1091      33
    1114   44.81    1154   45.54 1310.44   43.64 1360.45   43.97 2859.64   46.56
  3279.3   46.34 3294.81   45.97 3310.31   44.29 3327.35   45.87  3625.9   45.76
  3840.9   46.87 4246.34   47.25 4395.51   46.43 4740.16   47.92 4845.64   47.19
BR D #Mann= 5
       0     .11  277.46     .11    1055    .044    1114     .11 1360.45     .08
BC Design=,, 0 ,, 0 ,,,,,,

Type RM Length L Ch R = 1 ,5129.793,22.29,22.29,22.29
BEGIN DESCRIPTION:
use Blocked Obstruction Areas at DA boundary
END DESCRIPTION:
XS GIS Cut Line= 4
     3234506.702    13905521.349     3233669.478    13905284.521
     3233241.506    13905148.836     3229829.299    13904257.917
#Sta/Elev= 30
       0   44.54  277.46   44.67  635.99   44.78  682.76   43.17  833.99   44.68
     878   43.17     957   43.12    1008   43.53    1055   45.11    1070   31.77
    1076   29.43    1080   29.31    1085   29.61    1090   31.18    1091      33
    1114   44.81    1154   45.54 1310.44   43.64 1360.45   43.97 2859.64   46.56
  3279.3   46.34 3294.81   45.97 3310.31   44.29 3327.35   45.87  3625.9   45.76
  3840.9   46.87 4246.34   47.25 4395.51   46.43 4740.16   47.92 4845.64   47.19
#Mann= 5 ,-1 , 0
       0     .11       0  277.46     .11       0    1055    .045       0
    1114     .11       0 1360.45     .08       0
#XS Ineff= 2 , 0
       0    1055      44    1110       0      44
Permanent Ineff=
       F       F
#Block Obstruct= 2 , 0
       0  308.63   44.98               0
Bank Sta=1055,1114
XS Rating Curve= 0
Exp/Cntr=.5,.3

Type RM Length L Ch R = 1 ,5107.502,305.1,302.31,298.97
BEGIN DESCRIPTION:
use Blocked Obstruction Areas at DA boundary
END DESCRIPTION:
XS GIS Cut Line= 4
     3234484.012    13905480.506     3233666.504    13905260.729
     3233261.328    13905131.491     3229884.696    13904191.441
#Sta/Elev= 30
       0   44.35  303.96   44.65  612.79   44.28  676.74   42.98  733.77   44.28
  832.07    44.6  843.94    44.4     848   43.17     978   43.53    1025   45.11
    1040   31.77    1046   29.43    1050   29.31    1055   29.61    1060   31.18
    1061      33    1084   44.81    1124   45.54 1298.14   43.47 1428.41   43.53
 2804.11   46.47 3271.24   45.93 3296.86   45.02 3328.01   45.78 3343.58   44.76
 3390.29   45.78 3888.54   46.72 4297.77   47.44  4386.8   46.39 4776.87   47.23
#Mann= 5 ,-1 , 0
       0     .11       0  303.96     .11       0    1025    .045       0
    1084     .11       0 3888.54     .04       0
#XS Ineff= 2 , 0
       0                 2804.11       0   46.47
Permanent Ineff=
       F       F
#Block Obstruct= 2 , 0
       0  319.49   45.24               0
Bank Sta=1025,1084
XS Rating Curve= 0
Exp/Cntr=.3,.1

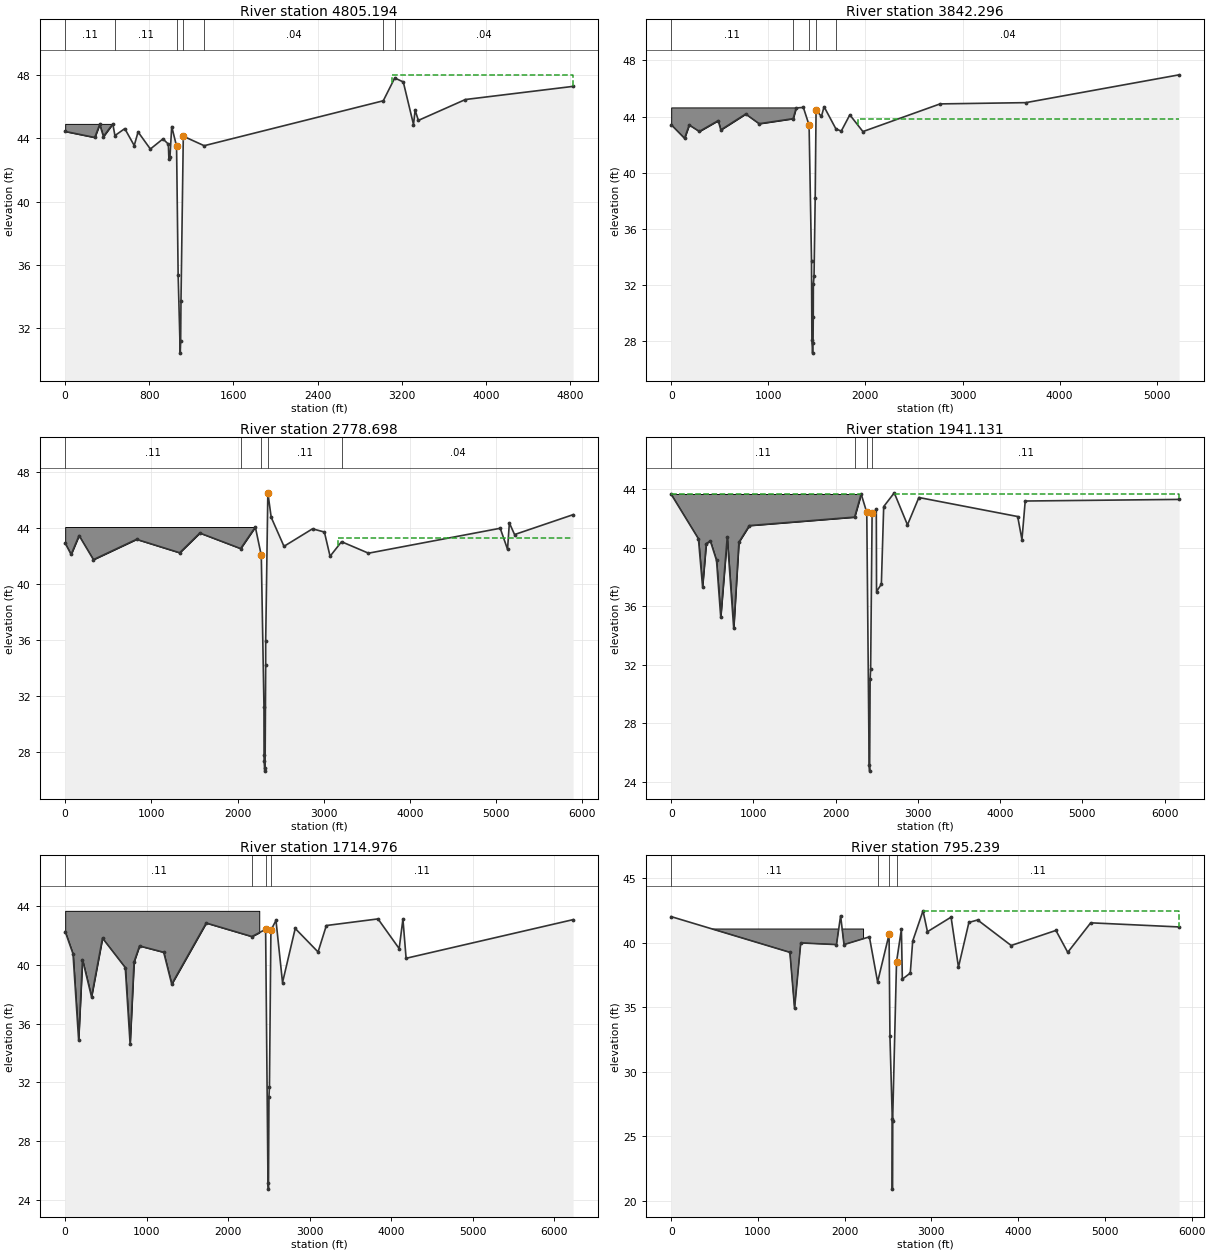
Type RM Length L Ch R = 1 ,4805.194,962.9,962.9,962.9
BEGIN DESCRIPTION:
Section D, use Blocked Obstruction Areas at DA boundary
END DESCRIPTION:
XS GIS Cut Line= 4
     3234582.325    13905188.579     3233635.482    13904930.787
     3233452.122     13904881.23     3229895.775    13904025.251
#Sta/Elev= 30
       0   44.43  281.44   44.05  328.38   44.88  363.67   44.11  452.75   44.91
  472.92   44.17  566.61   44.61  656.46   43.54  693.11    44.4  809.85   43.32
  929.55   43.96  980.85   43.63     986    42.7     996   42.81    1013   44.74
    1059    43.5    1074   35.35    1094   30.42    1098    31.2    1101    33.7
    1123   44.13 1321.51   43.53 3024.33   46.37 3133.44   47.81 3214.71   47.56
 3311.77   44.87  3327.2   45.78 3358.06   45.13 3805.48   46.45 4829.16   47.28
#Mann= 7 ,-1 , 0
       0     .11       0  472.92     .11       0    1059    .045       0
    1123     .11       0 1321.51     .04       0 3024.33     .08       0
 3133.44     .04       0
#XS Ineff= 2 , 0
       0                 3110.03       0   48.01
Permanent Ineff=
       F       F
#Block Obstruct= 2 , 0
       0  452.75   44.91               0
Bank Sta=1059,1123
XS Rating Curve= 0
Exp/Cntr=.3,.1

Type RM Length L Ch R = 1 ,3842.296,900,1063.6,1200
BEGIN DESCRIPTION:
Section C, use Blocked Obstruction Areas at DA boundary
END DESCRIPTION:
XS GIS Cut Line= 4
     3234792.832      13904856.2     3233732.117    13904004.076
     3233578.491    13903914.874     3230039.806    13902861.923
#Sta/Elev= 30
       0   43.42  137.74   42.45  185.64    43.4  289.93   42.94  484.04   43.71
  511.15   43.05  767.22   44.18  905.92   43.49 1256.19   43.85 1286.69   44.61
    1361   44.65    1420   43.39    1445   33.75    1449   28.11    1456   27.16
    1461   27.88    1463   29.76    1464   32.08    1471   32.63    1483   38.23
    1492   44.46    1547   44.01 1574.34    44.7 1697.24   43.11 1751.74   42.97
  1839.6   44.12  1974.4   42.93 2768.91    44.9 3652.16   44.99 5230.26   46.97
#Mann= 5 ,-1 , 0
       0     .11       0 1256.19     .11       0    1420    .045       0
    1492     .11       0 1697.24     .04       0
#XS Ineff= 2 , 0
       0                 1924.64       0   43.84
Permanent Ineff=
       F       F
#Block Obstruct= 2 , 0
       0 1297.33   44.65               0
Bank Sta=1420,1492
XS Rating Curve= 0
Exp/Cntr=.3,.1

Type RM Length L Ch R = 1 ,2778.698,837.57,837.57,837.57
BEGIN DESCRIPTION:
Section B, use Blocked Obstruction Areas at DA boundary
END DESCRIPTION:
XS GIS Cut Line= 4
     3235202.767    13905199.658     3234249.985    13903238.424
     3234158.305    13903000.552     3231712.783    13900557.425
#Sta/Elev= 30
       0    42.9   68.85    42.1   160.9   43.45  327.66   41.73  827.95   43.18
 1328.24   42.22 1561.71   43.63 2035.22   42.52    2206   44.06    2275   42.03
    2306   31.24    2307   27.78    2308   27.38    2315   26.63    2319   26.85
    2326   34.18    2326   35.92    2351    46.5    2390   44.75 2538.29   42.68
 2869.12   43.93    3007    43.7 3072.93   41.97 3205.94   43.01 3518.62   42.19
 5046.72   43.97 5131.62   42.47 5152.84   44.35 5213.18   43.52 5892.14   44.94
#Mann= 5 ,-1 , 0
       0     .11       0 2035.22     .11       0    2275    .045       0
    2351     .11       0 3205.94     .04       0
#XS Ineff= 2 , 0
       0                  3166.1       0    43.3
Permanent Ineff=
       F       F
#Block Obstruct= 2 , 0
       0    2206   44.06 5046.72       0   43.97
Bank Sta=2275,2351
XS Rating Curve= 0
Exp/Cntr=.3,.1

Type RM Length L Ch R = 1 ,1941.131,226.15,226.15,226.15
BEGIN DESCRIPTION:
use Blocked Obstruction Areas at DA boundary
END DESCRIPTION:
XS GIS Cut Line= 5
     3235745.653      13905177.5     3235056.397    13903071.382
     3234994.692      13902838.8     3234711.233    13902463.408
     3232576.969    13900014.539
#Sta/Elev= 30
       0   43.65  331.16   40.61  381.49   37.34  426.29   40.28  476.18   40.46
  551.15   39.13  602.45   35.26  681.36   40.71  760.27   34.49  823.41   40.38
  949.98   41.51 2230.37   42.09    2310   43.67    2378   42.41    2407   25.17
    2413   24.73    2419   31.03    2425   31.69    2443   42.35    2494   42.62
 2496.84      37 2555.48   37.51  2583.8   42.81 2712.31   43.75 2872.96   41.56
 3011.63   43.43 4212.92   42.13 4264.78   40.55 4304.57   43.19 6175.44    43.3
#Mann= 4 ,-1 , 0
       0     .11       0 2230.37     .11       0    2378    .045       0
    2443     .11       0
#XS Ineff= 2 , 0
       0    2310   43.67 2720.87       0   43.67
Permanent Ineff=
       F       F
#Block Obstruct= 2 , 0
       0    2310   43.67 4304.57       0   43.19
Bank Sta=2378,2443
XS Rating Curve= 0
Exp/Cntr=.3,.1

Type RM Length L Ch R = 1 ,1714.976,919.74,919.74,919.74
BEGIN DESCRIPTION:
Section A, use Blocked Obstruction Areas at DA boundary
END DESCRIPTION:
XS GIS Cut Line= 4
     3236000.478    13905166.421       3235260.5    13902938.478
     3235198.794    13902739.122     3232865.031    13899903.746
#Sta/Elev= 30
       0   42.26    96.1   40.74  164.89   34.89  212.31   40.35  322.95   37.82
  457.68   41.81   736.8   39.81  796.13   34.61  844.54   40.19  911.63   41.28
 1208.07   40.85 1306.32   38.68 1729.66   42.84 2290.06   41.92    2458   42.41
    2487   25.17    2493   24.73    2499   31.03    2505   31.69    2523   42.35
 2585.13   43.02 2665.34   38.79 2820.94   42.47  3101.1   40.87 3202.78   42.67
  3836.1   43.12 4095.74    41.1 4141.84   43.11 4180.69   40.44 6228.61   43.07
#Mann= 4 ,-1 , 0
       0     .11       0 2290.06     .11       0    2458    .045       0
    2523     .11       0
#XS Ineff= 2 , 0
       0                 2820.94       0   42.47
Permanent Ineff=
       F       F
#Block Obstruct= 2 , 0
       0    2380   43.67  3836.1       0   43.12
Bank Sta=2458,2523
XS Rating Curve= 0
Exp/Cntr=.3,.1

Type RM Length L Ch R = 1 ,795.239 ,687.72,687.72,687.72
BEGIN DESCRIPTION:
use Blocked Obstruction Areas at DA boundary
END DESCRIPTION:
XS GIS Cut Line= 4
     3236908.982    13904989.151     3236140.574    13902668.522
     3236073.673    13902467.817     3234560.167    13899648.921
#Sta/Elev= 30
       0   42.04 1368.59   39.27 1422.64   34.92 1493.87      40 1905.82   39.87
 1953.22   42.11 1992.42   39.87 2285.04   40.47 2379.85   36.97    2512   40.66
    2522   32.77    2549   26.37    2550    20.9    2553   26.17    2598   38.53
    2654   41.06 2665.05   37.19 2756.59   37.66 2784.22   40.14  2903.4   42.49
 2954.48   40.87 3226.88      42 3312.01   38.12 3432.33   41.59 3533.34   41.78
 3919.74    39.8 4435.68   40.97 4571.88   39.27 4836.72   41.56 5855.61   41.24
#Mann= 4 ,-1 , 0
       0     .11       0 2379.85     .11       0    2512    .045       0
    2598     .11       0
#XS Ineff= 2 , 0
       0                  2903.4       0   42.49
Permanent Ineff=
       F       F
#Block Obstruct= 2 , 0
       0 2217.96   41.08 3053.94       0   42.43
Bank Sta=2512,2598
XS Rating Curve= 0
Exp/Cntr=.3,.1

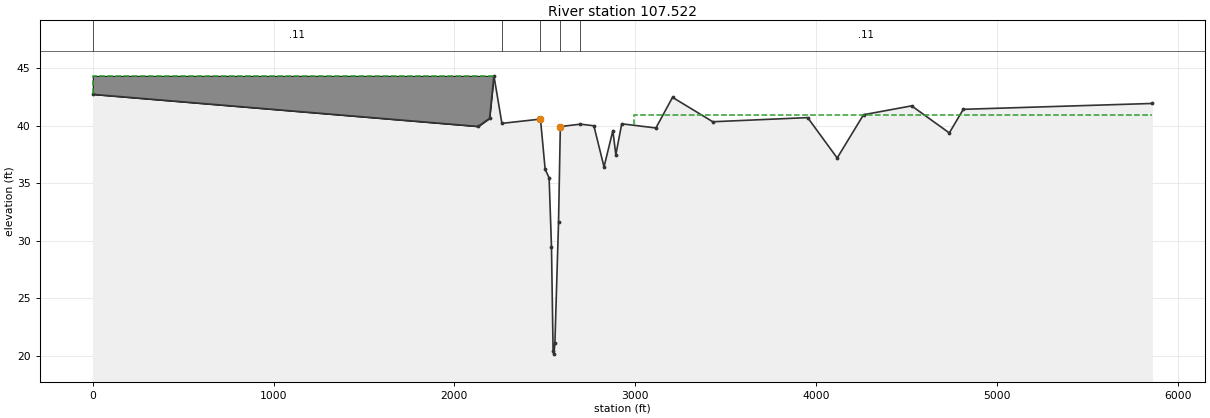
Type RM Length L Ch R = 1 ,107.522 ,107.52,107.52,107.52
BEGIN DESCRIPTION:
use Blocked Obstruction Areas at DA boundary
END DESCRIPTION:
XS GIS Cut Line= 4
     3237507.265    13904811.882     3236784.812    13902467.817
     3236760.033    13902336.492     3235468.671    13899327.621
#Sta/Elev= 30
       0   42.71  2131.5   39.92 2194.68   40.63 2218.68   44.32  2262.9   40.19
 2476.16   40.56    2502    36.2    2524   35.45    2537   29.48    2546   20.38
    2550   20.14    2556   21.11    2576   31.58    2586   39.91 2697.03   40.12
 2771.44   39.98 2827.61   36.41 2876.58   39.56 2892.91   37.46 2925.55   40.15
 3114.59   39.79 3206.59   42.45 3429.15   40.33 3953.91   40.69 4117.14   37.18
 4262.81   40.94 4528.98   41.71 4737.42   39.36 4814.51   41.41 5860.79   41.92
#Mann= 5 ,-1 , 0
       0     .11       0  2262.9     .11       0 2476.16    .045       0
    2586     .11       0 2697.03     .11       0
#XS Ineff= 2 , 0
       0 2218.68   44.32 2990.84       0   40.91
Permanent Ineff=
       F       F
#Block Obstruct= 2 , 0
       0 2218.68   44.32 2990.84       0   40.91
Bank Sta=2476.16,2586
XS Rating Curve= 0
Exp/Cntr=.3,.1

Chan Stop Cuts=-1